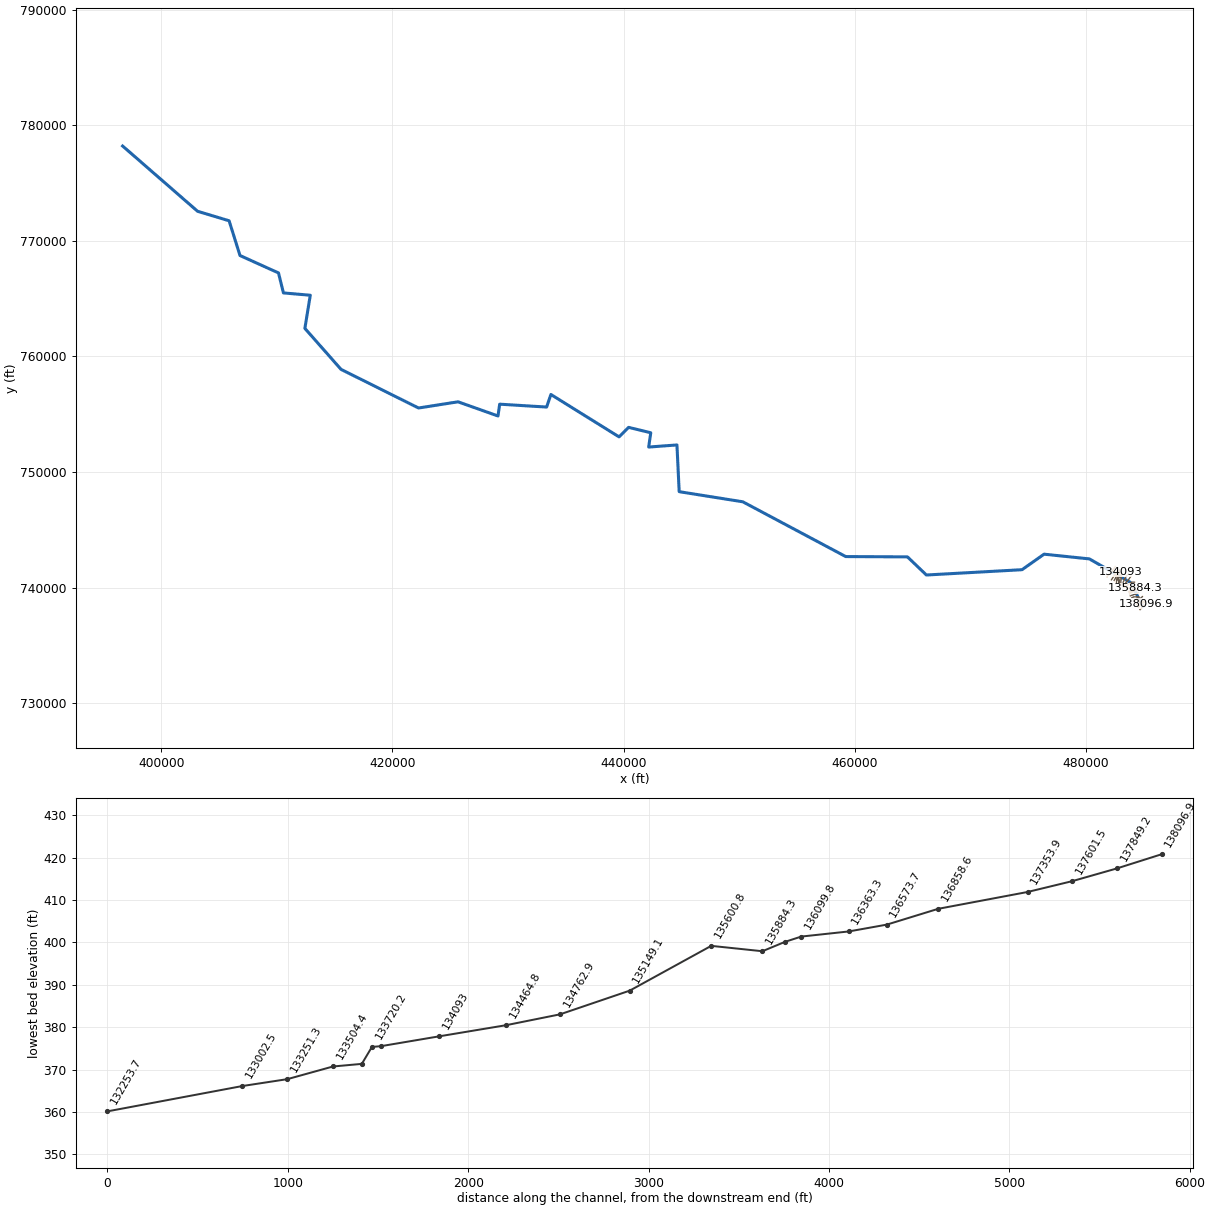
--- 2549_ras.prj (project) ---

Proj Title=2549
Current Plan=p01
Default Exp/Contr=0.3,0.1
English Units
Geom File=g01
Flow File=f01
Plan File=p01
Y Axis Title=Elevation
X Axis Title(PF)=Main Channel Distance
X Axis Title(XS)=Station
BEGIN DESCRIPTION:
RFD model 2549 exported to HEC-RAS
END DESCRIPTION:

--- 2549_ras.p01 (plan) ---

Plan Title=Plan 01
Program Version=4.10
Short Identifier=Plan 01
Geom File=g01
Flow File=f01
Subcritical Flow
Calc Critical at every XS
Secant Critical Depth

--- 2549_ras.f01 (steady flow) ---

Flow Title=Flow 01
Program Version=5.01
Number of Profiles= 6
Profile Names=10yr,25yr,50yr,100yr,100plus,500yr
River Rch & RM=2549,115,138096.9
  223.24  413.45  614.24  829.14 1210.55 2348.27
River Rch & RM=2549,115,137849.2
  312.64  579.11   860.7 1161.63 1695.98 3134.56
River Rch & RM=2549,115,137601.5
     335  620.65   922.6 1245.24 1818.06 3327.47
River Rch & RM=2549,115,137353.9
  337.56   625.4  929.69 1254.83 1832.06 3349.51
River Rch & RM=2549,115,136858.6
  346.39  641.87  954.29 1288.13 1880.68 3426.19
River Rch & RM=2549,115,136573.7
  380.11  704.96 1048.78 1416.33 2067.85 3720.43
River Rch & RM=2549,115,136363.3
  393.36  729.64 1085.63 1466.17  2140.6 3832.89
River Rch & RM=2549,115,136099.8
  404.79  751.01 1117.61 1509.52 2203.89  3930.8
River Rch & RM=2549,115,136009.4
  406.53  754.25 1122.45 1516.07 2213.47 3945.55
River Rch & RM=2549,115,135884.3
   408.6  758.12 1128.25 1523.93 2224.94 3963.22
River Rch & RM=2549,115,135600.8
  410.16  761.03 1132.59 1529.82 2233.53 3976.45
River Rch & RM=2549,115,135149.1
  412.76  765.88 1139.85 1539.64 2247.88 3998.47
River Rch & RM=2549,115,134762.9
  494.48  917.72 1366.24 1845.44 2694.34 4670.53
River Rch & RM=2549,115,134464.8
  496.98  922.39 1373.23  1854.9 2708.16  4691.2
River Rch & RM=2549,115,  134093
  509.83  946.36 1409.06  1903.4 2778.96 4796.77
River Rch & RM=2549,115,133772.4
  511.81  950.06  1414.6 1910.91 2789.93 4813.14
River Rch & RM=2549,115,133664.3
  537.37  997.94 1486.38 2008.33 2932.15 5025.35
River Rch & RM=2549,115,133504.4
  537.86  998.85 1487.75 2010.18 2934.86 5029.37
River Rch & RM=2549,115,133251.3
  542.24 1007.06 1500.04 2026.85 2959.21  5065.5
River Rch & RM=2549,115,133002.5
  546.45 1014.94 1511.86 2042.89 2982.61 5100.19
River Rch & RM=2549,115,132253.7
  557.62 1035.84 1543.16 2085.34  3044.6 5191.82
River Rch & RM=2549,115,131769.1
  599.72 1114.33 1660.49 2244.11  3276.4 5530.27
River Rch & RM=2549,115,131256.2
  601.79 1118.21  1666.3 2251.99  3287.9 5547.05
River Rch & RM=2549,115,  131057
  604.17 1122.66 1672.97 2261.04 3301.12 5566.37
River Rch & RM=2549,115,130736.8
  604.64 1123.55 1674.31 2262.85 3303.77 5570.23
River Rch & RM=2549,115,130425.8
     610  1133.6 1689.39 2283.33 3333.65 5613.93
River Rch & RM=2549,115,130055.2
  612.05 1137.44 1695.15 2291.15 3345.07 5630.61
River Rch & RM=2549,115,  129698
  664.22 1234.94  1841.1 2488.91 3633.81 6047.62
River Rch & RM=2549,115,129594.9
  664.69 1235.81 1842.41 2490.69  3636.4 6051.36
River Rch & RM=2549,115,  129160
  691.12 1285.34  1916.7 2591.52 3783.61 6262.99
River Rch & RM=2549,115,128725.1
  803.51  1496.7 2234.44 3023.59 4414.44 7161.58
River Rch & RM=2549,115,128324.8
  810.88 1510.54 2255.27 3051.91 4455.79  7219.8
River Rch & RM=2549,115,127934.3
  818.37 1524.64 2276.46 3080.73 4497.87 7278.99
River Rch & RM=2549,115,127420.3
  840.06 1565.43 2337.78 3164.12 4619.61 7449.72
River Rch & RM=2549,115,126985.3
  841.95 1568.99 2343.15 3171.41 4630.26 7464.64
River Rch & RM=2549,115,126944.5
 1842.62 3383.07 5006.95 6712.61 9800.4113899.48
River Rch & RM=2549,115,125986.9
 1890.38 3473.88 5144.48 6900.5810074.8514249.21
River Rch & RM=2549,115,124910.8
 1962.39 3610.94 5352.21 7184.6710489.6114775.92
River Rch & RM=2549,115,124414.5
 2072.98 3821.05 5670.33 7619.2911124.1615573.98
River Rch & RM=2549,115,123918.2
 2085.49 3844.91 5706.54 7668.8411196.5115664.99
River Rch & RM=2549,115,122925.6
 2102.03 3876.42 5754.33 7734.24   1129215784.87
River Rch & RM=2549,115,  122436
 2106.27  3884.5  5766.6 7751.0411316.5115815.64
River Rch & RM=2549,115,121030.4
13259.5321266.67 26034.631730.32 50400.948712.48
River Rch & RM=2549,115,120524.2
13270.9421291.5326074.7431789.7350495.2548838.66
River Rch & RM=2549,115,120433.7
13272.3721294.6326079.7631797.1550507.0448854.43
River Rch & RM=2549,115,120173.7
13273.18 21296.426082.6331801.3950513.7848863.45
River Rch & RM=2549,115,119117.3
13327.0321413.7126272.3132082.3650960.0749461.57
River Rch & RM=2549,115,118451.2
13329.7521419.6626281.9332096.6250982.7249491.98
River Rch & RM=2549,115,117610.1
13402.62 21578.726539.6532479.0751590.2250309.54
River Rch & RM=2549,115,116766.4
13419.4621615.5126599.3932567.8351731.2150499.81
River Rch & RM=2549,115,  115716
13443.2121667.4326683.71 32693.251930.3450768.87
River Rch & RM=2549,115,114412.2
13489.1721768.0126847.2132936.5452316.8751292.28
River Rch & RM=2549,115,113484.1
13507.2621807.6526911.7233032.6352469.4951499.36
River Rch & RM=2549,115,112191.3
13891.1122652.85   28296 35106.4 55763.556024.34
River Rch & RM=2549,115,111268.6
13992.0422876.4928665.0735663.0156647.6357256.66
River Rch & RM=2549,115,  110303
13995.96 22885.228679.4635684.7656682.1857304.96
River Rch & RM=2549,115,108870.5
15792.8326961.2135601.6746394.5873693.8182385.29
River Rch & RM=2549,115,107493.8
 15804.726988.7135649.5946470.3973814.2382571.54
River Rch & RM=2549,115,106363.2
15810.4527002.0435672.8146507.1473872.6182661.88
River Rch & RM=2549,115,105382.1
15937.15 27296.136186.1447320.7975165.0184668.81
River Rch & RM=2549,115,105055.4
15938.5527299.3436191.8247329.7975179.3184691.11
River Rch & RM=2549,115,104896.8
15939.5327301.6236195.79 47336.175189.3484706.72
River Rch & RM=2549,115,104040.6
15943.9227311.8336213.6647364.4775234.3984776.94
River Rch & RM=2549,115,102635.1
16266.2528063.7737534.5749469.7778578.4890032.95
River Rch & RM=2549,115,101636.2
 16270.828074.4337553.3749499.8378626.2390108.66
River Rch & RM=2549,115,100929.3
16389.6328353.0438045.7650288.7979879.4392101.19
River Rch & RM=2549,115,100088.8
16400.2428377.9438089.82 50359.579991.7592280.36
River Rch & RM=2549,115,99642.59
17169.8830200.1141348.6255636.4688373.74105917.9
River Rch & RM=2549,115,98668.64
17178.1430219.8141384.2155694.6188466.12  106071
River Rch & RM=2549,115,97207.71
17225.3130332.4841587.8756027.4888994.85106948.9
River Rch & RM=2549,115,95997.53
 17272.130444.35 41790.356358.7189520.98107824.4
River Rch & RM=2549,115,94285.86
17349.45 30629.542125.8956908.5690394.37109282.1
River Rch & RM=2549,115,92856.72
17361.9230659.3942180.1156997.4990535.63109518.4
River Rch & RM=2549,115,91321.57
17416.4530790.1342417.5357387.18 91154.6110555.4
River Rch & RM=2549,115,89903.09
17459.0730892.4142603.5157692.7591639.98111370.5
River Rch & RM=2549,115,89096.59
17678.6531420.8443567.4159281.0694162.88115633.6
River Rch & RM=2549,115, 88810.4
 17680.431425.0543575.1259293.79 94183.1115667.9
River Rch & RM=2549,115,87961.54
17688.5731444.7543611.1659353.3394277.67115828.6
River Rch & RM=2549,115,86906.32
17750.4531594.1143884.61 59805.494995.74117050.6
River Rch & RM=2549,115,86151.54
17756.2631608.1543910.3359847.9595063.34117165.8
River Rch & RM=2549,115,85957.76
17756.6531609.0943912.0659850.8295067.88117173.6
River Rch & RM=2549,115,85188.53
17761.3931620.5643933.0859885.5995123.12117267.7
River Rch & RM=2549,115,84015.29
17780.5831666.9144018.0560026.2195346.49117648.8
River Rch & RM=2549,115,81697.67
17795.2131702.2944082.9360133.6395517.12117940.1
River Rch & RM=2549,115, 80060.1
19179.8335095.3550410.4270766.39112406.3147728.2
River Rch & RM=2549,115,78488.46
19188.9235117.9450453.2270839.34112522.2147938.8
River Rch & RM=2549,115,75409.21
19430.1435718.3251594.1172788.52115618.3153598.6
River Rch & RM=2549,115,72980.03
19446.3635758.7951671.2372920.63115828.2153984.3
River Rch & RM=2549,115,70174.35
19497.0635885.3851912.6573334.41116485.4155194.2
River Rch & RM=2549,115,68423.59
19528.7435964.5252063.7373593.57116897.1155953.3
River Rch & RM=2549,115,68278.52
19529.9835967.6252069.6573603.71116913.2  155983
River Rch & RM=2549,115,67652.57
19534.0235977.7152088.9273636.79116965.7  156080
River Rch & RM=2549,115,65036.54
19592.56 36124.152368.6874117.15117728.7  157490
River Rch & RM=2549,115,59745.55
21271.7840388.6360673.3188617.33  140761  201644
River Rch & RM=2549,115,53092.78
 21323.4 40521.760937.1489085.31141504.4203118.3
River Rch & RM=2549,115,50902.63
21328.6140535.1360963.7889132.58141579.5203267.4
River Rch & RM=2549,115,50782.84
21328.8840535.8260965.1589135.02141583.3203275.1
River Rch & RM=2549,115,47268.87
21364.9740628.9461149.9789463.14142104.5204310.8
River Rch & RM=2549,115,41444.95
21402.5840726.0261342.7989805.68142648.6205393.6
River Rch & RM=2549,115,38819.58
21437.4440816.0661521.7490123.82  143154206400.7
River Rch & RM=2549,115,34883.56
21452.2440854.2961597.7790259.03143368.7206829.1
River Rch & RM=2549,115,32103.33
23669.1346686.8973454.11111762.2177524.6277954.4
River Rch & RM=2549,115,26885.16
26138.3153416.46 87731.8138655.3  220242  374536
River Rch & RM=2549,115,23973.21
26150.7153450.8487806.28138798.2  220469375070.1
River Rch & RM=2549,115,22226.04
26184.1453543.58 88007.3  139184221081.8376512.9
River Rch & RM=2549,115,19886.62
26189.6753558.9588040.63  139248221183.5376752.3
River Rch & RM=2549,115,19488.46
26190.2253560.4888043.95139254.3221193.5376776.2
River Rch & RM=2549,115,13340.64
26327.9153942.9588874.22  140850223728.2382760.8
River Rch & RM=2549,115,8994.717
 26712.855015.8591213.31145362.6  230896399825.7
River Rch & RM=2549,115,3711.431
26783.84 55214.591648.01  146204232232.5403030.2
River Rch & RM=2549,115,       0
26806.6455278.29 91787.7146474.5232662.2404062.2
Boundary for River Rch & Prof#=2549,115,1
Up Type= 0
Dn Type= 2
Boundary for River Rch & Prof#=2549,115,2
Up Type= 0
Dn Type= 2
Boundary for River Rch & Prof#=2549,115,2
Up Type= 0
Dn Type= 2
Boundary for River Rch & Prof#=2549,115,2
Up Type= 0
Dn Type= 2
Boundary for River Rch & Prof#=2549,115,2
Up Type= 0
Dn Type= 2
Boundary for River Rch & Prof#=2549,115,2
Up Type= 0
Dn Type= 2

--- 2549_ras.g01 (geometry) ---

Geom Title=2549
Program Version=4.10

River Reach=2549,115
Reach XY= 30
484912.646968126738376.227618709483845.285856962740449.144285381
480290.598356962742486.383868709476369.593702197742895.117229015
474460.956549406741551.801256761466191.642313302741093.901951268
464551.588690728742661.028130248459213.336375892742688.684380233
450312.426695228747425.871933252444807.350820154748302.156650603
444614.480449826752343.007345065442168.299894333752161.930956185
442349.313537031753397.644083485440432.204518259753864.773226827
439607.292949885753041.264289513433711.702671975756707.201790005
433339.584616512755621.055956185  429279.9665609755869.701789543
 429133.37624833754848.931048602425677.605449855756075.535122827
422262.640172005755538.903178394415559.525018483 758879.39737688
412430.636129588 762426.13348794412897.917949796765292.625400901
410575.950357169765493.296696931 410149.58438307767221.995732889
406818.421095341768729.157261059405877.666127235771732.629493207
403150.568412721772554.485933095396665.535426587778201.003294274

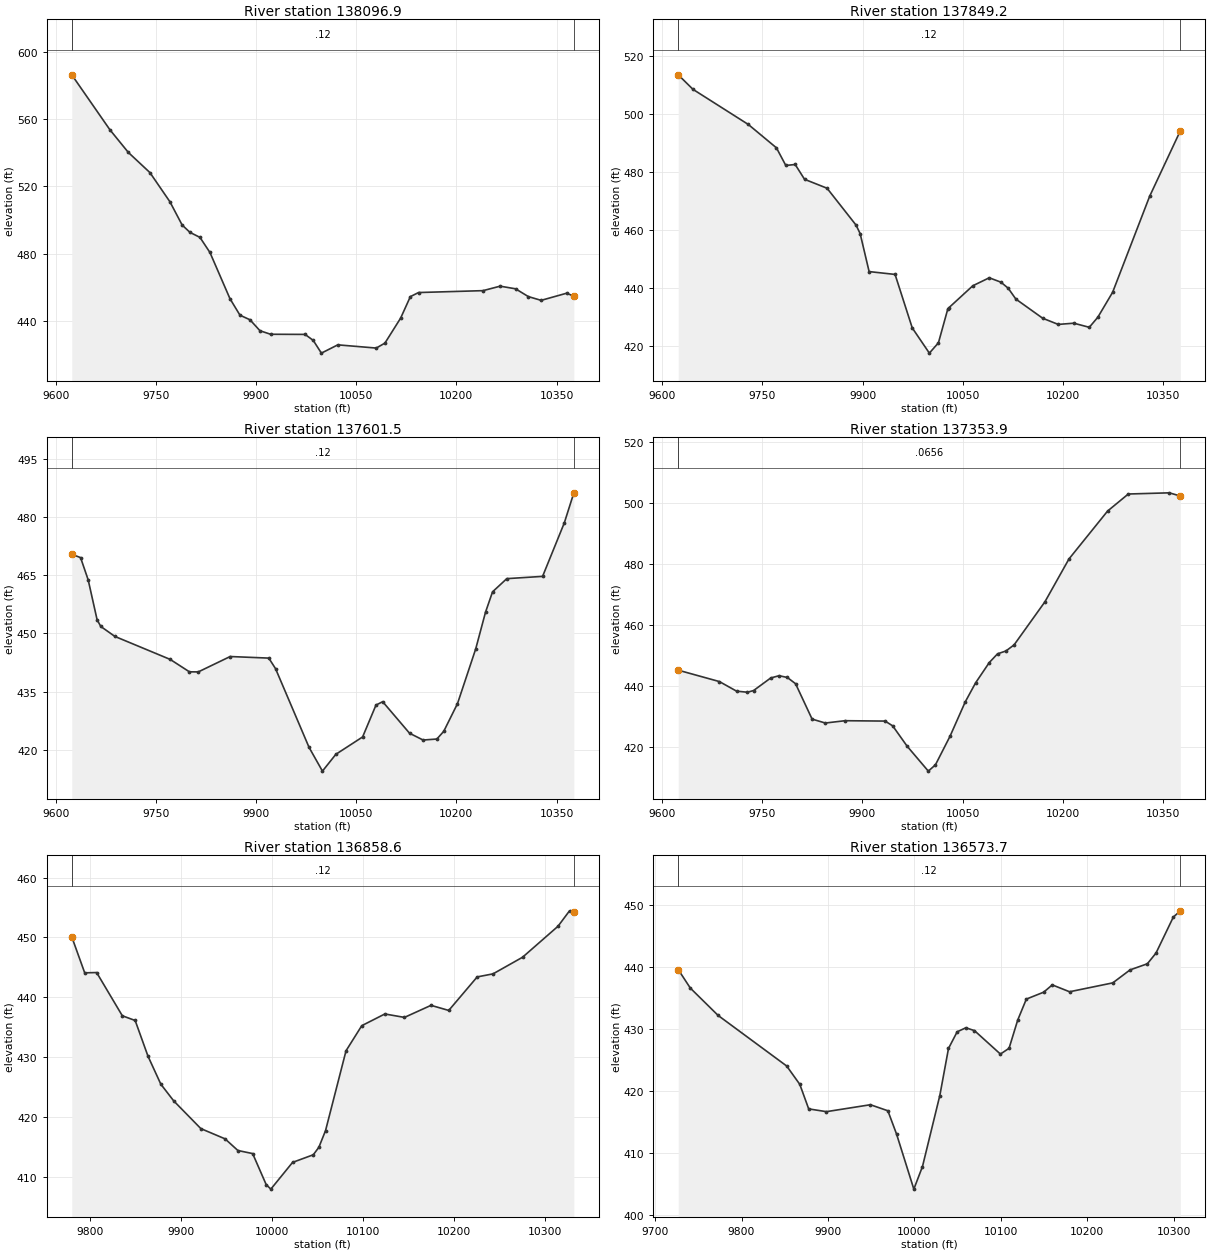
Type RM Length L Ch R = 1 ,138096.9,247.652400,247.652400,247.652400
XS GIS Cut Line= 6
484666.892801259738091.898047848484855.201342038738302.037065923
484927.077290221738398.010658759484954.396234402738427.319604602
485049.378730723738499.319261581485210.636954853738600.576214425
#Sta/Elev= 30
9624.021586.27179681.123553.61029708.753 540.124 9741.06528.14489771.028510.7913
9789.319496.97499800.997492.60919815.981489.62569830.966480.63469860.934453.1776
9875.919443.35729890.903 440.6399905.887434.11149921.803 432.0199973.438431.9336
9985.646428.36639997.855420.803410022.44425.725310079.99423.813410092.97426.7498
10116.56 441.64810131.07454.391310143.33456.8263 10239.9457.951310265.55460.6119
10288.62459.047910307.77454.418710326.93452.181110365.24456.441910375.92454.6112
#Mann= 3 , 0 , 0
9624.021    0.12       09624.021    0.12       010375.92    0.12       0
#XS Ineff= 2 , 0
       0                               0
Bank Sta=9624.021,10375.92
Exp/Cntr=0.3,0.1

Type RM Length L Ch R = 1 ,137849.2,247.652400,247.652400,247.652400
XS GIS Cut Line= 6
484529.779637492738299.102417619484705.060452305738479.411211337
 484788.69928599  738579.3850103484831.299906843738620.535788894
484904.567821049738667.432298128485106.502959834738763.610422387
#Sta/Elev= 30
9624.035513.46159646.142508.45139729.016496.33299771.107488.27869785.137482.1957
9799.168482.53389813.198 477.424 9846.91474.34319890.389461.60619896.457458.6955
9909.895445.59269948.766444.60959974.485426.167810000.12417.463810013.71421.0274
10027.64432.622810029.32433.114910065.16440.698310089.82443.452410107.32441.9348
10118.15439.860610129.69436.105810169.87429.492810193.12427.368810216.38427.7888
10239.63426.371210252.43429.848310274.59438.459410329.97 471.54510375.94494.1367
#Mann= 3 , 0 , 0
9624.035    0.12       09624.035    0.12       010375.94    0.12       0
#XS Ineff= 2 , 0
       0                10082.49       0
Bank Sta=9624.035,10375.94
Exp/Cntr=0.3,0.1

Type RM Length L Ch R = 1 ,137601.5,247.652400,247.652400,247.652400
XS GIS Cut Line= 6
484376.280656871738556.529116818484493.324184279738685.203136103
484570.936534721738740.530352904484625.523643164738752.194375064
484821.814806196738753.673090795 485038.14458024738827.536098544
#Sta/Elev= 30
9624.141470.43419637.336469.56059648.749463.79799662.072453.52429667.603 451.796
9688.719 449.2229771.545443.28899800.336440.08429813.582440.06879861.336444.0359
9919.155443.62879929.276440.90279979.455420.58939999.502414.460510019.57418.8018
10059.66423.284810079.66431.503810089.69432.379110129.93424.239110150.23422.4856
10170.83422.745810181.12424.727810201.72431.879710229.03446.023310243.69455.4859
10254.21 460.73210275.55464.135610329.14464.719810361.68478.533810375.94486.2822
#Mann= 3 , 0 , 0
9624.141    0.12       09624.141    0.12       010375.94    0.12       0
#XS Ineff= 2 , 0
       0                10084.91       0
Bank Sta=9624.141,10375.94
Exp/Cntr=0.3,0.1

Type RM Length L Ch R = 1 ,137353.9,495.304700,495.304700,495.304700
XS GIS Cut Line= 6
484420.333405009 738636.79224331484594.890135814738865.907627141
484643.577522704738979.832725548484684.006941137739041.406566109
484770.976701438739135.977261349484874.968196602739225.497727398
#Sta/Elev= 30
9624.085445.10679685.773441.35649711.365438.21499727.729437.84769736.958438.4157
 9762.55442.53799775.082443.28749787.445442.71189799.807440.64739824.533429.0141
9844.348427.72439873.983428.48999933.883428.36439945.244426.78629966.767420.1247
 9998.58411.905210009.24413.976410031.08423.379310053.92434.699810069.37440.9397
10089.89447.625310102.21450.480410114.83451.425210127.02453.426710173.18467.5928
10209.17481.682710267.02497.441710298.04503.0485 10359.4503.437410375.92502.3881
#Mann= 3 , 0 , 0
9624.085  0.0656       09624.085  0.0656       010375.92  0.0656       0
#XS Ineff= 2 , 0
       0                10081.05       0
Bank Sta=9624.085,10375.92
Exp/Cntr=0.3,0.1

Type RM Length L Ch R = 1 ,136858.6,284.841100,284.841100,284.841100
XS GIS Cut Line= 6
484135.109057733 738805.31865457484271.713635683738940.460103408
484302.694149911738968.300175831484314.408842504738981.335435793
484357.774178177739020.436956376484548.746400386739169.742511943
#Sta/Elev= 30
9780.084450.09389794.314444.07849807.443444.12769835.685436.90349849.806436.1156
9863.927 430.1419878.047425.46719892.168422.68569922.028418.04979948.651416.3388
9962.772414.38949979.009413.87579993.891  408.69    9999 407.93510022.91412.4026
10045.69413.676310051.84414.931410059.16417.7148 10081.7431.0576   10099435.2474
10124.38437.205110145.94436.632510175.16 438.64810194.65437.795210225.93 443.398
10243.35443.907510275.83446.686310314.78451.858910327.48454.441510332.23454.2505
#Mann= 3 , 0 , 0
9780.084    0.12       09780.084    0.12       010332.23    0.12       0
#XS Ineff= 2 , 0
       0 9928.41                       0
Bank Sta=9780.084,10332.23
Exp/Cntr=0.3,0.1

Type RM Length L Ch R = 1 ,136573.7,210.463700,210.463700,210.463700
XS GIS Cut Line= 6
483961.979944855739141.982310489 484080.21062693739183.838373348
484148.509757966739199.787066624484198.784346908739206.749127686
484243.445898533  739208.5630541484533.121400386739200.992511943
#Sta/Elev= 30
9726.768439.59779740.757436.6161 9772.99432.19729852.247424.05639867.434421.0956
9877.703417.14319898.241416.69559949.127417.81279969.317416.83859979.359413.0908
9999.375 404.20810009.38407.855410029.44419.297510039.47426.884610049.51429.5679
10059.54430.218110069.54429.758310099.55425.979210109.55426.910110119.55431.4556
10129.55434.842410149.56435.953210159.56437.130610179.56436.023510229.57437.4566
10249.57439.550110269.57440.534510279.57442.258510299.58448.0529 10307.7  449.07
#Mann= 3 , 0 , 0
9726.768    0.12       09726.768    0.12       0 10307.7    0.12       0
#XS Ineff= 2 , 0
       09896.324                       0
Bank Sta=9726.768,10307.7
Exp/Cntr=0.3,0.1

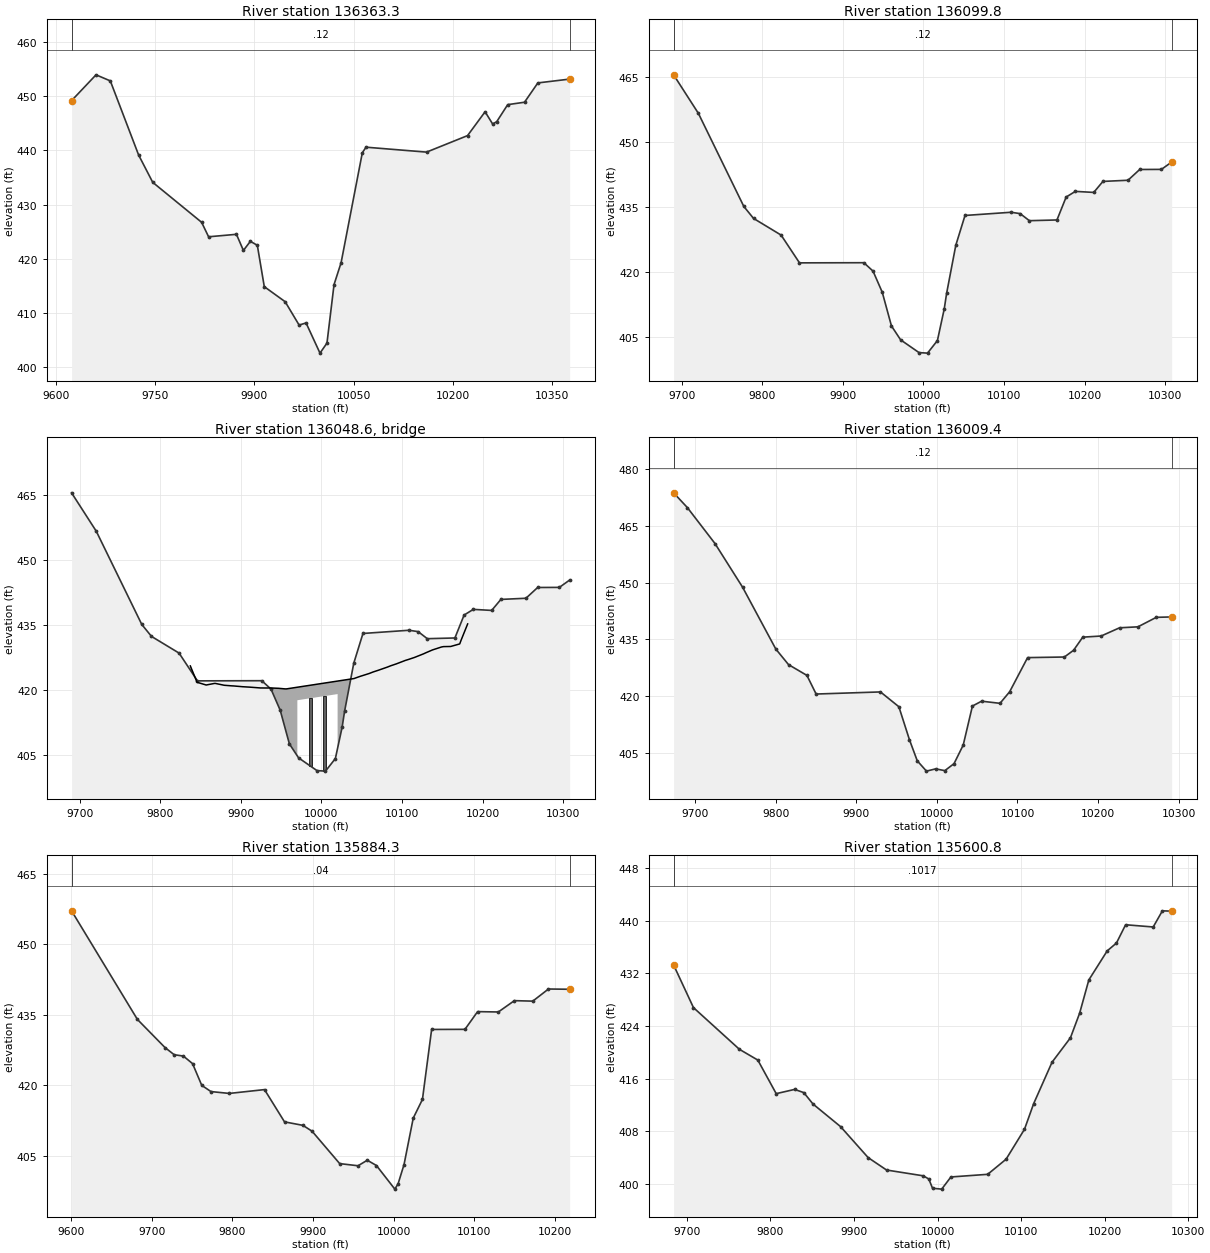
Type RM Length L Ch R = 1 ,136363.3,263.533500,263.533500,263.533500
XS GIS Cut Line= 6
483830.789519492739288.278072217483961.218290044739338.607594354
484191.125741828739412.977726883484294.320891272739451.434769598
 484413.42917033739505.760809731484527.170048784739567.488265833
#Sta/Elev= 30
9624.024449.16289660.942453.92589682.524452.80689725.284439.12759746.579434.0962
9820.381426.72599830.893424.05619872.939424.51319883.451421.53899893.962423.2187
9904.474422.48469914.986414.85789946.521412.07859967.544407.77659978.055 408.167
9999.078402.600110009.62404.452410020.29415.242310030.96419.281910062.98439.5466
10068.55440.579510159.93 439.67210221.85442.715410248.34 447.11210259.72444.8625
10265.93445.289110282.48448.426610307.86448.871210327.99452.434310375.97453.1373
#Mann= 3 , 0 , 0
9624.024    0.12       09624.024    0.12       010375.97    0.12       0
#XS Ineff= 2 , 0
       09879.122                       0
Bank Sta=9624.024,10375.97
Exp/Cntr=0.3,0.1

Type RM Length L Ch R = 1 ,136099.8,90.370800,90.370800,90.370800
XS GIS Cut Line= 2
483788.101177583739492.980381062 484329.76784427739791.157464405
#Sta/Elev= 30
9689.835 465.536 9720.54456.67139776.969435.2062 9789.03432.44499823.275428.5983
9846.105422.19629926.011422.23149937.426 420.2879948.841415.42579960.256407.6639
9971.671404.44769994.501401.512510005.07401.390910017.33404.288610025.81411.5892
10028.75415.169410040.16426.257710051.58433.121110108.75433.859310120.07433.5451
10131.48431.916910165.73432.081810177.14437.365110188.56438.671110211.39438.4326
 10222.8440.968510253.91 441.23610268.46 443.71710295.38  443.7410308.15445.4295
#Mann= 3 , 0 , 0
9689.835    0.12       09689.835    0.12       010308.15    0.12       0
#XS Ineff= 2 , 0
       0                               0
Bank Sta=9689.835,10308.15
Exp/Cntr=0.3,0.1

Type RM Length L Ch R = 3 ,136048.6,,,
BEGIN DESCRIPTION:
END DESCRIPTION:
Bridge Culvert--1,0,-1,-1, 0
Deck Dist Width WeirC Skew NumUp NumDn MinLoCord MaxHiCord MaxSubmerge Is_Ogee
16.185400,58.000000,2.6,0, 43, 43, , , 0.95, 0, 0,0,,
 9837.27 9845.24 9845.67 9856.92 9867.12 9868.16 9879.40 9889.01 9890.64 9901.88
 9910.90 9913.12 9924.37 9932.79 9935.61 9946.85 9954.68 9956.37 9970.13 9970.13
10020.1310020.1310040.5410042.2310048.0310059.2710064.1210070.5110081.7510086.00
10092.9910104.2410107.8910115.4810126.7210129.7810137.9610149.2010151.6710160.45
10171.6910173.5610181.56
  425.64  422.05  421.87  421.24  421.60  421.61  421.18  421.04  421.03  420.85
  420.75  420.72  420.56  420.55  420.57  420.48  420.35  420.34  420.73  420.73
  422.15  422.15  422.73  422.85  423.23  423.89  424.24  424.63  425.36  425.67
  426.11  426.91  427.12  427.59  428.42  428.68  429.33  430.01  430.09  430.12
  430.71  431.64  435.32
 -574.36 -577.95 -578.13 -578.76 -578.40 -578.39 -578.82 -578.96 -578.97 -579.15
 -579.25 -579.28 -579.44 -579.45 -579.43 -579.52 -579.65 -579.66 -579.27  417.73
  419.15 -577.85 -577.27 -577.15 -576.77 -576.11 -575.76 -575.37 -574.64 -574.33
 -573.89 -573.09 -572.88 -572.41 -571.58 -571.32 -570.67 -569.99 -569.91 -569.88
 -569.29 -568.36 -564.68
 9837.27 9845.24 9845.67 9856.92 9867.12 9868.16 9879.40 9889.01 9890.64 9901.88
 9910.90 9913.12 9924.37 9932.79 9935.61 9946.85 9954.68 9956.37 9972.76 9972.76
10022.7610022.7610040.5410042.2310048.0310059.2710064.1210070.5110081.7510086.00
10092.9910104.2410107.8910115.4810126.7210129.7810137.9610149.2010151.6710160.45
10171.6910173.5610181.56
  425.64  422.05  421.87  421.24  421.60  421.61  421.18  421.04  421.03  420.85
  420.75  420.72  420.56  420.55  420.57  420.48  420.35  420.34  420.80  420.80
  422.22  422.22  422.73  422.85  423.23  423.89  424.24  424.63  425.36  425.67
  426.11  426.91  427.12  427.59  428.42  428.68  429.33  430.01  430.09  430.12
  430.71  431.64  435.32
 -574.36 -577.95 -578.13 -578.76 -578.40 -578.39 -578.82 -578.96 -578.97 -579.15
 -579.25 -579.28 -579.44 -579.45 -579.43 -579.52 -579.65 -579.66 -579.20  417.80
  419.22 -577.78 -577.27 -577.15 -576.77 -576.11 -575.76 -575.37 -574.64 -574.33
 -573.89 -573.09 -572.88 -572.41 -571.58 -571.32 -570.67 -569.99 -569.91 -569.88
 -569.29 -568.36 -564.68
Pier Skew, UpSta & Num, DnSta & Num=  ,9986.30, 2 ,9988.93, 2 , 0 , 0 , 0 ,,
    3.00    3.00
 -578.81  421.19
    3.00    3.00
 -578.74  421.26
Pier Skew, UpSta & Num, DnSta & Num=  ,10003.96, 2 ,10006.59, 2 , 0 , 0 , 0 ,,
    3.00    3.00
 -578.31  421.69
    3.00    3.00
 -578.24  421.76
BR Coef=-1 , 0 , 0 ,, 0 ,,,0.8,0,1,0,
WSPro=,,,, 1 ,,,, 0 ,,,, 0 ,,,,-1 ,-1 ,-1 , 0 , 0 , 0 , 0 , 0
BC Design=,, 0 ,, 0 ,,,,,,

Type RM Length L Ch R = 1 ,136009.4,125.099900,125.099900,125.099900
XS GIS Cut Line= 2
483730.028260916739563.813714395484271.694927603739861.990797738
#Sta/Elev= 30
9673.132473.72629690.222469.81539724.467460.32719758.712 448.7869800.011 432.417
9815.788428.30249838.618425.45289850.033420.52499929.938421.08189952.768417.1677
9965.902408.44119975.598402.87229987.013  400.149998.428400.737210009.84400.2711
10021.26402.118410032.67407.035510044.09417.3547 10055.5418.632810078.33418.0666
10090.32421.130210112.58430.154610158.24 430.31310169.65432.091710181.07435.5641
 10203.9 435.86510226.73438.038610249.56438.293710272.39 440.80610291.45440.9114
#Mann= 3 , 0 , 0
9673.132    0.12       09673.132    0.12       010291.45    0.12       0
#XS Ineff= 2 , 0
       0                               0
Bank Sta=9673.132,10291.45
Exp/Cntr=0.3,0.1

Type RM Length L Ch R = 1 ,135884.3,283.487000,283.487000,283.487000
XS GIS Cut Line= 2
483683.413677583739649.490797728 484225.08034427739947.667881072
#Sta/Elev= 30
9600.216 457.1469681.932434.04379716.177 428.0629727.592426.53199739.007426.2446
9750.422424.63659761.837420.01489773.252418.69059796.082418.29519839.741419.1098
9864.572412.24419887.402411.50439898.817410.25169933.063 403.3649955.893402.9047
9967.308404.08379978.723402.955910001.55397.933510005.63399.090410012.97403.1721
10024.38413.0404 10035.8417.014910047.21431.906510088.58431.931210104.29   435.7
10130.05435.625410149.95438.035310172.78437.930610192.26440.512210218.53440.4576
#Mann= 3 , 0 , 0
9600.216    0.04       09600.216    0.04       010218.53    0.04       0
#XS Ineff= 2 , 0
       0                               0
Bank Sta=9600.216,10218.53
Exp/Cntr=0.3,0.1

Type RM Length L Ch R = 1 ,135600.8,451.686000,451.686000,451.686000
XS GIS Cut Line= 2
483553.431196988739887.569697738484095.097863674 740136.26761438
#Sta/Elev= 30
9684.181433.24549707.915426.77439762.933420.4364 9784.94 418.8039806.948413.7035
9828.955414.34579839.959413.86259850.962412.12959883.973408.69499916.984403.9884
9938.992402.10359983.006401.22019989.582400.7356 9994.01399.333910005.01399.2011
10016.02401.048510060.03401.449610082.04403.745510104.05408.287410115.05412.1848
10137.06418.480810159.06422.185510170.07425.925310181.07430.972910203.08435.3934
10214.08436.569710225.09439.3566 10258.1 439.018 10269.1441.471610280.21441.4216
#Mann= 3 , 0 , 0
9684.181  0.1017       09684.181  0.1017       010280.21  0.1017       0
#XS Ineff= 2 , 0
       0                               0
Bank Sta=9684.181,10280.21
Exp/Cntr=0.3,0.1

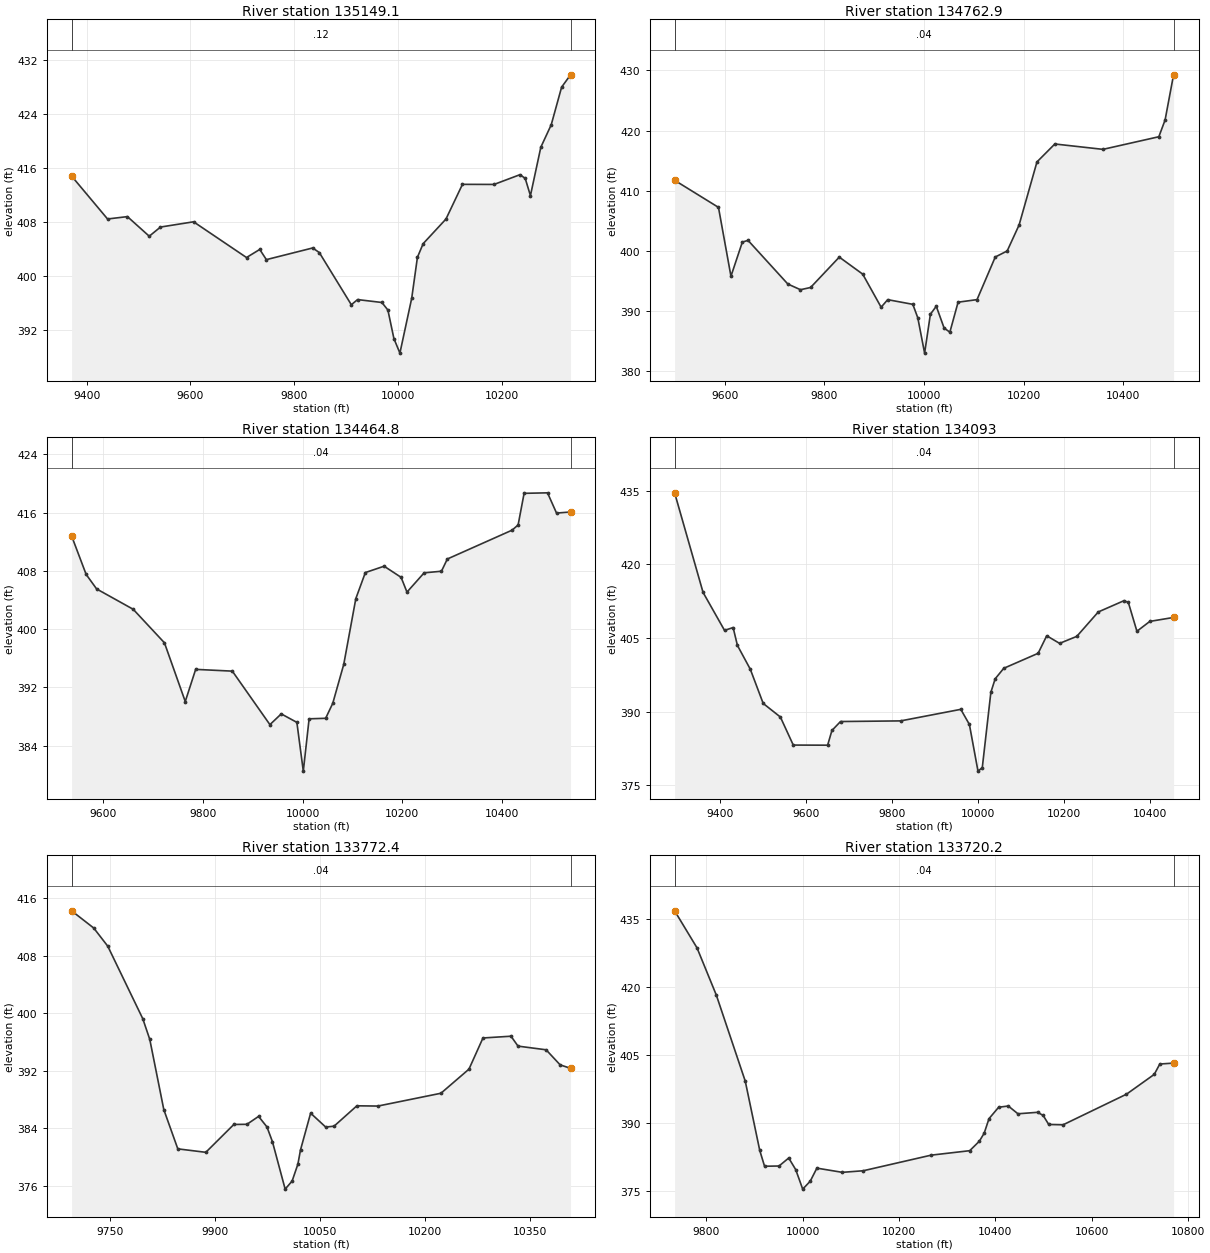
Type RM Length L Ch R = 1 ,135149.1,386.207100,386.207100,386.207100
XS GIS Cut Line= 6
483370.675943255740042.146491796483766.012814671740355.039126366
483887.736147463740430.456368938483948.987416238740459.297754765
484010.925533831 740478.50722836484192.199380755740468.242411956
#Sta/Elev= 30
9371.076414.81999440.355408.47539478.615408.82649520.694405.9291 9542.38407.2831
9606.145408.0594 9708.17402.77679733.676403.97189746.429 402.465  9835.7404.1906
9848.453403.51289910.186395.79479922.238396.55819969.102396.12819980.666395.0098
 9992.23390.801210003.79388.639610026.55396.7462 10037.6402.817610048.66 404.831
10092.61408.470110124.38413.597510185.27413.585310235.35415.031210245.36414.4714
10255.38411.927510275.41419.086410295.44422.401810315.48427.9709 10332.7429.7931
#Mann= 3 , 0 , 0
9371.076    0.12       09371.076    0.12       0 10332.7    0.12       0
#XS Ineff= 2 , 0
       0                               0
Bank Sta=9371.076,10332.7
Exp/Cntr=0.3,0.1

Type RM Length L Ch R = 1 ,134762.9,298.075300,298.075300,298.075300
XS GIS Cut Line= 6
483300.800874532740167.171829736483493.170519845740503.119536847
483537.239754042740554.982611568483601.844322909740600.469368003
483637.211046073740637.759942928483875.354384172740978.450677394
#Sta/Elev= 30
9499.093411.76039587.139407.26299612.206395.82119635.066401.49449646.485401.7815
9726.416394.52939751.784393.58449772.091393.95489829.734399.00049876.746 396.173
9913.756 390.6779926.905391.93269977.379391.15589987.365 388.91710001.04383.0504
10012.68389.514610024.47 390.837 10040.2387.219310051.77386.529810068.26391.5124
10106.29391.936410142.93 399.01910166.85400.020810190.78404.339210226.66414.8137
10262.55417.792610359.16416.899710471.38418.995810483.91421.773410500.93429.2804
#Mann= 3 , 0 , 0
9499.093    0.04       09499.093    0.04       010500.93    0.04       0
#XS Ineff= 2 , 0
       09861.789        10076.55       0
Bank Sta=9499.093,10500.93
Exp/Cntr=0.3,0.1

Type RM Length L Ch R = 1 ,134464.8,371.786500,371.786500,371.786500
XS GIS Cut Line= 6
483145.993502444740237.258490539483233.659163587740519.060743297
483280.329473956740635.871352923483344.432136578740743.670345169
483436.654097065740909.766623671483580.558730059741132.741509461
#Sta/Elev= 30
9536.019412.79369565.208407.51419586.251405.51959659.742402.72349722.432398.1209
9764.226390.05669785.122394.4727 9858.78394.23019934.234386.88229957.005388.3579
9988.358 387.19410001.28380.497510012.95387.682310046.15387.753810060.44389.8132
10082.52395.166910106.75404.192410125.88407.768810163.55408.642110197.65407.1137
10209.46405.085810243.89407.7311 10278.7407.9509 10290.5409.630610420.65413.5957
10432.65414.309510444.65418.650410491.68418.719610509.77  415.9410537.93416.0869
#Mann= 3 , 0 , 0
9536.019    0.04       09536.019    0.04       010537.93    0.04       0
#XS Ineff= 2 , 0
       09886.892                       0
Bank Sta=9536.019,10537.93
Exp/Cntr=0.3,0.1

Type RM Length L Ch R = 1 ,  134093,320.638400,320.638400,320.638400
XS GIS Cut Line= 2
483011.300943255740208.813158482483032.134276569741370.271491796
#Sta/Elev= 30
9293.784434.59859359.982414.2992 9409.99406.55839429.993407.13239439.995403.4923
9469.999398.63149500.004391.66339540.011388.89339570.016 383.1769650.028383.1521
 9660.03386.15389680.033387.97499820.056388.10529960.078390.46039980.081387.3804
10000.08377.864210010.09378.569310030.09393.941110040.09396.682710060.09398.8263
10140.11401.883610160.11405.458610190.12403.909510230.12405.335110280.13410.3118
10340.14412.615510350.14412.254110370.14406.375710400.15408.387610455.43409.1933
#Mann= 3 , 0 , 0
9293.784    0.04       09293.784    0.04       010455.43    0.04       0
#XS Ineff= 2 , 0
       09767.897         10077.9       0
Bank Sta=9293.784,10455.43
Exp/Cntr=0.3,0.1

Type RM Length L Ch R = 1 ,133772.4,52.156000,52.156000,52.156000
XS GIS Cut Line= 5
482920.809045106740373.385641098482923.656891435740607.969003275
482837.936405331740738.177336618482834.681197107740966.041919947
482841.470427603741059.804597303
#Sta/Elev= 30
9695.504414.26959727.121 411.8739747.122409.35119797.126399.26019807.126396.3781
9827.128 386.6219847.129381.15799887.132380.67819927.135384.55269945.848384.5731
9962.467385.6745 9974.44384.2055 9982.22382.162410000.41 375.55710010.36376.6825
10018.59379.032810022.33 381.01610036.78386.123210058.25384.193410070.22384.3123
10102.82387.147710132.82387.111810222.83388.893510262.84392.245710282.84396.5831
10322.87396.827710332.89395.4498   10373394.938510393.05392.839610407.89392.3628
#Mann= 3 , 0 , 0
9695.504    0.04       09695.504    0.04       010407.89    0.04       0
#XS Ineff= 2 , 0
       09951.903        10054.56       0
Bank Sta=9695.504,10407.89
Exp/Cntr=0.3,0.1

Type RM Length L Ch R = 1 ,133720.2,55.957100,55.957100,55.957100
XS GIS Cut Line= 6
482867.397110611740368.562559873482877.578452736740604.753247797
482804.661786079740676.628247783  482779.6200158740738.615694329
482765.731126845741079.761527672482908.960293531741329.761527672
#Sta/Elev= 30
9734.303436.81879780.784428.63329820.821418.21479880.877399.19989910.905383.9188
9920.914380.41249950.942380.46569971.071 382.2319985.577379.664710000.08375.3583
10015.69377.108210029.49379.995310082.23379.0663 10125.7379.416410266.55382.8597
10346.62 383.84710366.63385.942810376.64387.710710386.65390.921210406.67393.4463
10426.68393.7143 10446.7391.996910487.53392.325110499.05 391.62610510.58389.6329
10540.37389.562910671.92396.321810729.55400.698510741.07402.986910769.61403.1885
#Mann= 3 , 0 , 0
9734.303    0.04       09734.303    0.04       010769.61    0.04       0
#XS Ineff= 2 , 0
       09970.668         10052.8       0
Bank Sta=9734.303,10769.61
Exp/Cntr=0.3,0.1

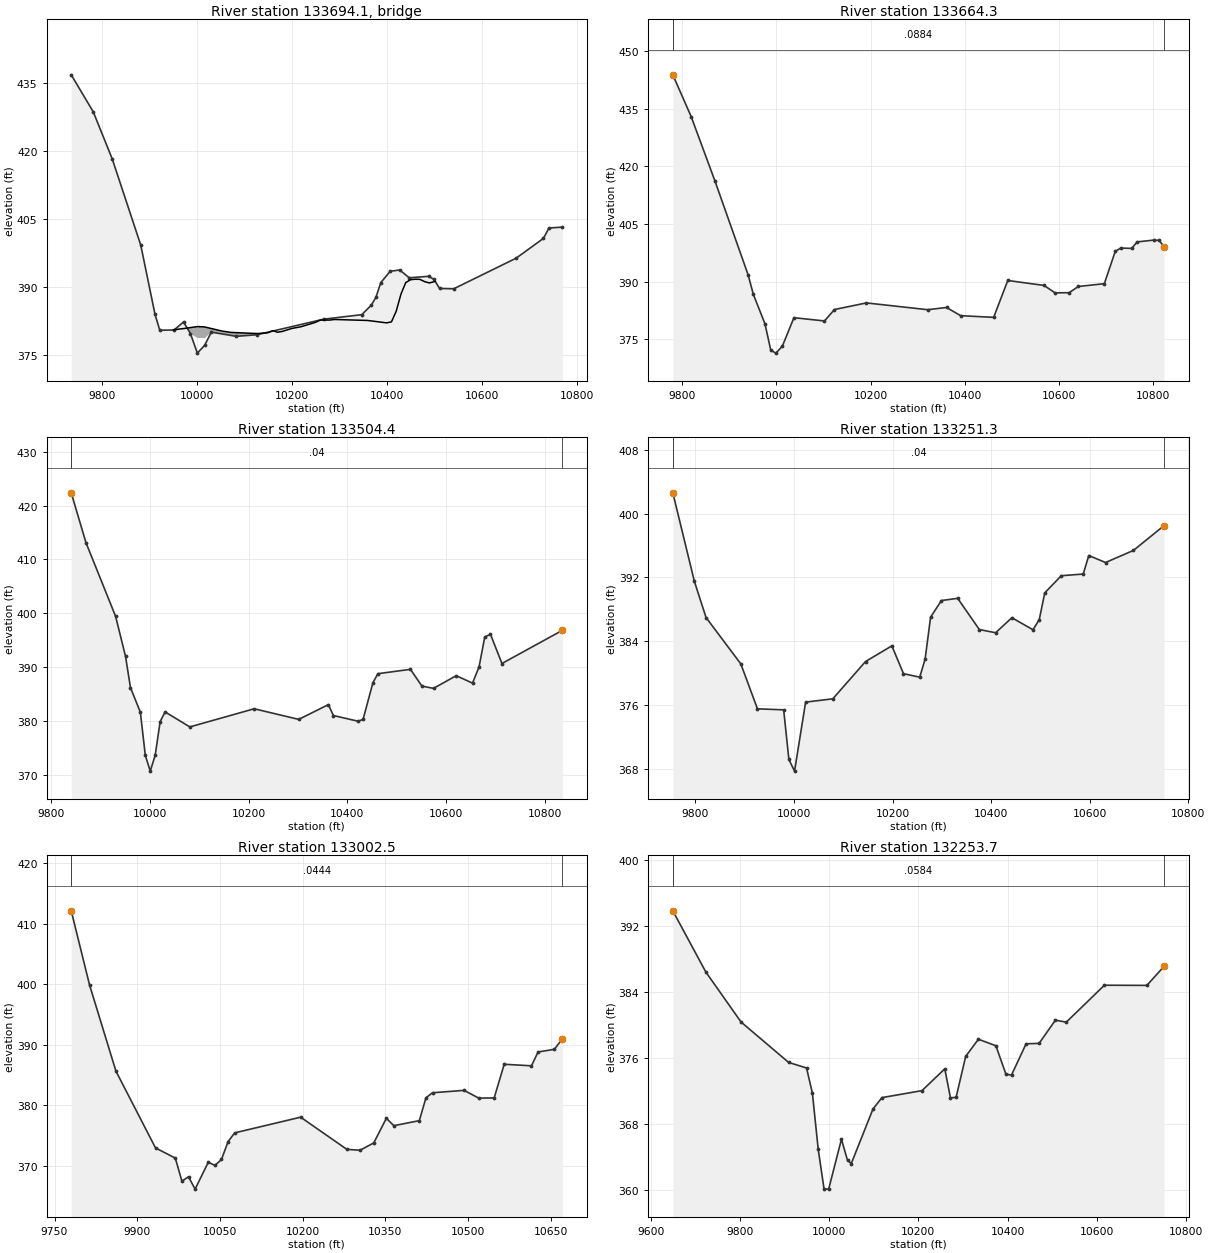
Type RM Length L Ch R = 3 ,133694.1,,,
BEGIN DESCRIPTION:
END DESCRIPTION:
Bridge Culvert--1,0,-1,-1, 0
Deck Dist Width WeirC Skew NumUp NumDn MinLoCord MaxHiCord MaxSubmerge Is_Ogee
14.748550,26.460000,2.6,0, 32, 32, , , 0.95, 0, 0,0,,
 9949.67 9971.80 9971.8010000.1910014.4810038.1610038.1610052.2010070.7710126.95
10149.0010159.0110169.0210179.0210199.0410219.0510249.0710259.0810279.0910289.10
10359.1410399.1710409.1810419.1810429.1910439.2010449.2010459.2110469.2210479.22
10489.2310501.70
  380.51  380.79  380.79  381.22  381.16  380.58  380.58  380.23  379.94  379.68
  379.86  380.33  379.97  380.15  380.80  381.20  382.15  382.65  382.66  382.79
  382.57  382.04  382.26  384.60  388.38  390.92  391.57  391.68  391.65  391.14
  390.86  391.20
 -619.49 -619.21  378.29  378.72  378.66  378.08 -619.42 -619.77 -620.06 -620.32
 -620.14 -619.67 -620.03 -619.85 -619.20 -618.80 -617.85 -617.35 -617.34 -617.21
 -617.43 -617.96 -617.74 -615.40 -611.62 -609.08 -608.43 -608.32 -608.35 -608.86
 -609.14 -608.80
 9949.67 9968.98 9968.9810000.1910014.4810035.3410035.3410052.2010070.7710126.95
10149.0010159.0110169.0210179.0210199.0410219.0510249.0710259.0810279.0910289.10
10359.1410399.1710409.1810419.1810429.1910439.2010449.2010459.2110469.2210479.22
10489.2310501.70
  380.51  380.73  380.73  381.22  381.16  380.66  380.66  380.23  379.94  379.68
  379.86  380.33  379.97  380.15  380.80  381.20  382.15  382.65  382.66  382.79
  382.57  382.04  382.26  384.60  388.38  390.92  391.57  391.68  391.65  391.14
  390.86  391.20
 -619.49 -619.27  378.23  378.72  378.66  378.16 -619.34 -619.77 -620.06 -620.32
 -620.14 -619.67 -620.03 -619.85 -619.20 -618.80 -617.85 -617.35 -617.34 -617.21
 -617.43 -617.96 -617.74 -615.40 -611.62 -609.08 -608.43 -608.32 -608.35 -608.86
 -609.14 -608.80
BR Coef=-1 , 0 , 0 ,, 0 ,,,0.8,0,1,0,
WSPro=,,,, 1 ,,,, 0 ,,,, 0 ,,,,-1 ,-1 ,-1 , 0 , 0 , 0 , 0 , 0
BC Design=,, 0 ,, 0 ,,,,,,

Type RM Length L Ch R = 1 ,133664.3,159.928300,159.928300,159.928300
XS GIS Cut Line= 6
482817.319214001740396.408037325482836.564460188740559.796249911
482774.064460188740647.035833225482708.439460188740738.962916568
482702.363071322741091.914305463 482857.74501577 741354.06708324
#Sta/Elev= 30
9780.244443.87859819.103433.00539869.449416.27369939.933391.79849951.163386.6559
9975.766379.01329988.068372.13669998.961371.367410012.67373.181910037.27380.6018
 10102.1379.7476 10123.3382.730410191.07384.449710321.09382.682310361.09383.2606
 10391.1381.125110461.11380.689210491.11390.294210568.12389.004410591.37 387.069
10621.26387.112410640.88388.730710695.99389.457610719.24397.900210730.86398.7406
10754.11 398.66110765.73400.349610800.61400.813210812.23400.741710822.77399.0995
#Mann= 3 , 0 , 0
9780.244  0.0884       09780.244  0.0884       010822.77  0.0884       0
#XS Ineff= 2 , 0
       09956.525        10061.35       0
Bank Sta=9780.244,10822.77
Exp/Cntr=0.3,0.1

Type RM Length L Ch R = 1 ,133504.4,253.088600,253.088600,253.088600
XS GIS Cut Line= 3
482634.758565321740465.310013495482689.446631879741107.601308227
482867.233280331741410.920392171
#Sta/Elev= 30
9840.185422.35829869.982413.13989930.199399.44589950.272392.04369960.308386.2422
 9980.38381.66939990.416373.668810000.45370.749210010.49373.705710020.52379.9352
10030.56381.725410080.74378.947510211.21382.313610301.54380.344110361.76383.0848
10371.79381.064110421.97380.000410432.01380.338710452.08387.167510462.12388.8182
10528.15389.627610551.33386.518810574.88386.096810620.88388.446310653.99387.0705
10667.24390.078410678.84395.647710690.43396.118710713.61390.707610836.38396.8685
#Mann= 3 , 0 , 0
9840.185    0.04       09840.185    0.04       010836.38    0.04       0
#XS Ineff= 2 , 0
       0                10041.28       0
Bank Sta=9840.185,10836.38
Exp/Cntr=0.3,0.1

Type RM Length L Ch R = 1 ,133251.3,248.721500,248.721500,248.721500
XS GIS Cut Line= 6
482435.099473625740628.100605577482519.451643705740765.017923683
482544.679287583 740833.75810577482741.079052418741255.431675628
482801.715372771741378.195685565482876.977966785741519.894526839
#Sta/Elev= 30
9754.199402.59449797.904 391.5149821.593386.98559892.116381.18649925.904375.5583
9979.083375.43319989.708369.219410001.17367.762210023.63376.398310078.87376.8156
10145.15381.475910198.63383.4424 10222.2379.961610255.19379.519610266.19381.8114
10277.19387.023710299.18389.113310332.17389.390510376.16385.482210409.15385.0831
10442.14386.962410485.04385.457310497.74386.730210508.89390.072810542.35392.2186
10586.97392.429910598.24394.749510632.21393.871310688.82395.386610750.98398.4911
#Mann= 3 , 0 , 0
9754.199    0.04       09754.199    0.04       010750.98    0.04       0
#XS Ineff= 2 , 0
       0                               0
Bank Sta=9754.199,10750.98
Exp/Cntr=0.3,0.1

Type RM Length L Ch R = 1 ,133002.5,748.807400,748.807400,748.807400
XS GIS Cut Line= 2
482193.479762673740677.189894572482683.063096017741421.981561244
#Sta/Elev= 30
9780.281412.12899813.561399.86489861.429385.63219933.232372.95019969.133371.2714
  9981.1367.45759993.067368.190410005.03366.144910028.97370.591410040.93370.0656
 10052.9371.040710064.87373.996110076.84375.438810196.51378.034110280.28372.7226
10304.21372.5648 10329.2373.780510352.08377.856910365.61376.626510411.91377.4624
10423.88381.237710435.85382.070710493.05382.463710519.62381.187610547.67381.2112
10565.87 386.77510615.35386.522310627.32388.8089 10656.9389.242910671.58391.0123
#Mann= 3 , 0 , 0
9780.281  0.0444       09780.281  0.0444       010671.58  0.0444       0
#XS Ineff= 2 , 0
       0                               0
Bank Sta=9780.281,10671.58
Exp/Cntr=0.3,0.1

Type RM Length L Ch R = 1 ,132253.7,484.604800,484.604800,484.604800
XS GIS Cut Line= 6
481822.920118839 740958.88853398481971.625687003741129.894462898
482105.013440639741248.551759124482178.364178598741330.166762352
482356.113158494741566.422577709482518.723020524 741807.20833607
#Sta/Elev= 30
9649.632393.86419723.537386.46239802.563380.39979909.187375.50959949.399374.8301
 9962.48371.80039975.562364.98659988.643360.1831    9999360.162610027.62366.1996
10041.27363.650410049.71363.260510098.36369.865810118.47371.2446 10208.2372.0901
10259.37374.730410272.02371.223110284.67371.272610306.17376.232910334.69378.3139
10373.86377.526210396.66374.050710409.05373.988210441.57377.759410470.83377.8131
10507.37380.628710531.72380.382110617.22384.855710712.36384.832610750.96387.1448
#Mann= 3 , 0 , 0
9649.632  0.0584       09649.632  0.0584       010750.96  0.0584       0
#XS Ineff= 2 , 0
       0                               0
Bank Sta=9649.632,10750.96
Exp/Cntr=0.3,0.1