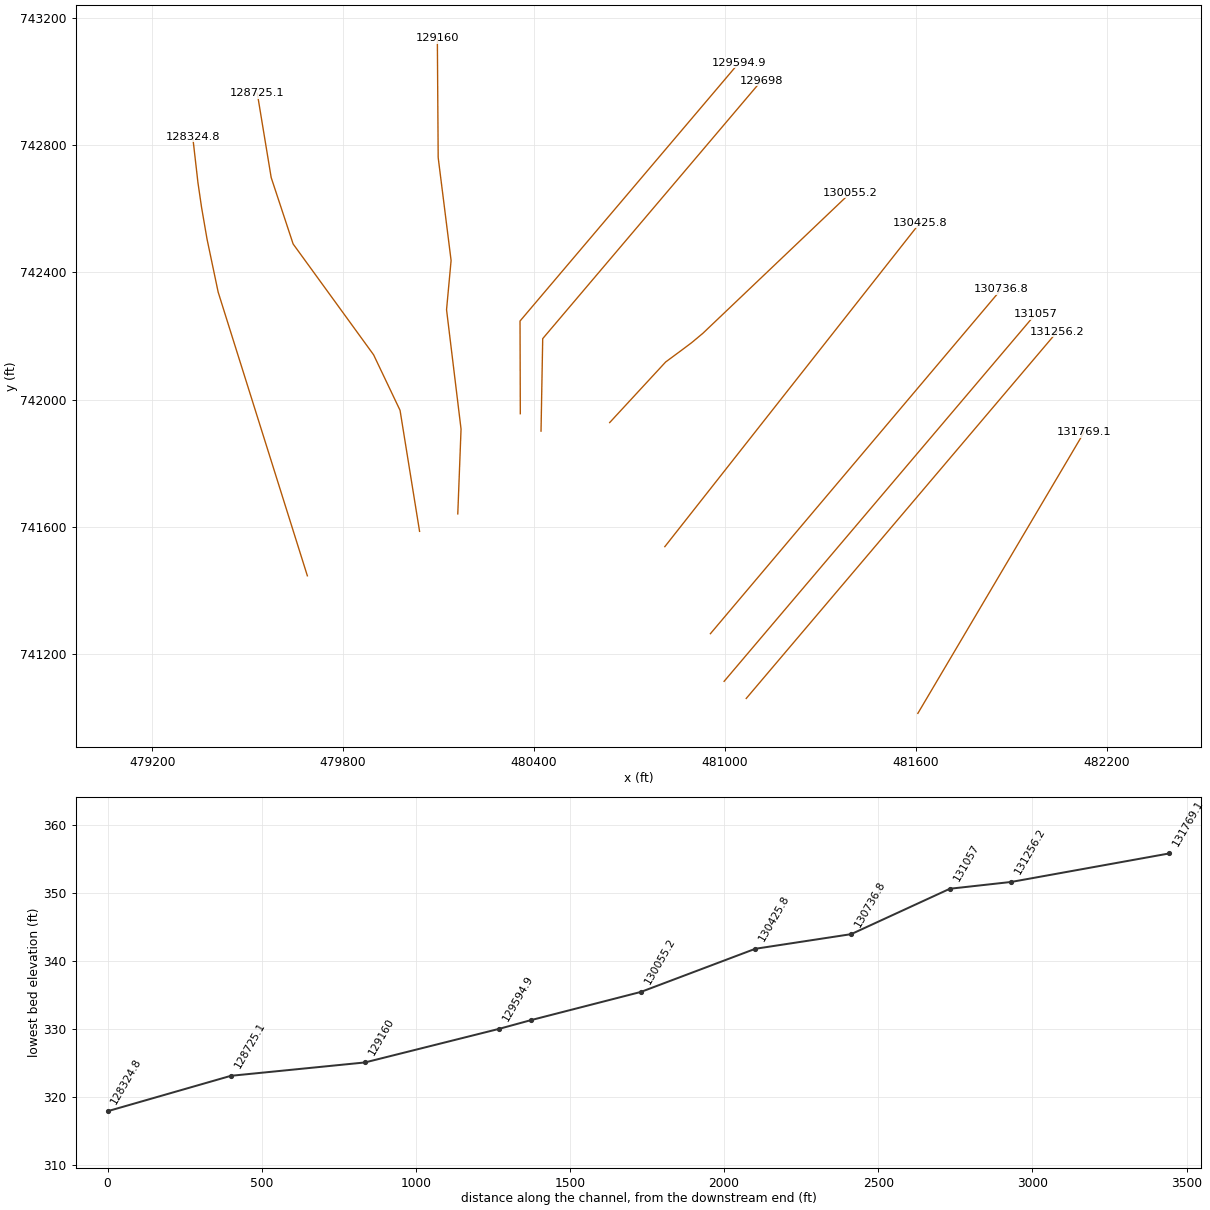
HEC-RAS study 2549_ras.prj: 2549

--- 2549_ras.g01 (geometry) --- (continued)

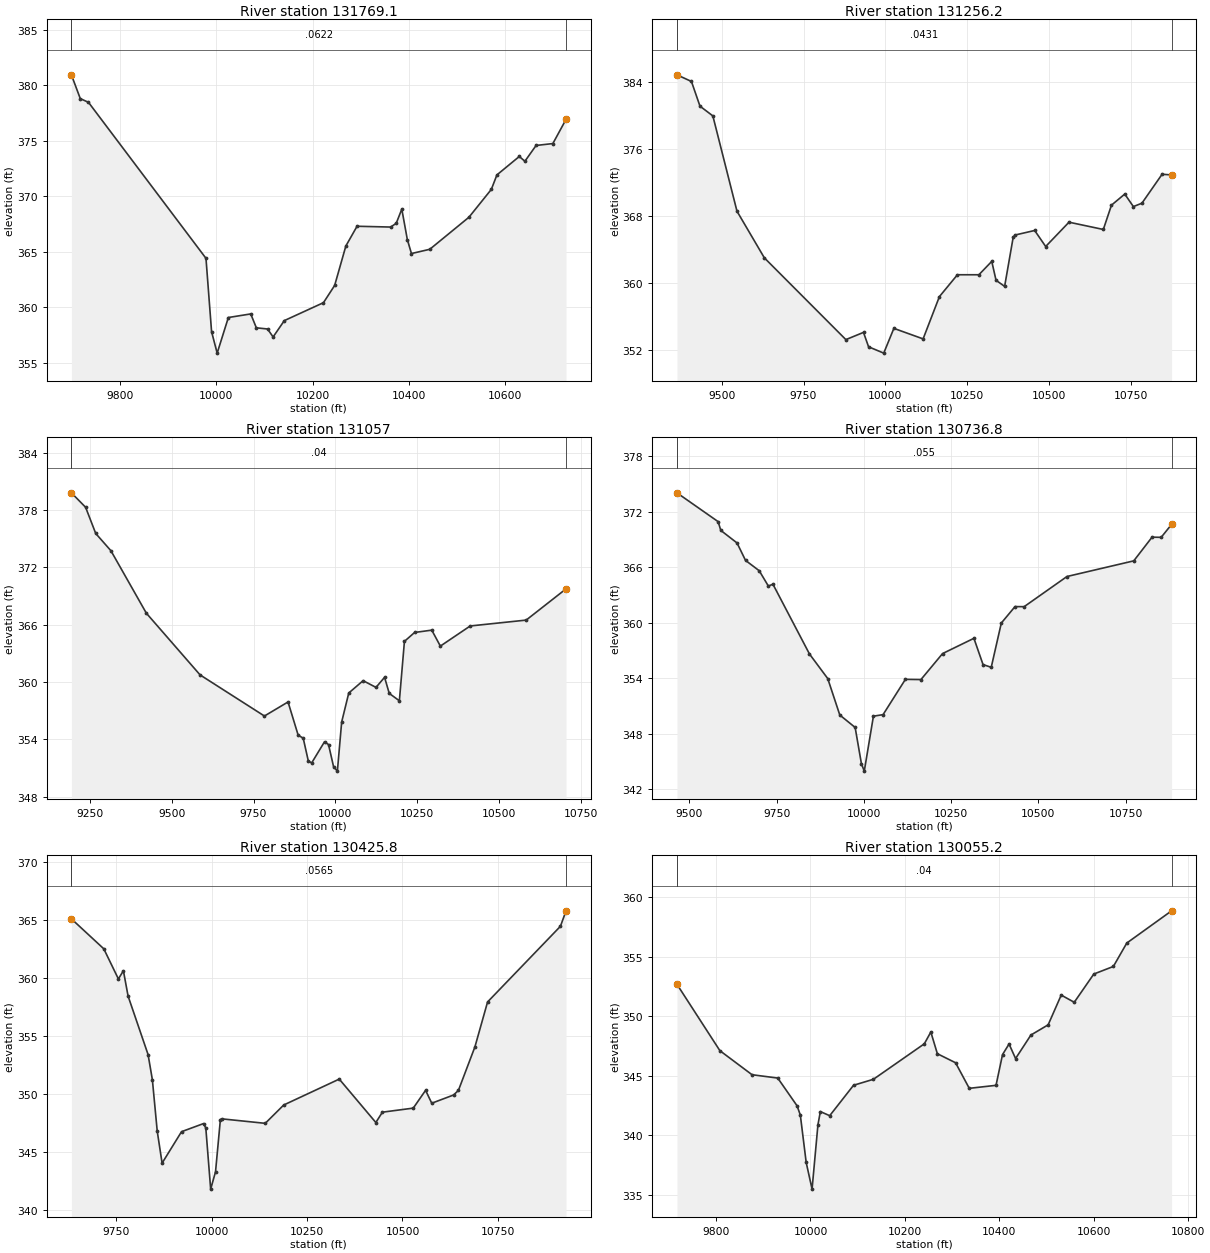
Type RM Length L Ch R = 1 ,131769.1,512.924100,512.924100,512.924100
XS GIS Cut Line= 2
481605.617790967741014.457203045482128.375596017741898.544061244
#Sta/Elev= 30
9699.217380.95269717.651378.8099  9734.7378.47249978.665364.41379990.282357.8028
 10001.9355.869510025.13359.0791 10071.6359.402910083.22358.151310106.46 358.044
10118.07357.328210141.31358.800110222.63360.417210245.86361.9721 10269.1365.5249
10292.33367.304410362.04367.232710373.66367.566710385.27368.848510396.89366.0732
10405.31364.845210443.36365.228410524.68368.117910571.15370.627110582.77371.9326
10629.24373.593810640.85373.162310664.09374.585410698.94374.758610726.29  376.94
#Mann= 3 , 0 , 0
9699.217  0.0622       09699.217  0.0622       010726.29  0.0622       0
#XS Ineff= 2 , 0
       09948.119                       0
Bank Sta=9699.217,10726.29
Exp/Cntr=0.3,0.1

Type RM Length L Ch R = 1 ,131256.2,199.187000,199.187000,199.187000
XS GIS Cut Line= 2
481066.356385943741061.310820896482043.786941495742214.088598657
#Sta/Elev= 30
9363.128 384.8079407.419 384.0189433.518381.0761 9472.85379.91519546.584368.5653
 9630.18363.01589879.284 353.2779933.153354.13879948.616352.42279995.004351.6689
10025.93354.616610115.28353.364610165.09358.397910220.16361.001310285.72361.0006
10325.05362.593910338.16360.337810364.38359.6179 10390.6365.477110397.04365.7388
10456.16366.272610489.81364.364410561.04367.260310665.93366.393410690.83369.2885
10731.48370.6086 10757.7369.117910783.93369.523510845.46372.966610874.51372.8886
#Mann= 3 , 0 , 0
9363.128  0.0431       09363.128  0.0431       010874.51  0.0431       0
#XS Ineff= 2 , 0
       09892.465         10234.6       0
Bank Sta=9363.128,10874.51
Exp/Cntr=0.3,0.1

Type RM Length L Ch R = 1 ,  131057,320.193900,320.193900,320.193900
XS GIS Cut Line= 2
480996.911941499 741115.13026534481974.342497051742267.908043101
#Sta/Elev= 30
9193.514379.79789236.946378.28399267.872375.5423 9314.26373.7368  9422.5367.2007
9586.666 360.7399783.328356.43429855.458357.90659886.383354.43219901.846354.1128
9917.309351.74369927.546351.51919966.878353.7383 9979.16353.44839994.623351.1243
10006.21350.666510019.32355.807610041.01 358.84510084.88360.135710124.21359.4319
10150.43360.486410164.71358.802210195.64358.0304 10211.1364.2504 10242.2365.1811
10294.65365.424510320.87363.753210412.12365.861710583.08366.475810704.89369.7458
#Mann= 3 , 0 , 0
9193.514    0.04       09193.514    0.04       010704.89    0.04       0
#XS Ineff= 2 , 0
       09826.387        10088.21       0
Bank Sta=9193.514,10704.89
Exp/Cntr=0.3,0.1

Type RM Length L Ch R = 1 ,130736.8,311.031400,311.031400,311.031400
XS GIS Cut Line= 2
 480953.89642936741264.863505706 481868.43971926742347.769154221
#Sta/Elev= 30
 9464.12 374.071  9582.1370.9564 9589.82370.00859636.316368.65119660.634366.7669
9699.902365.6469 9726.08363.99179739.169364.19159843.881356.64639896.237 353.989
 9930.79350.04699974.771348.70259992.785344.773410000.95343.980210027.13349.9215
10054.78350.087710118.75353.902510163.27353.879710225.26356.689910315.09358.3415
10341.26355.498910364.75355.206810393.62359.991610432.89361.769210459.07361.7619
10581.73365.0227 10773.2 366.71610825.56369.276510851.74369.259210881.54370.6559
#Mann= 3 , 0 , 0
 9464.12   0.055       0 9464.12   0.055       010881.54   0.055       0
#XS Ineff= 2 , 0
       09924.304        10251.01       0
Bank Sta=9464.12,10881.54
Exp/Cntr=0.3,0.1

Type RM Length L Ch R = 1 ,130425.8,370.603600,370.603600,370.603600
XS GIS Cut Line= 2
480810.667262673741538.301005706481612.750596017742556.530172348
#Sta/Elev= 30
9632.369365.07529717.276362.49719755.466359.90879768.654360.61039780.926358.4294
9833.296353.40159844.576351.23279857.306346.81129870.036344.06189920.955346.7659
9978.739347.46579984.605347.07729997.335 341.82510010.06343.319710022.79347.8072
10027.22347.868310140.34347.484910188.82349.062910334.27  351.2910430.15 347.556
10447.39348.444910528.19348.793210560.51 350.32510576.67349.215310633.83349.9224
10646.56350.3189 10689.8354.063310722.94357.925710913.89364.436410928.57365.7656
#Mann= 3 , 0 , 0
9632.369  0.0565       09632.369  0.0565       010928.57  0.0565       0
#XS Ineff= 2 , 0
       0 9917.36        10071.14       0
Bank Sta=9632.369,10928.57
Exp/Cntr=0.3,0.1

Type RM Length L Ch R = 1 ,130055.2,357.184900,357.184900,357.184900
XS GIS Cut Line= 6
 480637.38427186741928.196532458 480813.29352513 742118.54839249
480861.024649024 742153.78531599480894.761003345  742179.0469203
480929.987767279742208.438517526481394.328716367742650.418754652
#Sta/Elev= 30
9717.223352.67969808.184347.10489876.265345.0856 9930.73344.80529971.579342.4789
9978.531341.70069990.961337.717910003.39335.479910015.82340.879610020.95341.9924
10040.75341.645210091.22344.199410133.28344.701610241.13347.680610254.94348.6723
10268.74346.849510307.33346.090110336.34343.943110392.99344.1952 10406.8346.7793
10420.61347.664210434.41 346.44510466.88348.418710503.44349.276310531.05351.7727
10558.66351.167710600.08353.5396 10641.5354.175710669.94356.141310764.82358.8472
#Mann= 3 , 0 , 0
9717.223    0.04       09717.223    0.04       010764.82    0.04       0
#XS Ineff= 2 , 0
       09911.417        10082.79       0
Bank Sta=9717.223,10764.82
Exp/Cntr=0.3,0.1

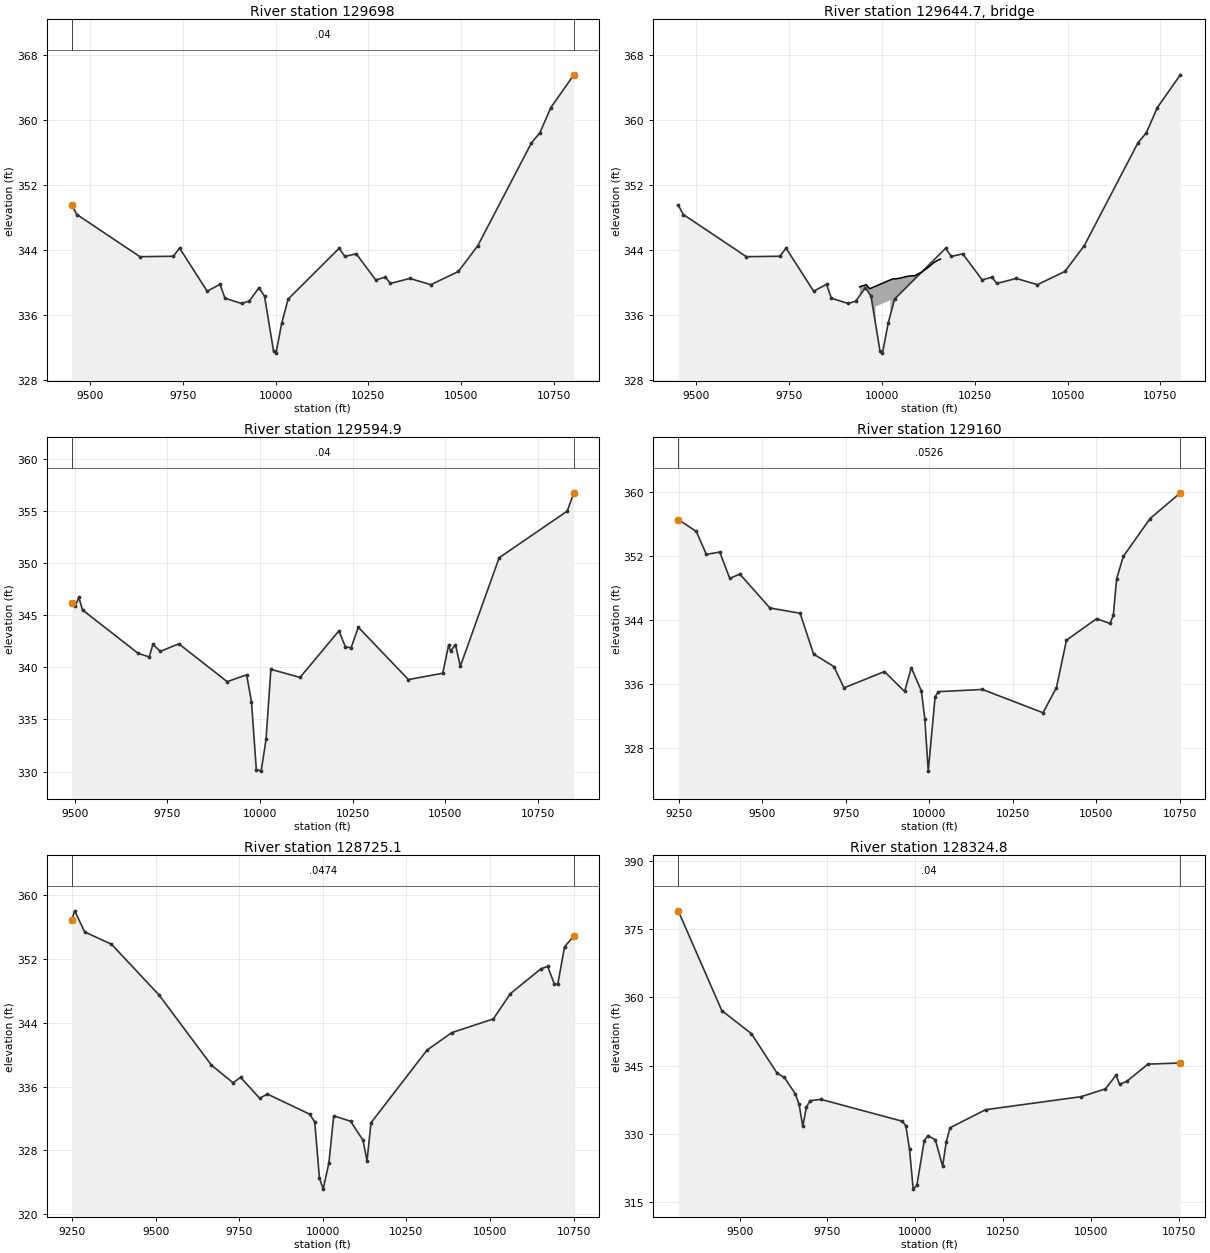
Type RM Length L Ch R = 1 ,  129698,103.066800,103.066800,103.066800
XS GIS Cut Line= 3
480421.674207121741901.304477915480426.953872979742191.866244733
481114.099441499743002.283043116
#Sta/Elev= 30
  9450.9349.51149464.597348.34979634.625343.1664 9724.64343.21959741.509344.2129
9815.802338.92899850.504339.77469863.615338.06859908.579337.41849929.169337.7035
 9955.39 339.351 9970.43338.31279994.722331.568110001.36331.319610016.82335.0219
10034.05  337.9610171.45344.200410186.91343.194410217.61343.524710270.05 340.314
10296.27340.655510309.38339.877910361.82340.492710418.85339.731710492.93341.3512
10545.37344.538310689.59357.131210712.64358.399910742.04361.486310804.03365.5097
#Mann= 3 , 0 , 0
  9450.9    0.04       0  9450.9    0.04       010804.03    0.04       0
#XS Ineff= 2 , 0
       09957.343         10033.7       0
Bank Sta=9450.9,10804.03
Exp/Cntr=0.3,0.1

Type RM Length L Ch R = 3 ,129644.7,,,
BEGIN DESCRIPTION:
END DESCRIPTION:
Bridge Culvert--1,0,-1,-1, 0
Deck Dist Width WeirC Skew NumUp NumDn MinLoCord MaxHiCord MaxSubmerge Is_Ogee
44.033400,15.000000,2.6,0, 29, 29, , , 0.95, 0, 0,0,,
 9939.93 9944.65 9952.25 9957.69 9966.95 9982.78 9982.7810022.7810022.7810030.97
10035.9010045.7710048.9410061.3610061.9810075.0110076.9510088.0510092.5310101.09
10108.1210114.1210123.7110127.1610139.3010140.2010153.2310154.8810157.77
  339.45  339.55  339.64  339.73  339.23  339.54  339.54  340.32  340.32  340.47
  340.43  340.52  340.53  340.68  340.70  340.80  340.81  340.82  340.93  341.14
  341.31  341.51  341.82  341.95  342.43  342.45  342.79  342.81  342.87
 -660.55 -660.45 -660.36 -660.27 -660.77 -660.46  337.04  337.82 -659.68 -659.53
 -659.57 -659.48 -659.47 -659.32 -659.30 -659.20 -659.19 -659.18 -659.07 -658.86
 -658.69 -658.49 -658.18 -658.05 -657.57 -657.55 -657.21 -657.19 -657.13
 9939.93 9944.65 9952.25 9957.69 9966.95 9982.28 9982.2810022.2810022.2810030.97
10035.9010045.7710048.9410061.3610061.9810075.0110076.9510088.0510092.5310101.09
10108.1210114.1210123.7110127.1610139.3010140.2010153.2310154.8810157.77
  339.45  339.55  339.64  339.73  339.23  339.53  339.53  340.31  340.31  340.47
  340.43  340.52  340.53  340.68  340.70  340.80  340.81  340.82  340.93  341.14
  341.31  341.51  341.82  341.95  342.43  342.45  342.79  342.81  342.87
 -660.55 -660.45 -660.36 -660.27 -660.77 -660.47  337.03  337.81 -659.69 -659.53
 -659.57 -659.48 -659.47 -659.32 -659.30 -659.20 -659.19 -659.18 -659.07 -658.86
 -658.69 -658.49 -658.18 -658.05 -657.57 -657.55 -657.21 -657.19 -657.13
BR Coef=-1 , 0 , 0 ,, 0 ,,,0.8,0,1,0,
WSPro=,,,, 1 ,,,, 0 ,,,, 0 ,,,,-1 ,-1 ,-1 , 0 , 0 , 0 , 0 , 0
BC Design=,, 0 ,, 0 ,,,,,,

Type RM Length L Ch R = 1 ,129594.9,434.937700,434.937700,434.937700
XS GIS Cut Line= 3
480356.570040494741955.991977915480355.687305629742247.164632529
481043.786941499743058.706654191
#Sta/Elev= 30
 9491.65346.19799500.658345.85029510.658346.70169520.658345.50519670.659341.3437
9700.659340.99439710.659342.19889730.659 341.532 9780.66342.25469911.094338.6236
9963.537339.27929976.648336.71979989.758330.190410002.87330.039310015.98333.0861
10029.09339.809410107.76 339.02910212.64 343.49510230.18341.969410245.64341.8673
10265.08 343.84610400.27338.824210493.05339.432710508.51342.098610514.19341.5573
 10527.3 342.16910540.41 340.101 10645.3350.517810828.85354.984110846.82356.7418
#Mann= 3 , 0 , 0
 9491.65    0.04       0 9491.65    0.04       010846.82    0.04       0
#XS Ineff= 2 , 0
       09959.487        10045.44       0
Bank Sta=9491.65,10846.82
Exp/Cntr=0.3,0.1

Type RM Length L Ch R = 1 ,  129160,434.937800,434.937800,434.937800
XS GIS Cut Line= 6
480160.116230844741641.272393285480170.370172708741907.799667715
 480124.82033602742282.721843046 480139.10285729 742437.38636268
480098.549885479742760.790716647480095.900739156743135.385171301
#Sta/Elev= 30
9249.086356.56879303.011355.09779333.122352.22369373.219352.50479403.242349.2118
9433.251349.7558 9523.27345.50829613.604 344.8489653.912339.7413 9714.58338.1824
9744.914335.51459866.044337.55179926.213335.05859946.232338.04179976.435335.1202
 9986.63331.67219996.923325.093210017.45334.399110027.56335.039910158.96335.3144
10340.27332.397110380.37335.5407 10410.4341.482310500.47 344.16910540.47343.5723
10550.48 344.57910560.48349.178410580.48351.9684 10660.5356.6987 10750.9359.9195
#Mann= 3 , 0 , 0
9249.086  0.0526       09249.086  0.0526       0 10750.9  0.0526       0
#XS Ineff= 2 , 0
       09949.768        10228.51       0
Bank Sta=9249.086,10750.9
Exp/Cntr=0.3,0.1

Type RM Length L Ch R = 1 ,128725.1,400.311900,400.311900,400.311900
XS GIS Cut Line= 6
480040.053787789741586.355757145479978.723089572741966.662667309
479895.624469668742141.076251973 479642.78661414742489.296528998
479573.872805531742697.862716918479530.166537919742962.667793919
#Sta/Elev= 30
9249.105356.91289257.749358.05969287.751355.41279367.919353.86679509.847347.5128
9666.763338.69369731.686336.47559754.014337.16529811.082334.54149834.481335.0523
9960.862332.53169975.845 331.5559989.861324.5402   10001323.1256 10018.2326.4098
10032.66332.326910083.12 331.64810120.19329.270210132.32326.686110144.16331.4518
10311.87 340.58110385.95342.773410510.05344.487910561.07347.666910652.42350.7797
10672.63351.080510692.85348.854810702.93348.859610723.06353.543610750.91354.8904
#Mann= 3 , 0 , 0
9249.105  0.0474       09249.105  0.0474       010750.91  0.0474       0
#XS Ineff= 2 , 0
       0                10142.82       0
Bank Sta=9249.105,10750.91
Exp/Cntr=0.3,0.1

Type RM Length L Ch R = 1 ,128324.8,390.484000,390.484000,390.484000
XS GIS Cut Line= 6
479687.516221017741446.660380691479407.285051286 742337.88507995
479372.255094886742504.696938068479355.131199539742604.059480667
479343.784072369742681.602633595 479327.20282504 742826.66224809
#Sta/Elev= 30
9325.073 379.0369449.125357.12579533.492352.05799606.366343.40529627.331342.4302
9658.779338.81229669.262336.51859679.744331.70269690.227335.9279 9700.71337.3486
9732.158 337.6159962.777332.8266 9973.26331.85629983.742326.67319994.225317.9091
10004.71318.746510025.67328.564510036.16329.639310057.12328.776810078.09322.9705
10088.57328.346910099.05 331.37710200.26335.352410472.49 338.21510541.65339.9277
10571.97342.942210582.08340.941110602.29341.573410662.71345.363710754.97345.6204
#Mann= 3 , 0 , 0
9325.073    0.04       09325.073    0.04       010754.97    0.04       0
#XS Ineff= 2 , 0
       0 9943.36        10157.79       0
Bank Sta=9325.073,10754.97
Exp/Cntr=0.3,0.1