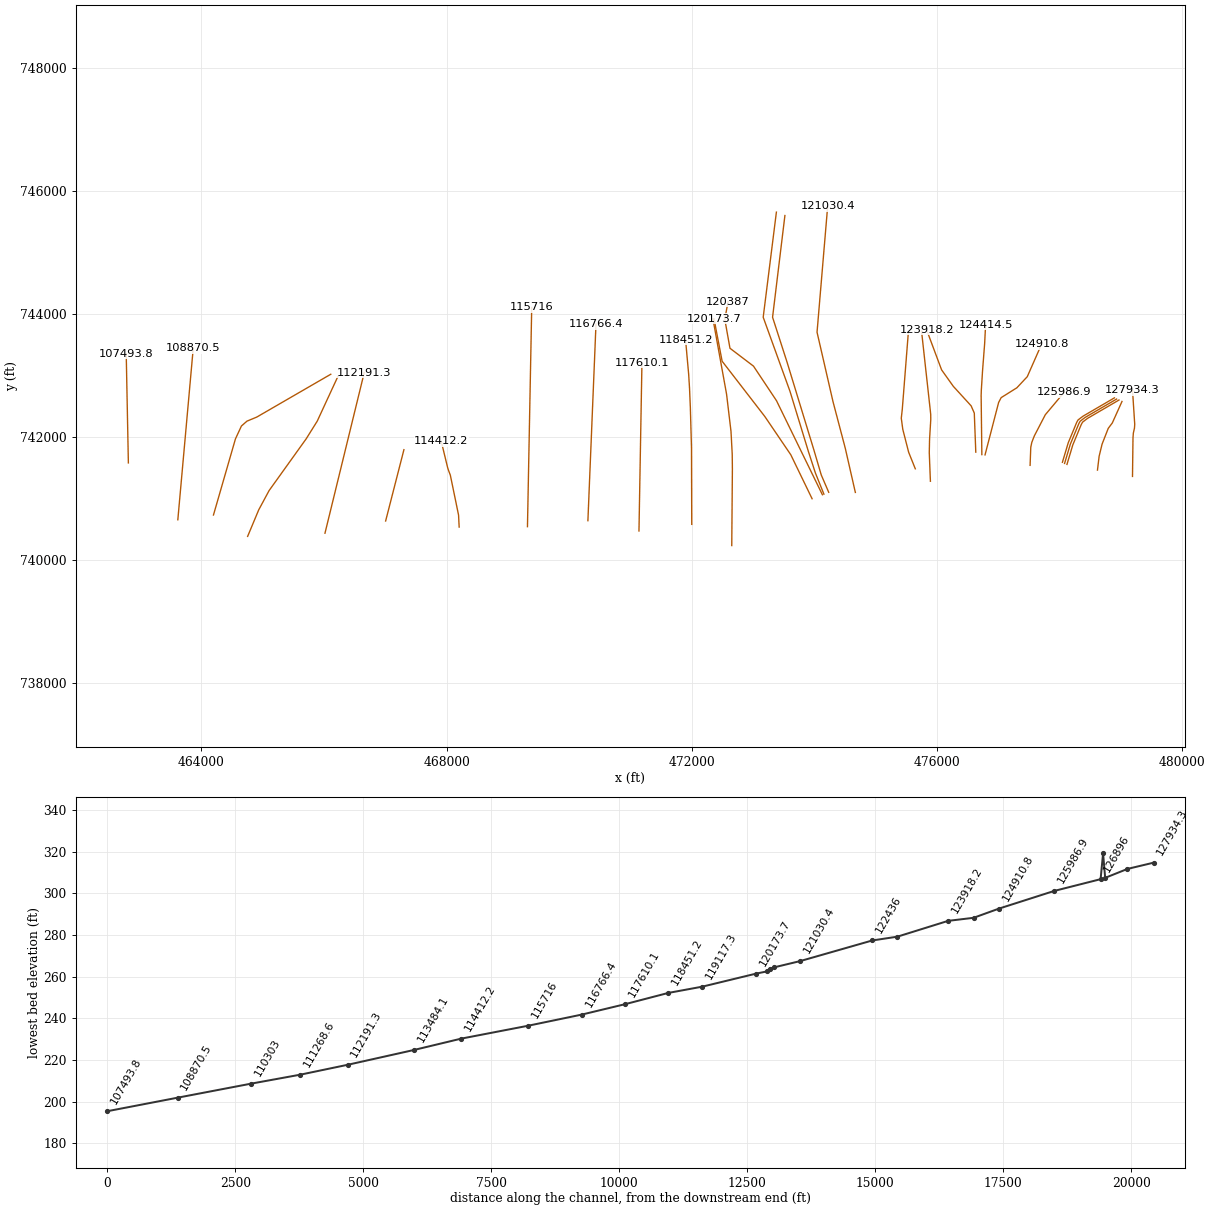
HEC-RAS study 2549_ras.prj: 2549

--- 2549_ras.g01 (geometry) --- (continued)

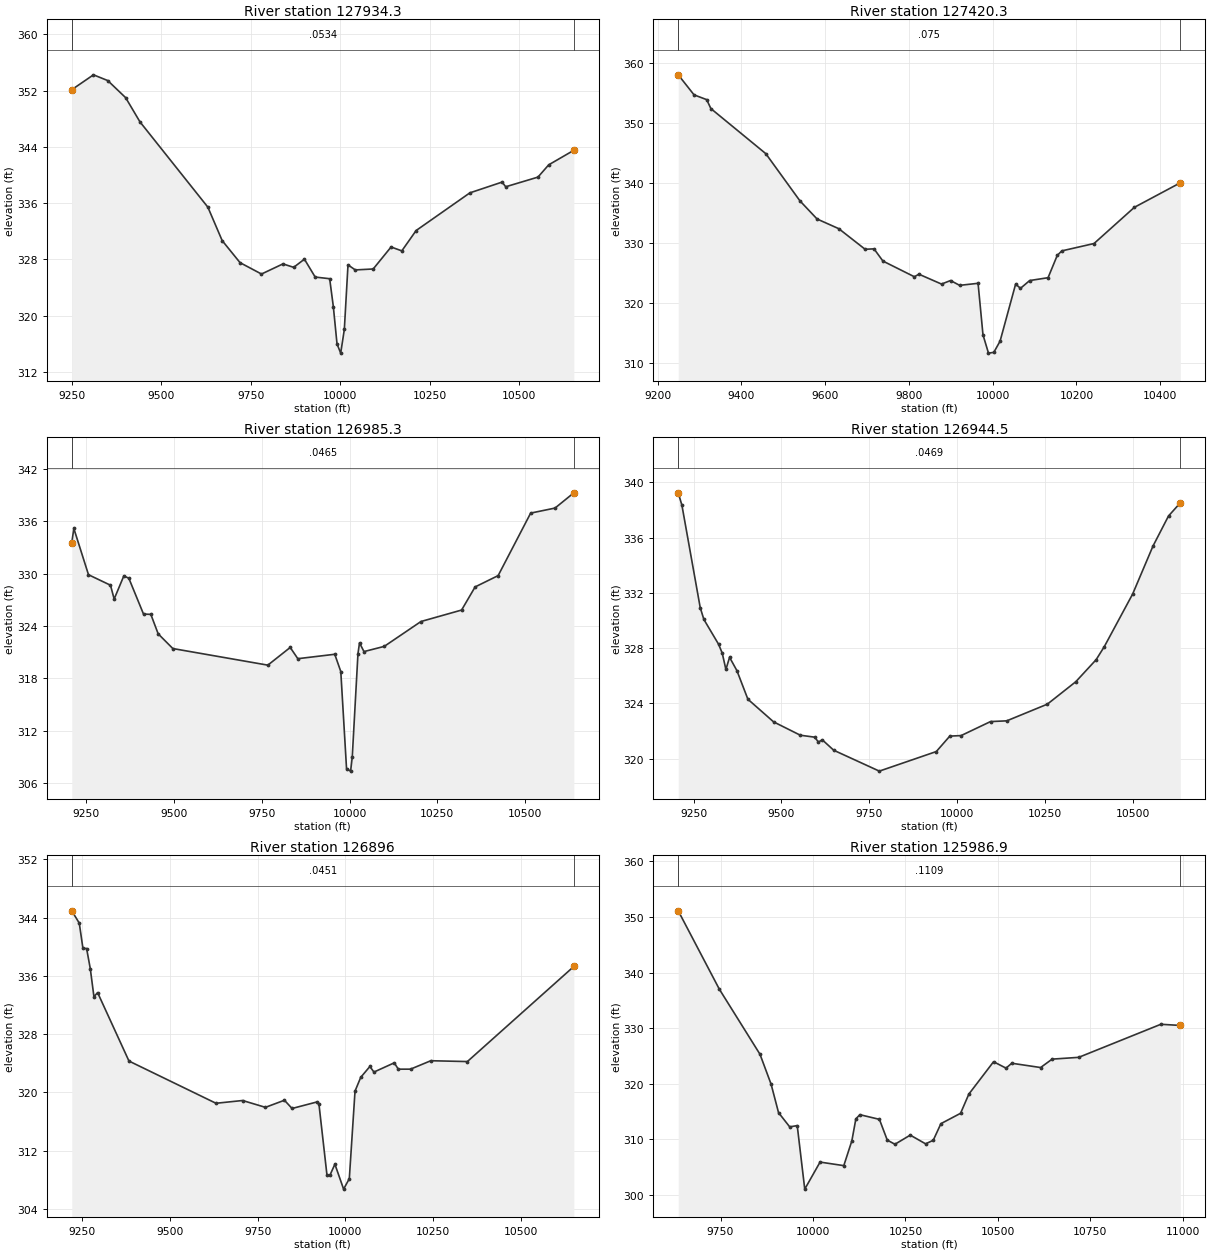
Type RM Length L Ch R = 1 ,127934.3,514.017400,514.017400,514.017400
XS GIS Cut Line= 6
479191.647089452741364.316327363479199.837424099741992.913073242
479205.687844038742069.429039001479223.864021331742149.505421922
479228.040165424742210.035214037479192.000161976742765.066586003
#Sta/Elev= 30
9249.087352.14359309.782354.2568 9349.79353.4387  9399.8351.00759439.808347.5695
9629.819335.43389669.821330.67999719.823 327.5439779.826325.92579839.829327.3659
 9869.83326.87739899.895328.03749929.983325.49419970.505325.26029980.795321.2932
9991.085315.986810001.37314.676210011.58318.0571 10021.8327.228910042.13326.5094
10092.29326.643610142.32 329.77210172.34329.219510212.43332.114610362.75337.4701
10452.94339.002910462.96338.335610553.16339.708910583.26341.455910653.58343.5262
#Mann= 3 , 0 , 0
9249.087  0.0534       09249.087  0.0534       010653.58  0.0534       0
#XS Ineff= 2 , 0
       09760.342        10033.74       0
Bank Sta=9249.087,10653.58
Exp/Cntr=0.3,0.1

Type RM Length L Ch R = 1 ,127420.3,434.937800,434.937800,434.937800
XS GIS Cut Line= 6
478620.069762319741467.417240456478647.236407161741692.654320717
 478695.44069016741889.361761957478796.177717298742145.993354887
478862.310330331742233.236914903479020.125161976742582.774919346
#Sta/Elev= 30
9249.149358.01169286.925354.67429317.079353.8779 9327.13352.38749458.229344.8815
9539.805337.0137 9580.69333.99759632.569332.38399695.355328.95659716.608329.0272
 9737.86326.99439812.978 324.3799823.781324.80489877.795323.16099899.401323.7518
9921.007322.94649965.055323.28839976.786314.71139989.905311.658610002.61 311.784
10017.59313.6509 10054.7323.150110066.36322.4537 10088.3323.747210132.19324.2218
10154.13327.9387 10165.1  328.6910241.91329.913510338.27335.943710447.94 340.029
#Mann= 3 , 0 , 0
9249.149   0.075       09249.149   0.075       010447.94   0.075       0
#XS Ineff= 2 , 0
       09764.821        10126.53       0
Bank Sta=9249.149,10447.94
Exp/Cntr=0.3,0.1

Type RM Length L Ch R = 1 ,126985.3,40.819700,40.819700,40.819700
XS GIS Cut Line= 6
478122.360436887741559.393864885  478217.4125202741875.800114885
478356.735436887742210.435531527  478377.5687702 742246.89386487
478458.297936857742308.091781542 478971.31877023742606.268864885
#Sta/Elev= 30
9209.006333.51929214.859 335.1779256.625329.87359319.274328.67099329.716327.0889
9357.209329.73859371.481329.47259413.247325.3694 9434.13325.33269455.013323.1025
9496.779321.41799767.259319.5163 9830.98 321.5439852.645320.25589957.798320.7623
9975.003318.78689991.391307.642910002.94 307.37710007.64308.9984 10023.9320.8394
10028.31322.068410040.99321.069210098.72321.665910203.29324.514910318.95325.8281
10357.43328.475610423.05329.774710515.58336.931910584.98337.509210638.56339.2551
#Mann= 3 , 0 , 0
9209.006  0.0465       09209.006  0.0465       010638.56  0.0465       0
#XS Ineff= 2 , 0
       09784.346        10130.91       0
Bank Sta=9209.006,10638.56
Exp/Cntr=0.3,0.1

Type RM Length L Ch R = 1 ,126944.5,48.492700,48.492700,48.492700
XS GIS Cut Line= 6
478083.297936887741575.018864885  478178.3500202741891.425114885
478317.672936887742226.060531527  478338.5062702 742262.51886487
478419.235436857742323.716781542 478932.25627023742621.893864885
#Sta/Elev= 30
9206.395339.23849216.817338.34659269.024330.93099279.466330.07479321.232328.2854
9331.673327.64129342.115326.45919352.556327.33849373.439326.37589404.764324.3048
9477.854322.66929554.072321.70239594.803321.56179605.635321.20739616.467321.3719
9648.963 320.6189778.949319.10489941.241 320.5229979.638321.638810011.82 321.676
 10095.5322.689210141.76322.742510257.43  323.9510338.39325.574310396.22 327.166
10419.36328.103410500.32 331.92210558.15335.387510602.33 337.56310635.94338.5148
#Mann= 3 , 0 , 0
9206.395  0.0469       09206.395  0.0469       010635.94  0.0469       0
#XS Ineff= 2 , 0
       09776.658         10110.7       0
Bank Sta=9206.395,10635.94
Exp/Cntr=0.3,0.1

Type RM Length L Ch R = 1 ,  126896,909.073000,909.073000,909.073000
XS GIS Cut Line= 6
478048.141686887741594.550114885  478143.1937702741910.956364885
478282.516686887742245.591781527  478303.3500202 742282.05011487
478384.079186857742343.248031542 478897.10002023742641.425114885
#Sta/Elev= 30
9220.862344.93799242.214343.25089252.656 339.7869263.097 339.7659273.539337.0176
 9283.98333.15129294.422333.71219383.728324.31689631.442318.52079707.266318.8997
9772.259317.96239826.419318.93679848.083317.80589918.722318.69759924.553318.4448
9947.588308.61599955.708308.61859970.025310.16029994.867306.735110011.12308.1762
10027.37320.188610043.63322.082410069.66323.569910081.23322.804210139.06324.0712
10150.63323.201410185.33323.203510243.16324.360710347.26 324.24610650.41337.3023
#Mann= 3 , 0 , 0
9220.862  0.0451       09220.862  0.0451       010650.41  0.0451       0
#XS Ineff= 2 , 0
       09781.222        10100.38       0
Bank Sta=9220.862,10650.41
Exp/Cntr=0.3,0.1

Type RM Length L Ch R = 1 ,125986.9,1076.151300,1076.151300,1076.151300
XS GIS Cut Line= 6
477520.642566442741544.175333291477532.098786891741840.171387658
477549.194504946741919.379134148477590.815252751742025.040084302
477769.389828205742367.627320051478079.113443285742734.481561244
#Sta/Elev= 30
9635.606351.1075 9746.64337.0299 9856.76325.30949886.775319.93299906.876314.8229
9937.086312.26169957.426312.49189977.766301.068110019.18305.930310083.36305.2922
10105.12309.742410115.99 313.69710126.87314.452510179.69313.613610200.93309.8842
10221.65309.137110263.11310.778510304.56309.212410325.28 309.85110346.01312.8383
10399.17314.703910421.58318.155810488.39323.9738 10522.1322.824710537.69323.7011
10615.63322.930610646.81324.442110718.67 324.76310940.77330.706710993.47330.5007
#Mann= 3 , 0 , 0
9635.606  0.1109       09635.606  0.1109       010993.47  0.1109       0
#XS Ineff= 2 , 0
       0                10150.24       0
Bank Sta=9635.606,10993.47
Exp/Cntr=0.3,0.1

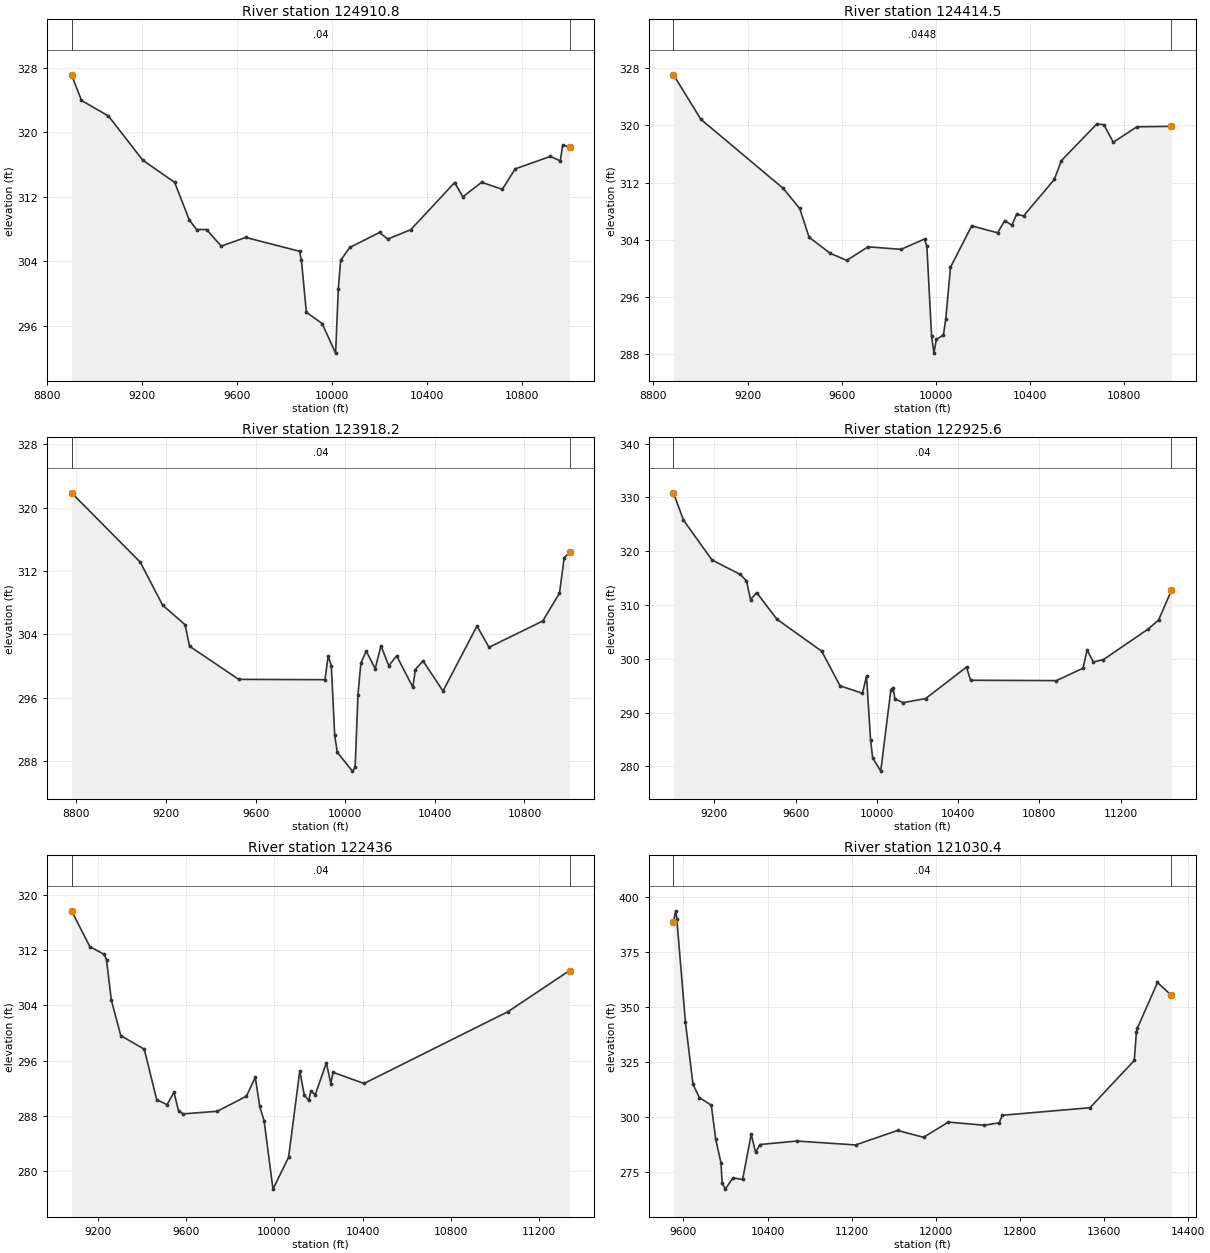
Type RM Length L Ch R = 1 ,124910.8,496.306100,496.306100,496.306100
XS GIS Cut Line= 6
476785.710665464741714.516283482477007.064832121742565.210727915
477048.621457249          742645477305.093532115742804.928236067
477474.734080672742985.719009593477707.782356471743512.304504275
#Sta/Elev= 30
8901.794327.11838943.626323.94279057.289 322.0149201.951316.5349 9336.28313.7887
9398.277309.11149429.276307.92869470.608 307.9379532.606305.87679635.936306.9535
9862.939305.23769870.778304.12599891.566297.6718  9957.9296.279210014.82292.6082
10026.26 300.572 10036.1304.110310074.33305.707210199.95307.570510234.31306.7502
10331.67307.9143 10516.7313.762110551.05311.984210630.29313.797310717.56312.9183
10772.01 315.46210920.16316.997610961.92316.450910972.36318.415911000.87318.1566
#Mann= 3 , 0 , 0
8901.794    0.04       08901.794    0.04       011000.87    0.04       0
#XS Ineff= 2 , 0
       0                10231.62       0
Bank Sta=8901.794,11000.87
Exp/Cntr=0.3,0.1

Type RM Length L Ch R = 1 ,124414.5,496.306000,496.306000,496.306000
XS GIS Cut Line= 6
476733.627332121741718.856561244476722.015154004742679.471184298
476724.768912494 742760.90870361476744.660834879743076.717198908
476779.346191913743525.671134725476795.062960654743831.647690147
#Sta/Elev= 30
8885.573327.05049001.728320.8434 9351.76311.19089421.767308.3851 9461.77 304.362
9551.779302.12089621.785301.13259711.794303.03469851.804 302.6789951.901304.1183
9961.923303.11349981.986290.55929992.061288.188310002.16290.097610032.29290.7438
10042.31292.951710062.33300.187610152.41305.958110262.63304.992610292.72306.7038
10322.81  306.0410342.87307.558510372.96307.356510503.34312.439610533.43315.0686
10683.88320.193110713.94320.077910753.99317.634110854.12319.796811000.96319.8547
#Mann= 3 , 0 , 0
8885.573  0.0448       08885.573  0.0448       011000.96  0.0448       0
#XS Ineff= 2 , 0
       0                10138.46       0
Bank Sta=8885.573,11000.96
Exp/Cntr=0.3,0.1

Type RM Length L Ch R = 1 ,123918.2,992.612200,992.612200,992.612200
XS GIS Cut Line= 6
476634.668998897741758.787116811476610.363443255742394.203783467
476558.280109912742512.259339035476267.922217667742828.806489035
476076.682437062743096.296519041475832.026465088743748.068461567
#Sta/Elev= 30
8778.432321.88099084.869 313.1269184.942307.69159285.015305.2235 9305.03302.5057
9524.483298.31819909.317298.27579923.831301.27159937.728300.04469952.935291.2457
9964.459289.098810031.94286.726410044.04287.192110056.83296.400310069.63 300.374
10093.63301.893210133.61299.663210159.35302.563110194.37300.039210229.38301.2958
10301.57297.328910312.93299.562110346.86300.657410436.24296.845310588.01305.0631
10641.45302.365310881.26305.683710956.16309.201410976.95313.637611000.92314.3695
#Mann= 3 , 0 , 0
8778.432    0.04       08778.432    0.04       011000.92    0.04       0
#XS Ineff= 2 , 0
       0                10099.33       0
Bank Sta=8778.432,11000.92
Exp/Cntr=0.3,0.1

Type RM Length L Ch R = 1 ,122925.6,489.597000,489.597000,489.597000
XS GIS Cut Line= 6
475894.283093482741286.092741296475875.749183685741748.156224057
475880.448097944741967.428759903475900.004312962742284.964782268
475899.260558546742373.809662104475749.252332121743727.537116796
#Sta/Elev= 30
 8999.02330.86789047.998325.80029188.198318.39199328.323315.68419358.341  314.47
9378.343311.00929408.347312.31839508.356307.35639728.526 301.434 9818.72294.9858
9928.957293.59849948.984 296.7629969.004284.99169979.015281.627610019.04279.1289
10069.04294.276510079.04294.653410089.05292.558310129.29291.856110239.97292.6241
10441.19298.461310461.31296.025110883.88295.957311014.68298.2621 11034.8301.6755
11064.99299.426611115.29299.865811336.64305.577111386.94307.241211449.86312.7354
#Mann= 3 , 0 , 0
 8999.02    0.04       0 8999.02    0.04       011449.86    0.04       0
#XS Ineff= 2 , 0
       0 9898.51         10437.1       0
Bank Sta=8999.02,11449.86
Exp/Cntr=0.3,0.1

Type RM Length L Ch R = 1 ,  122436,1405.558300,1405.558300,1405.558300
XS GIS Cut Line= 6
475647.689832121741488.170797348475539.256604999 741757.56748876
475443.592127323742129.732195899475419.114389747742310.915751845
475435.402846158742455.560781628 475533.97455436743702.363505706
#Sta/Elev= 30
9082.285317.74969165.104312.54629229.782311.42919240.561310.63399262.121304.8087
9305.239299.60589411.397 297.6499467.826290.29959514.814289.5834 9545.84291.3812
9566.523288.69789587.207288.2463 9741.83288.62149873.948290.81369914.063293.5653
9934.111289.33269954.125287.2244 9994.19277.310210064.96281.961910115.56294.5056
10135.62291.019110155.68290.189910165.71291.516810185.77291.052510235.93295.6539
10255.99292.656110266.02294.283410406.46292.662811058.49 303.10511336.72309.0659
#Mann= 3 , 0 , 0
9082.285    0.04       09082.285    0.04       011336.72    0.04       0
#XS Ineff= 2 , 0
       09863.839        10304.06       0
Bank Sta=9082.285,11336.72
Exp/Cntr=0.3,0.1

Type RM Length L Ch R = 1 ,121030.4,506.224200,506.224200,506.224200
XS GIS Cut Line= 5
474669.519159989741104.388274115474504.588604407741824.874385219
474304.935826616742580.082718563474044.519159959743708.554940772
474218.130271094745757.166051906
#Sta/Elev= 30
9506.185388.7828 9527.33393.71149537.588390.14899619.658343.21049691.468315.0306
 9753.02308.94629865.866305.5241  9906.9290.22019958.194279.22339968.452270.2077
9999.228267.430310071.04272.522910163.37271.826810245.44292.363910286.81284.0666
10328.19287.668910679.87289.252411236.76287.485211637.01294.040211883.32290.9538
12119.37297.846812462.03 296.42912602.53297.518912632.64300.948313465.61304.3671
13887.12325.804513907.19338.629113917.23340.547914107.91361.194214240.55355.3125
#Mann= 3 , 0 , 0
9506.185    0.04       09506.185    0.04       014240.55    0.04       0
#XS Ineff= 2 , 0
       09913.696        10311.83       0
Bank Sta=9506.185,14240.55
Exp/Cntr=0.3,0.1

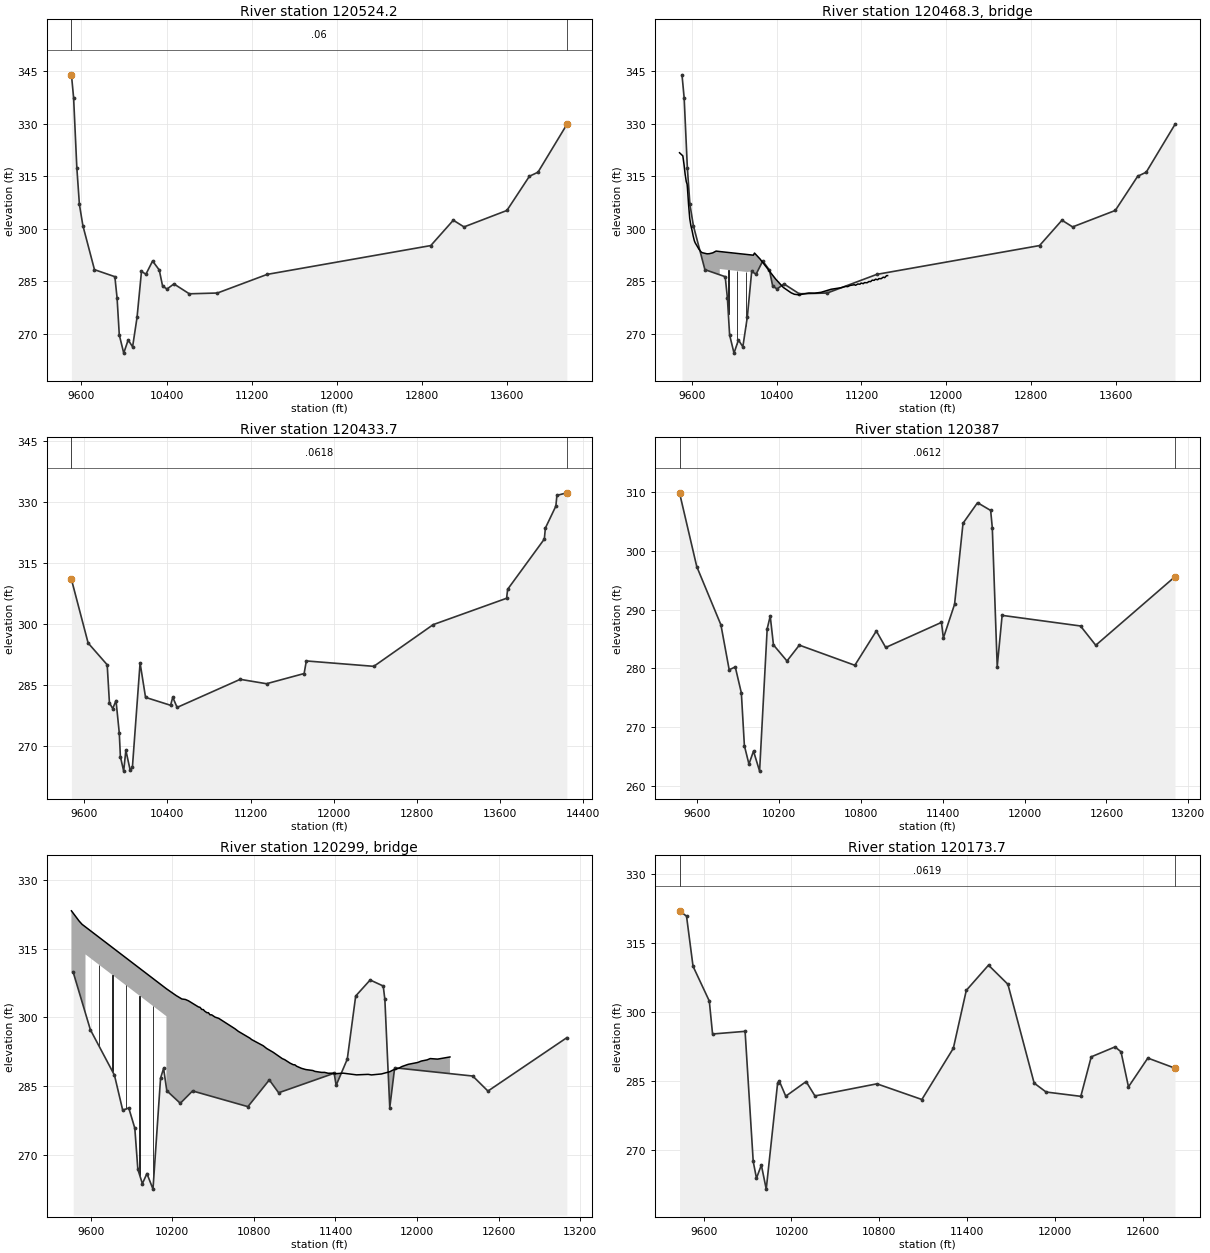
Type RM Length L Ch R = 1 ,120524.2,90.511700,90.511700,90.511700
XS GIS Cut Line= 6
474235.044397742741106.294670965474113.126960188741388.695266113
473993.769321352741792.341099441473554.935826629743222.443829641
473318.824715525743951.610496327 473520.21360442745604.388274103
#Sta/Elev= 30
9505.573 343.9769525.947337.45459556.145317.48299580.408306.94099613.084300.8803
9722.005288.29039913.594286.2857 9934.45280.20819955.306269.63779997.018264.4352
10038.73268.197310080.44266.247210122.15274.643310163.87287.775810205.58286.9932
10268.25290.762710331.01288.191810362.39283.569610404.23282.760310468.51284.2174
10613.44281.390810877.58281.615411345.65286.945312882.67295.177213094.23302.4213
13194.97300.508713597.93305.210113809.48314.984213890.07316.144114161.45329.7926
#Mann= 3 , 0 , 0
9505.573    0.06       09505.573    0.06       014161.45    0.06       0
#XS Ineff= 2 , 0
       0 9874.95         10206.4       0
Bank Sta=9505.573,14161.45
Exp/Cntr=0.3,0.1

Type RM Length L Ch R = 3 ,120468.3,,,
BEGIN DESCRIPTION:
END DESCRIPTION:
Bridge Culvert--1,0,-1,-1, 0
Deck Dist Width WeirC Skew NumUp NumDn MinLoCord MaxHiCord MaxSubmerge Is_Ogee
28.031500,34.448700,2.6,0, 60, 60, , , 0.95, 0, 0,0,,
 9482.32 9513.48 9524.37 9535.26 9546.15 9553.70 9557.04 9567.94 9578.83 9589.72
 9600.61 9611.50 9622.39 9629.46 9665.95 9687.73 9698.62 9742.18 9763.96 9796.50
 9827.66 9862.40 9862.4010179.4910190.4810190.4810243.0410389.5010462.9210536.34
10567.8110609.7610704.1610756.8610819.5310913.9311008.3311050.2811071.2611092.23
11134.1911144.6811165.6511186.6311197.1211218.1011228.5811254.1511270.5411287.31
11302.0011320.4611333.4711353.6111364.9411386.7611406.8911419.9211438.3611447.32
  321.70  320.81  318.45  315.58  313.42  312.76  311.65  306.82  302.89  300.87
  299.50  297.87  296.54  296.00  294.12  293.31  293.13  292.82  292.86  293.10
  293.60  293.47  293.47  292.43  293.04  293.04  291.33  285.63  283.20  281.67
  281.25  281.10  281.61  281.56  281.82  282.69  283.13  283.50  283.44  283.77
  283.99  283.82  284.19  284.14  284.46  284.28  284.59  284.55  284.90  284.87
  285.29  285.23  285.57  285.40  285.73  285.71  286.15  286.01  286.59  286.59
 -678.30 -679.19 -681.55 -684.42 -686.58 -687.24 -688.35 -693.18 -697.11 -699.13
 -700.50 -702.13 -703.46 -704.00 -705.88 -706.69 -706.87 -707.18 -707.14 -706.90
 -706.40 -706.53  288.47  287.43  288.04 -706.96 -708.67 -714.37 -716.80 -718.33
 -718.75 -718.90 -718.39 -718.44 -718.18 -717.31 -716.87 -716.50 -716.56 -716.23
 -716.01 -716.18 -715.81 -715.86 -715.54 -715.72 -715.41 -715.45 -715.10 -715.13
 -714.71 -714.77 -714.43 -714.60 -714.27 -714.29 -713.85 -713.99 -713.41 -713.41
 9482.32 9513.48 9524.37 9535.26 9546.15 9553.70 9557.04 9567.94 9578.83 9589.72
 9622.39 9633.28 9665.95 9687.73 9698.62 9742.18 9763.96 9796.50 9825.40 9825.40
 9827.6610153.4810153.4810179.4910191.1210201.5010243.0410389.5010462.9210536.34
10567.8110609.7610704.1610756.8610819.5310913.9311008.3311050.2811071.2611092.23
11134.1911144.6811165.6511186.6311197.1211218.1011228.5811254.1511270.5411287.31
11302.0011320.4611333.4711353.6111364.9411386.7611406.8911419.9211438.3611447.32
  321.70  320.81  318.45  315.58  313.42  312.76  311.65  306.82  302.89  300.87
  296.54  295.76  294.12  293.31  293.13  292.82  292.86  293.10  293.56  293.56
  293.60  292.51  292.51  292.43  293.07  292.76  291.33  285.63  283.20  281.67
  281.25  281.10  281.61  281.56  281.82  282.69  283.13  283.50  283.44  283.77
  283.99  283.82  284.19  284.14  284.46  284.28  284.59  284.55  284.90  284.87
  285.29  285.23  285.57  285.40  285.73  285.71  286.15  286.01  286.59  286.59
 -678.30 -679.19 -681.55 -684.42 -686.58 -687.24 -688.35 -693.18 -697.11 -699.13
 -703.46 -704.24 -705.88 -706.69 -706.87 -707.18 -707.14 -706.90 -706.44  288.56
  288.60  287.51 -707.49 -707.57 -706.93 -707.24 -708.67 -714.37 -716.80 -718.33
 -718.75 -718.90 -718.39 -718.44 -718.18 -717.31 -716.87 -716.50 -716.56 -716.23
 -716.01 -716.18 -715.81 -715.86 -715.54 -715.72 -715.41 -715.45 -715.10 -715.13
 -714.71 -714.77 -714.43 -714.60 -714.27 -714.29 -713.85 -713.99 -713.41 -713.41
Pier Skew, UpSta & Num, DnSta & Num=  ,9943.42, 2 ,9906.42, 2 , 0 , 0 , 0 ,,
    4.00    4.00
 -706.80  293.20
    4.00    4.00
 -706.68  293.32
Pier Skew, UpSta & Num, DnSta & Num=  ,10026.44, 2 ,9989.44, 2 , 0 , 0 , 0 ,,
    4.00    4.00
 -707.07  292.93
    4.00    4.00
 -706.95  293.05
Pier Skew, UpSta & Num, DnSta & Num=  ,10109.46, 2 ,10072.46, 2 , 0 , 0 , 0 ,,
    4.00    4.00
 -707.34  292.66
    4.00    4.00
 -707.22  292.78
BR Coef=-1 , 0 , 0 ,, 0 ,,,0.8,0,1,0,
WSPro=,,,, 1 ,,,, 0 ,,,, 0 ,,,,-1 ,-1 ,-1 , 0 , 0 , 0 , 0 , 0
BC Design=,, 0 ,, 0 ,,,,,,

Type RM Length L Ch R = 1 ,120433.7,46.706800,46.706800,46.706800
XS GIS Cut Line= 6
474156.612296776741076.128478289474018.074876845741419.511238322
473905.227654636741764.129293874473604.012376904 742745.03207165
473166.046937764743951.610496327473381.324715525745659.943829671
#Sta/Elev= 30
 9476.96310.89439637.491295.26659820.805289.92299842.372280.56189874.057 279.176
9905.624281.13219937.192273.12669947.714267.37259979.282263.809310000.33268.9146
10042.42263.980310063.46264.811110137.12290.386510189.73281.920210430.45279.9777
10451.37281.951110493.21279.455111099.95286.351611352.96285.273911714.66287.7745
11735.94290.868612384.88289.543712956.39299.790513661.93306.261513672.01308.4631
14024.78320.805714034.86323.501914135.65 328.89714145.73331.521714241.42332.1535
#Mann= 3 , 0 , 0
 9476.96  0.0618       0 9476.96  0.0618       014241.42  0.0618       0
#XS Ineff= 2 , 0
       09870.388        10182.27       0
Bank Sta=9476.96,14241.42
Exp/Cntr=0.3,0.1

Type RM Length L Ch R = 1 ,  120387,213.237900,213.237900,213.237900
XS GIS Cut Line= 6
474131.951657085 741066.64361687473383.399995208742594.548697487
473007.965967417743156.614669695472623.851384073  743447.4132808
472539.215967417743918.333419695472593.035411865744206.093836367
#Sta/Elev= 30
9470.331309.87099596.648297.31639773.845 287.3929834.428279.75139879.006280.2289
9923.584275.80959945.873266.82749979.307263.686310012.74265.901310057.32 262.495
10113.04286.723710135.33288.885310158.97283.984210258.13 281.24410348.59283.9434
 10755.7280.512910913.18286.349410981.87283.542711390.61287.812911404.77285.1516
11486.81290.8928 11548.8304.690611655.17308.189811751.38306.8722 11763.4303.9398
11799.48280.290311835.56289.009912410.13287.203812521.89283.920613102.51295.5886
#Mann= 3 , 0 , 0
9470.331  0.0612       09470.331  0.0612       013102.51  0.0612       0
#XS Ineff= 2 , 0
       09872.629        10181.17       0
Bank Sta=9470.331,13102.51
Exp/Cntr=0.3,0.1

Type RM Length L Ch R = 3 ,  120299,,,
BEGIN DESCRIPTION:
END DESCRIPTION:
Bridge Culvert--1,0,-1,-1, 0
Deck Dist Width WeirC Skew NumUp NumDn MinLoCord MaxHiCord MaxSubmerge Is_Ogee
60.198950,92.840000,2.6,0, 60, 60, , , 0.95, 0, 0,0,,
 9457.28 9513.67 9535.56 9560.67 9560.6710156.2010156.2010228.1910269.9810295.84
10318.3910391.2410403.4910415.7410427.9910437.0010454.3110464.7310476.9810488.95
10513.7210540.9110660.7010685.1910770.9310783.1810868.9110893.4110942.4011008.53
11025.8511064.8811089.3711101.6211113.8711150.6111181.7211233.6811248.6011297.59
11320.2811346.5811383.3211395.5711456.8111554.7911640.5311665.0211738.5111799.75
11822.5411865.1911888.8711935.0712005.3112031.6112073.6912097.3512150.7012242.27
  323.30  321.07  320.35  319.78  319.78  306.27  306.27  304.78  304.04  303.93
  303.64  302.31  302.21  301.76  301.72  301.40  301.04  301.05  300.58  300.58
  300.08  299.81  297.53  296.97  295.47  295.17  293.81  293.23  292.38  291.01
  290.79  290.04  289.68  289.65  289.35  288.88  288.62  288.41  288.22  288.00
  288.00  287.81  287.83  287.71  287.83  287.46  287.57  287.45  287.66  288.15
  288.51  288.90  289.28  289.76  290.17  290.48  290.73  291.02  290.90  291.37
 -676.70 -678.93 -679.65 -680.22  313.78  300.27 -693.73 -695.22 -695.96 -696.07
 -696.36 -697.69 -697.79 -698.24 -698.28 -698.60 -698.96 -698.95 -699.42 -699.42
 -699.92 -700.19 -702.47 -703.03 -704.53 -704.83 -706.19 -706.77 -707.62 -708.99
 -709.21 -709.96 -710.32 -710.35 -710.65 -711.12 -711.38 -711.59 -711.78 -712.00
 -712.00 -712.19 -712.17 -712.29 -712.17 -712.54 -712.43 -712.55 -712.34 -711.85
 -711.49 -711.10 -710.72 -710.24 -709.83 -709.52 -709.27 -708.98 -709.10 -708.63
 9457.28 9490.17 9526.30 9526.30 9535.5610121.8310121.8310183.0910269.9810295.84
10318.3910391.2410403.4910415.7410427.9910437.0010454.3110464.7310476.9810488.95
10513.7210540.9110660.7010685.1910770.9310783.1810868.9110893.4110942.4011008.53
11025.8511064.8811089.3711101.6211113.8711150.6111181.7211233.6811248.6011297.59
11320.2811346.5811383.3211395.5711456.8111554.7911640.5311665.0211738.5111799.75
11822.5411865.1911888.8711935.0712005.3112031.6112073.6912097.3512150.7012242.27
  323.30  321.95  320.65  320.65  320.35  307.05  307.05  305.69  304.04  303.93
  303.64  302.31  302.21  301.76  301.72  301.40  301.04  301.05  300.58  300.58
  300.08  299.81  297.53  296.97  295.47  295.17  293.81  293.23  292.38  291.01
  290.79  290.04  289.68  289.65  289.35  288.88  288.62  288.41  288.22  288.00
  288.00  287.81  287.83  287.71  287.83  287.46  287.57  287.45  287.66  288.15
  288.51  288.90  289.28  289.76  290.17  290.48  290.73  291.02  290.90  291.37
 -676.70 -678.05 -679.35  314.65  314.35  301.05 -692.95 -694.31 -695.96 -696.07
 -696.36 -697.69 -697.79 -698.24 -698.28 -698.60 -698.96 -698.95 -699.42 -699.42
 -699.92 -700.19 -702.47 -703.03 -704.53 -704.83 -706.19 -706.77 -707.62 -708.99
 -709.21 -709.96 -710.32 -710.35 -710.65 -711.12 -711.38 -711.59 -711.78 -712.00
 -712.00 -712.19 -712.17 -712.29 -712.17 -712.54 -712.43 -712.55 -712.34 -711.85
 -711.49 -711.10 -710.72 -710.24 -709.83 -709.52 -709.27 -708.98 -709.10 -708.63
Pier Skew, UpSta & Num, DnSta & Num=  ,9658.59, 2 ,9624.23, 2 , 0 , 0 , 0 ,,
    4.00    4.00
 -682.44  317.56
    4.00    4.00
 -681.66  318.34
Pier Skew, UpSta & Num, DnSta & Num=  ,9758.52, 2 ,9724.15, 2 , 0 , 0 , 0 ,,
    4.00    4.00
 -684.71  315.29
    4.00    4.00
 -683.93  316.07
Pier Skew, UpSta & Num, DnSta & Num=  ,9858.44, 2 ,9824.07, 2 , 0 , 0 , 0 ,,
    4.00    4.00
 -686.98  313.02
    4.00    4.00
 -686.20  313.80
Pier Skew, UpSta & Num, DnSta & Num=  ,9958.36, 2 ,9923.99, 2 , 0 , 0 , 0 ,,
    4.00    4.00
 -689.24  310.76
    4.00    4.00
 -688.46  311.54
Pier Skew, UpSta & Num, DnSta & Num=  ,10058.28, 2 ,10023.91, 2 , 0 , 0 , 0 ,,
    4.00    4.00
 -691.51  308.49
    4.00    4.00
 -690.73  309.27
BR Coef=-1 , 0 , 0 ,, 0 ,,,0.8,0,1,0,
WSPro=,,,, 1 ,,,, 0 ,,,, 0 ,,,,-1 ,-1 ,-1 , 0 , 0 , 0 , 0 , 0
BC Design=,, 0 ,, 0 ,,,,,,

Type RM Length L Ch R = 1 ,120173.7,1056.410100,1056.410100,1056.410100
XS GIS Cut Line= 5
473963.632517259741001.905486174473616.165154666741716.776863322
473192.427772969742338.472308606472495.813189656743236.909808591
472363.434717447743927.013975263
#Sta/Elev= 30
9434.613 321.9849482.529320.82189527.003309.9208 9638.19302.35919660.428295.1889
9882.801295.76469938.395267.44919960.632263.80999993.988266.681310027.34261.4374
10105.17284.510510116.29284.973410160.77281.653510299.92284.837110360.43281.7134
10783.99284.346911091.31280.936511306.43292.079711395.01304.677111546.85310.1623
11679.38306.0051 11858.9284.5001 11940.5282.564112177.84281.624612249.11290.2187
12412.03292.383512452.76291.311212503.67283.689712636.04289.951412821.38 287.751
#Mann= 3 , 0 , 0
9434.613  0.0619       09434.613  0.0619       012821.38  0.0619       0
#XS Ineff= 2 , 0
       09902.174        10128.68       0
Bank Sta=9434.613,12821.38
Exp/Cntr=0.3,0.1

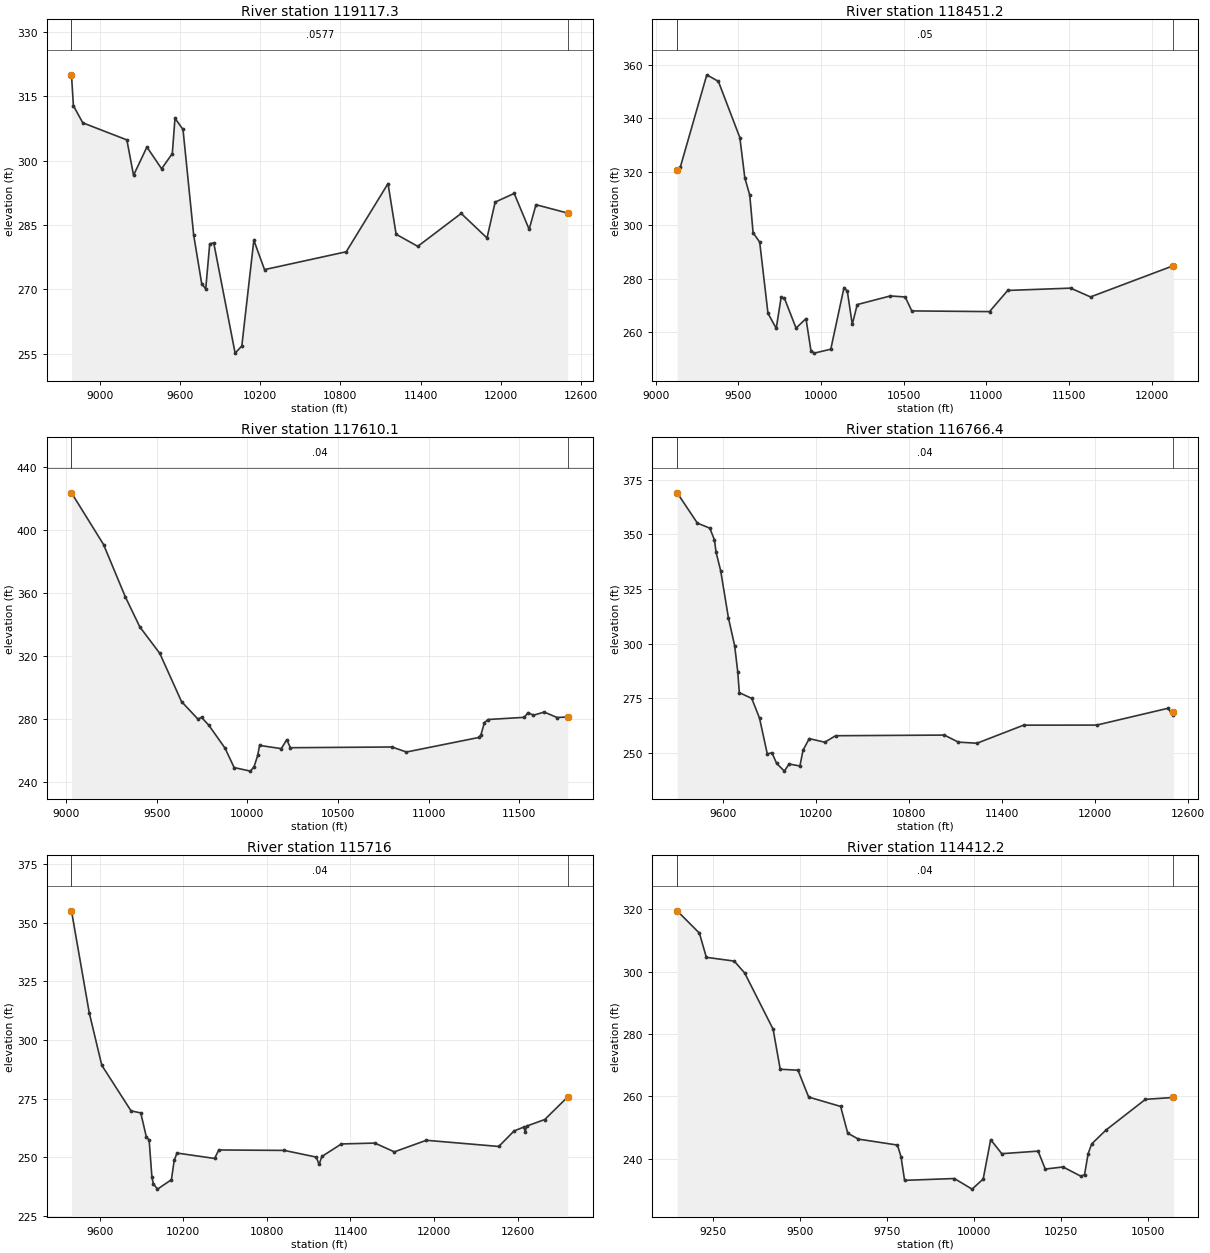
Type RM Length L Ch R = 1 ,119117.3,666.113700,666.113700,666.113700
XS GIS Cut Line= 6
472653.049102717740240.582296185472663.324470547741484.337080832
472660.496840584741726.505772399472640.623414289742096.162307005
472568.257952792742701.630989589 472345.33303656743928.696615973
#Sta/Elev= 30
8787.648320.00518802.066312.81018872.067308.81929202.075304.83769252.077296.5931
9352.082303.17849462.087298.1095 9542.09301.66179562.091309.87759622.094307.2714
9702.098282.6423  9762.1271.32919792.102270.09849822.103280.60959852.104280.8443
10012.11255.143810062.11256.796510152.12281.457510232.12 274.60510843.59278.7704
11156.14294.656411216.75282.851511378.75280.028811703.49287.699411896.83281.9789
11957.89 290.34612100.35292.362512212.28283.987312263.16289.737812500.96287.7785
#Mann= 3 , 0 , 0
8787.648  0.0577       08787.648  0.0577       012500.96  0.0577       0
#XS Ineff= 2 , 0
       09862.121        10156.28       0
Bank Sta=8787.648,12500.96
Exp/Cntr=0.3,0.1

Type RM Length L Ch R = 1 ,118451.2,841.051200,841.051200,841.051200
XS GIS Cut Line= 6
472000.157045809740585.669003881471995.788848467741837.801881965
471977.318622852742486.559652018471964.146114168742794.261021554
471949.612076711743027.877680326471899.169985565743584.330996119
#Sta/Elev= 30
9129.993320.78759149.325321.77159309.325356.29179379.326353.85079509.327332.7947
9539.327317.74749569.327 311.2319589.327297.19529629.327 293.6819679.328267.0465
9729.328261.39649759.328273.11169779.328272.59979849.329261.49159909.329265.0451
9939.329253.05049959.329252.123310059.33253.596810139.33276.648710159.33275.3266
10189.33262.886610219.33270.300210419.34273.521110509.36273.153610549.37267.9269
 11019.6267.667111129.69275.587111510.22276.451711630.53273.162112131.97284.8559
#Mann= 3 , 0 , 0
9129.993    0.05       09129.993    0.05       012131.97    0.05       0
#XS Ineff= 2 , 0
       09797.456        10147.05       0
Bank Sta=9129.993,12131.97
Exp/Cntr=0.3,0.1

Type RM Length L Ch R = 1 ,117610.1,843.784900,843.784900,843.784900
XS GIS Cut Line= 2
471139.060866058740478.127869442471187.671977162743214.238980561
#Sta/Elev= 30
9030.139423.58249207.039390.71949327.058357.48589407.071338.37819517.088321.5677
9637.107290.91049727.122279.85059747.125280.89419787.131275.95919877.145261.2894
9927.153248.999710017.17 246.73810037.17 249.59810057.17256.732310067.18263.0954
10187.19261.0305 10217.2266.7299 10237.2261.618810797.29262.0781 10877.3258.8846
11277.37 268.15311287.37269.579111307.37277.589811327.37279.543111527.41 280.919
11547.41283.928411577.41 282.27611637.42284.269711707.43280.814511766.68281.1532
#Mann= 3 , 0 , 0
9030.139    0.04       09030.139    0.04       011766.68    0.04       0
#XS Ineff= 2 , 0
       0                10217.63       0
Bank Sta=9030.139,11766.68
Exp/Cntr=0.3,0.1

Type RM Length L Ch R = 1 ,116766.4,1050.386800,1050.386800,1050.386800
XS GIS Cut Line= 2
470305.727532715740644.794536114470437.671977192743839.238980576
#Sta/Elev= 30
9307.255369.02259437.572355.1771 9517.64352.86369547.665347.49929557.674341.9623
  9587.7333.37179637.742 311.7989677.776 299.1069697.793287.07849707.802277.6545
 9787.87 275.0099837.913265.98989887.955249.61859917.981250.17629948.007245.3057
9998.049241.753410028.07245.025610098.13244.097110118.15251.289210158.19256.6265
10258.27254.980410328.33257.942311028.93 258.239   11119255.008311239.11254.5212
11539.36262.776712009.76262.807412470.16270.507612500.18267.294812504.42 268.604
#Mann= 3 , 0 , 0
9307.255    0.04       09307.255    0.04       012504.42    0.04       0
#XS Ineff= 2 , 0
       0                10713.05       0
Bank Sta=9307.255,12504.42
Exp/Cntr=0.3,0.1

Type RM Length L Ch R = 1 ,  115716,1303.768000,1303.768000,1303.768000
XS GIS Cut Line= 2
 469319.61642161740547.572313905469389.060866058 744110.07231389
#Sta/Elev= 30
9396.865355.14369524.316311.67649614.334289.25939824.373269.79779894.387268.8996
9934.394258.66399954.398257.37089974.402241.50539984.404238.707610014.41236.3885
10114.43240.401410134.43248.672810154.44251.785410424.49249.474610454.49 253.098
10924.58252.911711154.63250.060711174.63 246.90411194.63250.317311334.66255.6658
11574.71256.041311714.73252.296111944.78257.232912464.88254.5965 12574.9261.2241
12644.91262.883712654.91   260.812664.91263.286712794.94266.089612960.04 275.749
#Mann= 3 , 0 , 0
9396.865    0.04       09396.865    0.04       012960.04    0.04       0
#XS Ineff= 2 , 0
       0                10581.39       0
Bank Sta=9396.865,12960.04
Exp/Cntr=0.3,0.1

Type RM Length L Ch R = 1 ,114412.2,928.068100,928.068100,928.068100
XS GIS Cut Line= 6
 468205.20072785740541.154200032468195.375186324740736.233507663
468061.008139133741386.264288634468031.669130057741461.708754003
468017.058851451741507.652943075 467913.36642161741932.988980561
#Sta/Elev= 30
9148.081319.56379212.008312.40569232.033304.63399312.135303.42929342.173299.6042
 9423.84 281.5549444.262 268.7119495.319268.39649525.954 259.7789617.856256.7624
9638.279248.19279668.913 246.2769781.239244.3608 9791.45240.58299801.662233.0352
9944.621233.62269995.678230.2167 10027.5233.461710049.06246.0988   10081241.5935
10185.35242.419810205.91 236.66110256.97237.332710308.47234.357310318.77234.8444
10329.07 241.57210339.37 244.74310380.57249.196410493.87259.0467 10574.2259.6443
#Mann= 3 , 0 , 0
9148.081    0.04       09148.081    0.04       0 10574.2    0.04       0
#XS Ineff= 2 , 0
       09755.884           10414       0
Bank Sta=9148.081,10574.2
Exp/Cntr=0.3,0.1

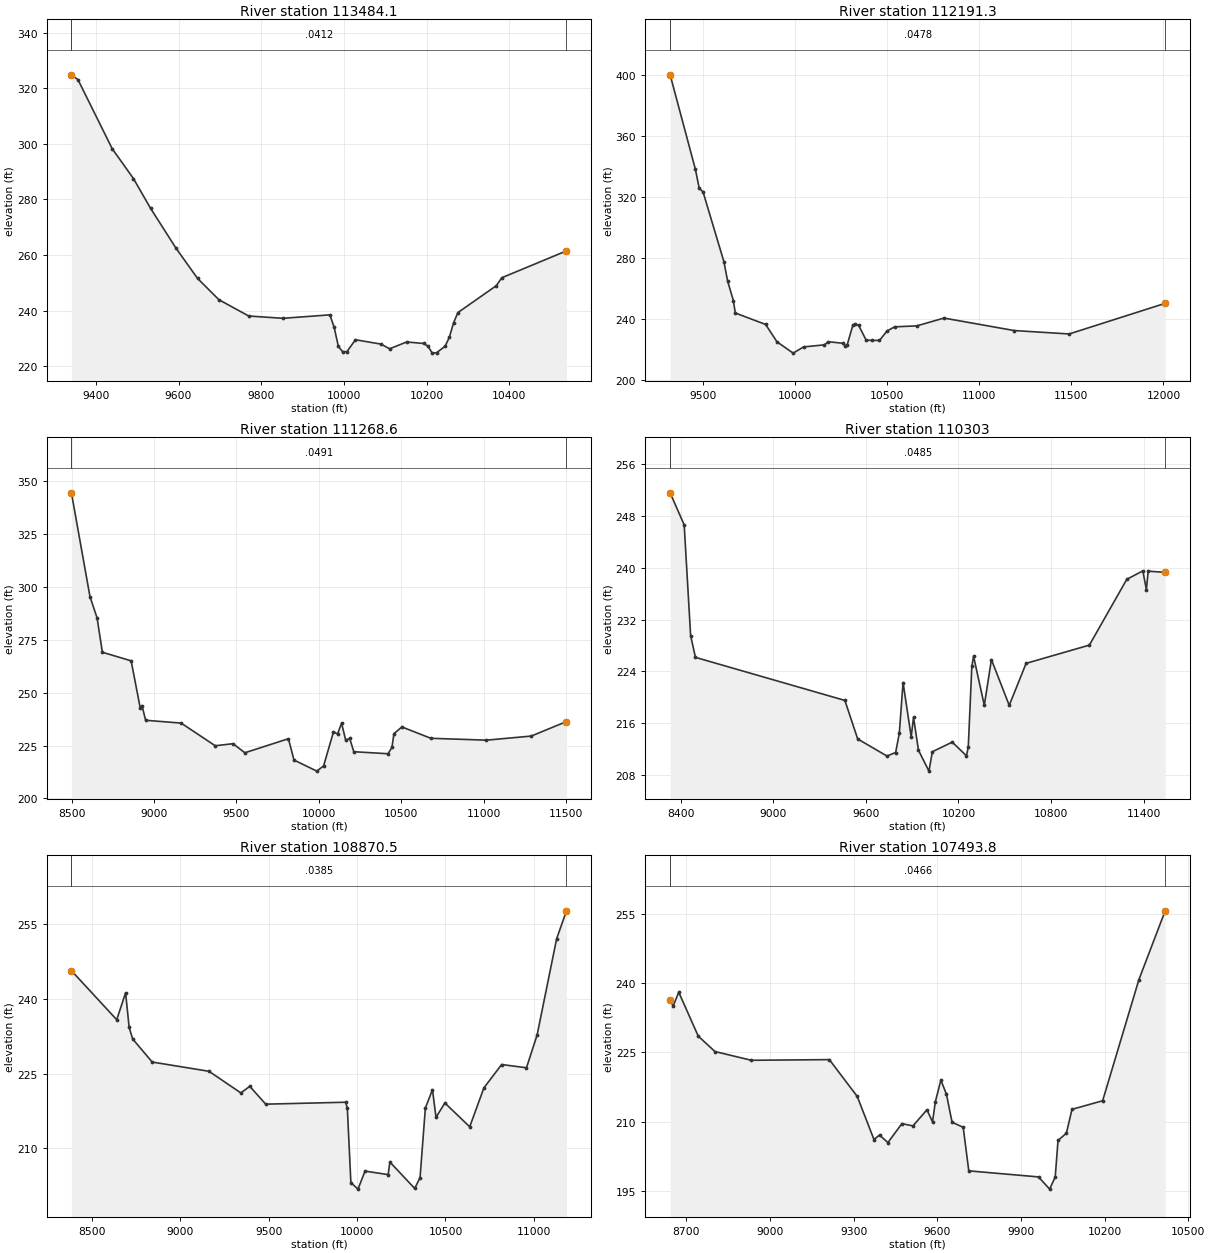
Type RM Length L Ch R = 1 ,113484.1,1292.858200,1292.858200,1292.858200
XS GIS Cut Line= 2
467005.380310506 740639.58620277 467303.99142164741799.308425009
#Sta/Elev= 30
 9340.81324.84339356.726323.09059439.336298.29939490.967287.50739532.271276.8255
9594.228262.39749645.859251.6297 9697.49243.96249769.773238.09119852.383237.2668
9965.971238.50459976.297234.09879986.623227.12929996.949225.239210007.28225.2738
10027.93 229.55310089.88227.980910110.54226.300410151.84228.752710193.15228.2088
10203.47227.2141 10213.8224.740210224.12224.880610244.78  227.21 10255.1230.4413
10265.43235.702510275.76239.325710368.69248.996410381.99251.860310538.36261.5122
#Mann= 3 , 0 , 0
 9340.81  0.0412       0 9340.81  0.0412       010538.36  0.0412       0
#XS Ineff= 2 , 0
       0                               0
Bank Sta=9340.81,10538.36
Exp/Cntr=0.3,0.1

Type RM Length L Ch R = 1 ,112191.3,922.651200,922.651200,922.651200
XS GIS Cut Line= 2
466015.796977162740441.669536114466656.421977162743051.044536129
#Sta/Elev= 30
9322.672400.09159459.962338.04619480.556325.6779 9501.15323.41049614.417277.6276
9635.011264.70739665.902252.11029676.199243.9526 9840.95236.44299902.732225.0353
 9990.39217.641310046.89221.715710160.16223.070610180.75225.112910263.13224.0787
10273.42222.181710283.72 223.06910314.61236.070610324.91236.5541 10345.5235.8758
10386.69226.154510417.58225.983410458.77225.969710499.96232.151310541.14234.8787
10661.45235.504210808.86240.625911189.85232.446811488.46 230.20512009.54250.2899
#Mann= 3 , 0 , 0
9322.672  0.0478       09322.672  0.0478       012009.54  0.0478       0
#XS Ineff= 2 , 0
       09910.785        10778.76       0
Bank Sta=9322.672,12009.54
Exp/Cntr=0.3,0.1

Type RM Length L Ch R = 1 ,111268.6,965.611000,965.611000,965.611000
XS GIS Cut Line= 6
464753.768233223 740389.96916129  464934.4456786740820.249927086
465103.614259515741133.876469637 465709.43679125 741975.86148643
465889.359916618742262.691996539466226.903827946742989.776163144
#Sta/Elev= 30
8499.072344.50028611.681295.39418654.567285.39588686.823269.11938861.289265.0542
8916.201 242.8328927.184243.87128949.149236.95239164.414235.62199371.142224.9042
9479.075225.87399550.874221.5874 9815.01228.23389848.682218.15059987.149212.9069
10028.39 215.37910088.15231.477110112.78230.4701 10137.4235.592210162.03227.5879
10186.66228.367910211.28222.086410419.08221.131310442.53224.095510455.08230.6264
10503.08233.803910678.44228.433911015.74227.5486 11287.2229.482311500.94236.3355
#Mann= 3 , 0 , 0
8499.072  0.0491       08499.072  0.0491       011500.94  0.0491       0
#XS Ineff= 2 , 0
       09614.677        10553.12       0
Bank Sta=8499.072,11500.94
Exp/Cntr=0.3,0.1

Type RM Length L Ch R = 1 ,  110303,1432.475500,1432.475500,1432.475500
XS GIS Cut Line= 6
464196.352532744740737.676480561464555.127514452 741974.74801816
464652.415355384742183.569220394464742.680014879742262.714768216
464902.834241807742328.969798937466110.415032715743025.002869442
#Sta/Elev= 30
8331.939251.59278423.006 246.6388464.721229.52168496.007226.15969464.257219.5045
9547.308213.54669737.011210.9111 9793.34211.45399817.035214.43779841.234 222.275
9893.989213.88599909.149216.88989941.082211.811310009.09208.576710031.17211.5757
10159.98213.058510252.32210.942510263.86212.293110286.95224.767110298.19226.3234
10367.74218.751810413.91225.809510529.33 218.74610638.62225.233511048.73228.0566
11291.12238.2242   11395239.530411418.08 236.62211429.62239.486311539.75239.2954
#Mann= 3 , 0 , 0
8331.939  0.0485       08331.939  0.0485       011539.75  0.0485       0
#XS Ineff= 2 , 0
       09369.742        10622.25       0
Bank Sta=8331.939,11539.75
Exp/Cntr=0.3,0.1

Type RM Length L Ch R = 1 ,108870.5,1376.780800,1376.780800,1376.780800
XS GIS Cut Line= 2
463614.755310506740659.551480561 463866.49142161743450.350091666
#Sta/Elev= 30
 8382.66 245.6438639.146235.80968689.349241.2066 8709.43234.25868729.511231.9479
8839.958227.32689161.257225.47549341.988221.13659392.191 222.4579482.556218.8854
9934.383219.27199944.424218.15929964.505203.173310004.67 201.85410044.83205.4659
10175.36204.7635 10185.4207.283610325.97201.986410356.09 204.15810386.21218.1222
10426.37221.785110446.45216.246310496.66219.122410637.22214.344110717.55222.1528
10817.96226.827910958.52226.180111018.77232.760811129.21252.029411184.79257.6374
#Mann= 3 , 0 , 0
 8382.66  0.0385       0 8382.66  0.0385       011184.79  0.0385       0
#XS Ineff= 2 , 0
       09867.295         10479.7       0
Bank Sta=8382.66,11184.79
Exp/Cntr=0.3,0.1

Type RM Length L Ch R = 1 ,107493.8,1130.559000,1130.559000,1130.559000
XS GIS Cut Line= 2
462807.923394948741584.114717171 462772.74142161743359.204258338
#Sta/Elev= 30
8641.865236.42668652.752235.07228672.756238.0684 8742.77228.53678802.782225.1971
8932.807223.30619212.862223.44679312.882215.46259372.894206.11159392.898207.0805
9422.904205.44589472.914209.54989512.921209.07199562.931212.56539582.935209.9305
9592.937214.27349612.941 219.0029632.945215.90389652.949209.86239692.957 208.759
9712.961199.3076 9963.01197.991310003.02 195.34210023.02197.997910033.02205.9239
10063.03207.464710083.03212.653910193.05214.522610323.08240.7991 10417.3255.7374
#Mann= 3 , 0 , 0
8641.865  0.0466       08641.865  0.0466       0 10417.3  0.0466       0
#XS Ineff= 2 , 0
       09626.267                       0
Bank Sta=8641.865,10417.3
Exp/Cntr=0.3,0.1