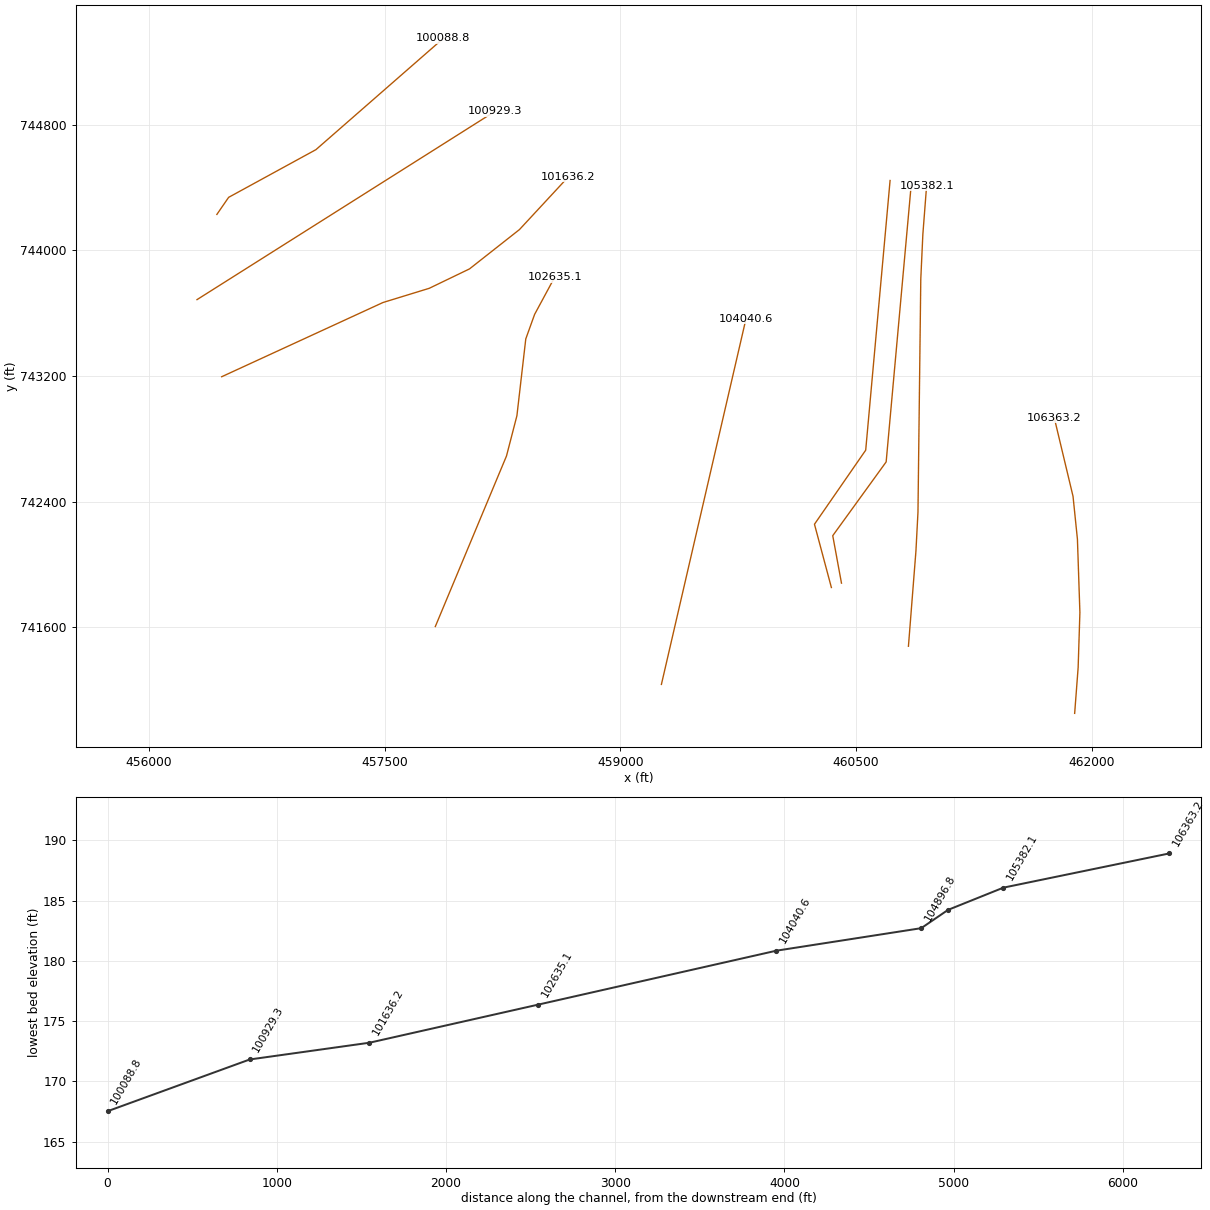
HEC-RAS study 2549_ras.prj: 2549

--- 2549_ras.g01 (geometry) --- (continued)

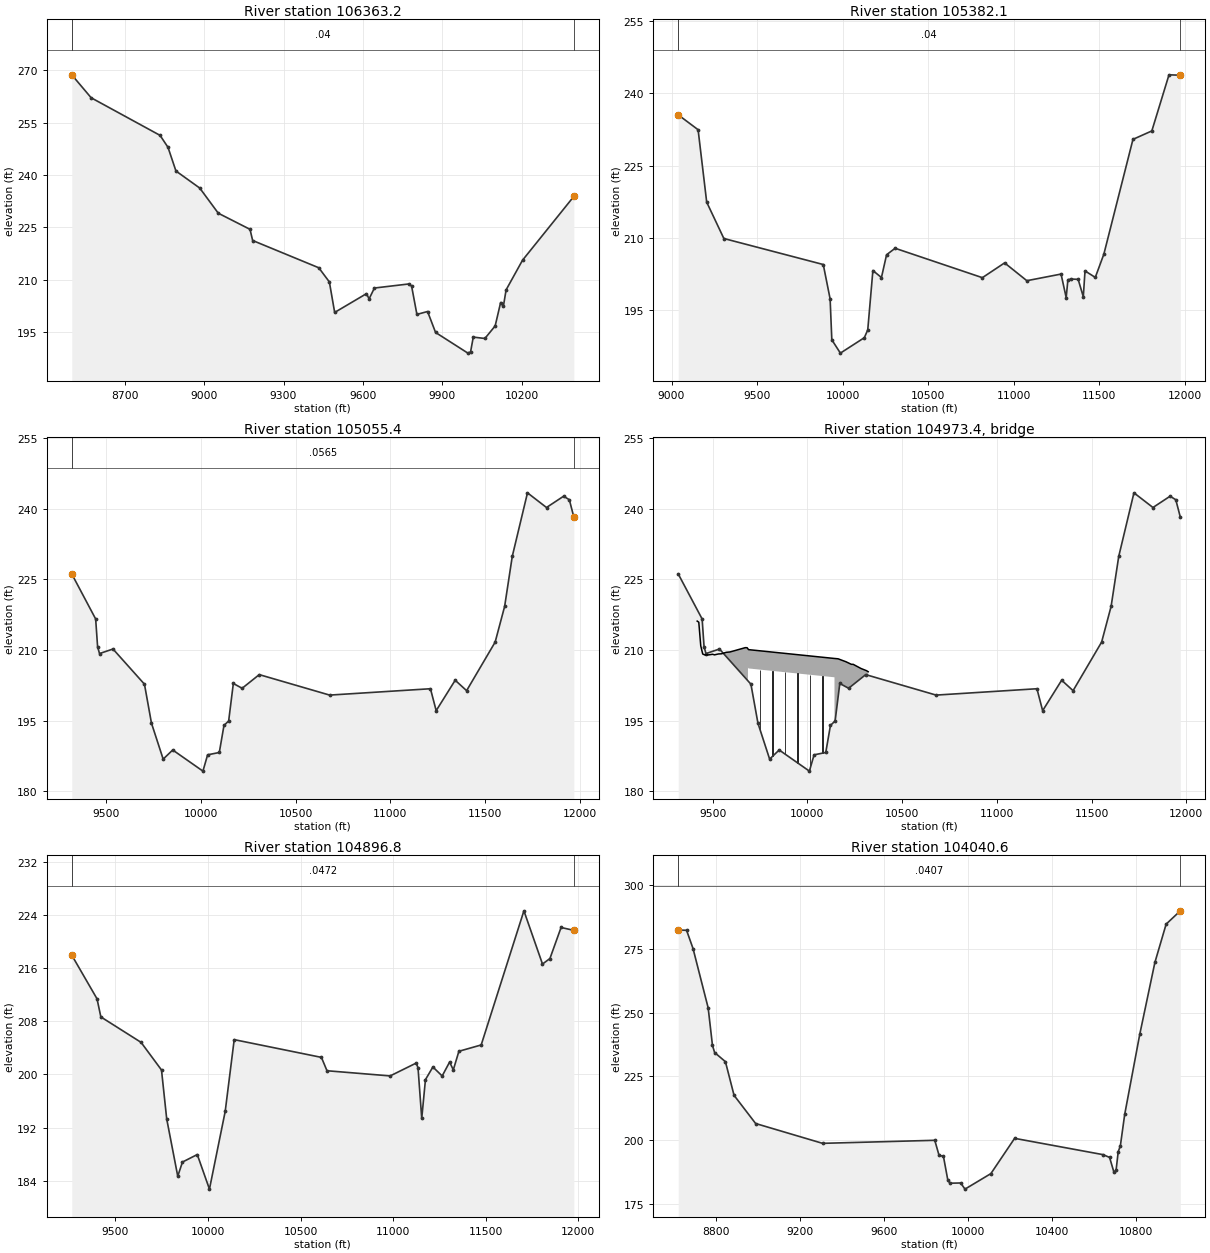
Type RM Length L Ch R = 1 ,106363.2,981.085200,981.085200,981.085200
XS GIS Cut Line= 6
461892.403303443741051.969858581461914.570515838741343.512138496
461925.749700506741694.233014553461910.047813955742160.116712391
461882.062772522742433.371690135461762.571630819742933.608807107
#Sta/Elev= 30
8499.073268.68828572.352262.11438832.996251.33558863.026 247.9098893.055241.1261
8983.141236.23059053.152229.02889173.166224.40669183.166221.20589433.249213.3915
9473.302209.33099493.335200.58929613.539205.96749623.574204.48019643.643207.5853
9774.093208.75399784.179208.19059804.351200.02199844.696200.85679874.955194.8504
 9997.18188.927910007.32189.272410017.54  193.5210061.45193.126610100.33196.7244
10121.02203.429910131.37202.317610141.72207.060910203.81215.5584 10397.9233.8445
#Mann= 3 , 0 , 0
8499.073    0.04       08499.073    0.04       0 10397.9    0.04       0
#XS Ineff= 2 , 0
       09610.596                       0
Bank Sta=8499.073,10397.9
Exp/Cntr=0.3,0.1

Type RM Length L Ch R = 1 ,105382.1,326.682200,326.682200,326.682200
XS GIS Cut Line= 6
460834.401962161741479.284868628 460882.17327705742086.197512642
460895.065318197742332.700995773460912.998352677743816.544198051
460926.216364235 744102.05252935460950.109929621744410.939386472
#Sta/Elev= 30
 9039.08235.53139155.248232.44599205.443217.41719305.785209.87329887.016204.4717
9927.029197.3458 9937.03188.85159987.048186.0854 10127.1189.2884 10147.1 190.909
10177.12203.225410227.14201.773410257.15206.501210307.17 207.84710817.23201.7433
10947.23204.812411077.23201.114711277.27202.492411307.27197.607611317.28201.3181
11337.28 201.46311377.29201.393711407.31197.778711417.32203.148611477.37201.7997
11527.41206.615911697.68230.449511807.95232.195611908.29243.839611974.48243.7614
#Mann= 3 , 0 , 0
 9039.08    0.04       0 9039.08    0.04       011974.48    0.04       0
#XS Ineff= 2 , 0
       09738.061        10238.57       0
Bank Sta=9039.08,11974.48
Exp/Cntr=0.3,0.1

Type RM Length L Ch R = 1 ,105055.4,158.602600,158.602600,158.602600
XS GIS Cut Line= 4
460408.149901539741880.937724441460352.594345987 742183.02105777
460692.554043502742652.540752232460851.345273942744408.744616359
#Sta/Elev= 30
9318.283226.17589444.425216.59579454.593210.69099464.761209.24579535.935210.2102
9701.952202.7299 9738.99194.44389800.721186.7954  9851.2 188.737 10010.6184.2413
 10035.3187.705610097.03188.206210121.72193.964910146.41194.9087 10171.1202.8798
10217.62201.860510307.98204.766210679.49200.411111211.65201.763511241.78197.0989
11342.18203.572311402.43 201.35311553.04211.677111603.24219.285411643.41229.9044
11723.73243.427811824.14240.305111914.51 242.70711944.63241.957311968.47238.2715
#Mann= 3 , 0 , 0
9318.283  0.0565       09318.283  0.0565       011968.47  0.0565       0
#XS Ineff= 2 , 0
       09687.866         10264.8       0
Bank Sta=9318.283,11968.47
Exp/Cntr=0.3,0.1

Type RM Length L Ch R = 3 ,104973.4,,,
BEGIN DESCRIPTION:
END DESCRIPTION:
Bridge Culvert--1,0,-1,-1, 0
Deck Dist Width WeirC Skew NumUp NumDn MinLoCord MaxHiCord MaxSubmerge Is_Ogee
56.431300,45.740000,2.6,0, 26, 26, , , 0.95, 0, 0,0,,
 9418.29 9426.76 9437.13 9447.51 9457.89 9478.64 9499.39 9509.77 9530.52 9546.07
 9571.88 9591.90 9671.99 9681.85 9686.22 9686.22 9689.2010142.9910142.9910162.01
10203.7710231.8610241.9010282.9410312.2410321.00
  216.15  215.91  210.88  209.15  208.96  208.96  209.09  208.97  209.16  209.19
  209.51  209.59  210.50  210.49  210.25  210.25  210.08  208.20  208.20  208.13
  207.50  206.96  206.95  206.07  205.60  205.38
 -783.85 -784.09 -789.12 -790.85 -791.04 -791.04 -790.91 -791.03 -790.84 -790.81
 -790.49 -790.41 -789.50 -789.51 -789.75  206.25  206.08  204.20 -791.80 -791.87
 -792.50 -793.04 -793.05 -793.93 -794.40 -794.62
 9418.29 9426.76 9437.13 9447.51 9457.89 9468.26 9499.39 9508.62 9520.15 9530.52
 9546.07 9571.88 9591.90 9671.99 9681.85 9689.20 9708.81 9708.8110165.5810165.58
10203.7710231.8610241.9010282.9410312.2410321.00
  216.15  215.91  210.88  209.15  208.96  208.94  209.09  208.97  209.02  209.16
  209.19  209.51  209.59  210.50  210.49  210.08  210.00  210.00  208.07  208.07
  207.50  206.96  206.95  206.07  205.60  205.38
 -783.85 -784.09 -789.12 -790.85 -791.04 -791.06 -790.91 -791.03 -790.98 -790.84
 -790.81 -790.49 -790.41 -789.50 -789.51 -789.92 -790.00  206.00  204.07 -791.93
 -792.50 -793.04 -793.05 -793.93 -794.40 -794.62
Pier Skew, UpSta & Num, DnSta & Num=  ,9750.40, 2 ,9772.99, 2 , 0 , 0 , 0 ,,
    3.00    3.00
 -790.17  209.83
    3.00    3.00
 -790.26  209.74
Pier Skew, UpSta & Num, DnSta & Num=  ,9816.08, 2 ,9838.67, 2 , 0 , 0 , 0 ,,
    3.00    3.00
 -790.44  209.56
    3.00    3.00
 -790.54  209.46
Pier Skew, UpSta & Num, DnSta & Num=  ,9881.76, 2 ,9904.35, 2 , 0 , 0 , 0 ,,
    3.00    3.00
 -790.71  209.29
    3.00    3.00
 -790.81  209.19
Pier Skew, UpSta & Num, DnSta & Num=  ,9947.44, 2 ,9970.03, 2 , 0 , 0 , 0 ,,
    3.00    3.00
 -790.99  209.01
    3.00    3.00
 -791.08  208.92
Pier Skew, UpSta & Num, DnSta & Num=  ,10013.12, 2 ,10035.71, 2 , 0 , 0 , 0 ,,
    3.00    3.00
 -791.26  208.74
    3.00    3.00
 -791.35  208.65
Pier Skew, UpSta & Num, DnSta & Num=  ,10078.81, 2 ,10101.39, 2 , 0 , 0 , 0 ,,
    3.00    3.00
 -791.53  208.47
    3.00    3.00
 -791.62  208.38
BR Coef=-1 , 0 , 0 ,, 0 ,,,0.8,0,1,0,
WSPro=,,,, 1 ,,,, 0 ,,,, 0 ,,,,-1 ,-1 ,-1 , 0 , 0 , 0 , 0 , 0
BC Design=,, 0 ,, 0 ,,,,,,

Type RM Length L Ch R = 1 ,104896.8,856.259200,856.259200,856.259200
XS GIS Cut Line= 4
460343.913790435 741853.15994668460236.274901539742255.937724456
460562.345710248742727.193530008460717.553147376744443.761254236
#Sta/Elev= 30
9263.696217.94949400.163211.37939420.865 208.6529638.234204.82039748.668 200.659
9776.752193.29539836.542184.66139861.874186.79759941.991187.9292 10007.8182.7219
10092.92194.418110141.56205.230110612.94202.559310643.06200.546610984.45 199.767
11125.02   201.711135.06201.004111155.14193.374411175.22199.205211215.39201.1132
11265.59199.759311305.76201.854711325.84200.681611355.96203.476711476.45204.4298
11707.39224.625511807.79216.612811847.96217.4428 11908.2222.120111977.24221.6817
#Mann= 3 , 0 , 0
9263.696  0.0472       09263.696  0.0472       011977.24  0.0472       0
#XS Ineff= 2 , 0
       09712.361        10262.52       0
Bank Sta=9263.696,11977.24
Exp/Cntr=0.3,0.1

Type RM Length L Ch R = 1 ,104040.6,1405.494800,1405.494800,1405.494800
XS GIS Cut Line= 2
 459261.99394092741236.341370285459800.188385367743562.730259165
#Sta/Elev= 30
 8622.54282.3288 8662.22 282.2368693.012275.05778764.861251.85538785.389237.1243
8795.654234.35138846.974230.76668888.031217.58738990.672206.55069308.859198.7877
9842.593199.97649863.121 194.0369883.649193.76149904.178184.60139914.442183.1714
9965.762183.2614 9986.29180.852210109.46 186.93110222.36200.743710643.19194.3551
10673.99193.269110694.51187.524510704.78188.164110715.04195.492410725.31197.8399
10745.83210.096210817.68241.567110889.53269.663210942.98284.652411010.37289.8602
#Mann= 3 , 0 , 0
 8622.54  0.0407       0 8622.54  0.0407       011010.37  0.0407       0
#XS Ineff= 2 , 0
       09714.838        10507.03       0
Bank Sta=8622.54,11010.37
Exp/Cntr=0.3,0.1

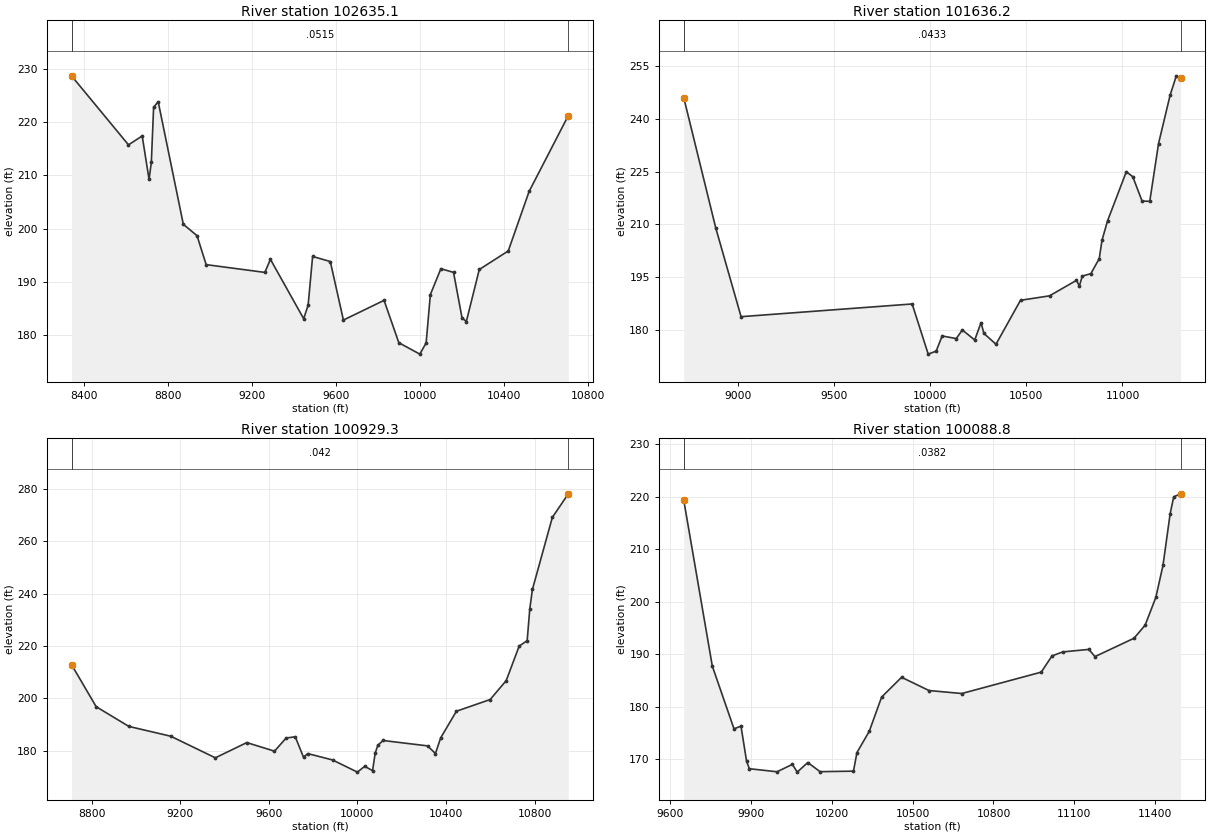
Type RM Length L Ch R = 1 ,102635.1,998.923200,998.923200,998.923200
XS GIS Cut Line= 6
457822.828614227741604.639255363 458276.03308412742690.525927016
458342.245902698 742946.42035055458398.707636005743435.343635784
458455.022449513743591.821294979458582.328410853743827.496102509
#Sta/Elev= 30
8339.152228.75398610.868215.76448676.233217.43828708.915209.27638719.809212.4741
8730.703222.83828752.492223.88388872.327200.81868937.691 198.6698981.268 193.223
9261.065 191.7619287.693194.21679446.298183.04389467.582185.60679488.866194.7642
9573.204 193.8069635.705182.79259829.582186.5015 9899.96178.527210000.16176.3811
10030.23178.497610050.29187.577710100.42192.453710160.84 191.765 10201.4183.2048
10221.89182.517610283.71192.309510421.78195.795210521.23206.9984 10708.1221.2699
#Mann= 3 , 0 , 0
8339.152  0.0515       08339.152  0.0515       0 10708.1  0.0515       0
#XS Ineff= 2 , 0
       09150.348                       0
Bank Sta=8339.152,10708.1
Exp/Cntr=0.3,0.1

Type RM Length L Ch R = 1 ,101636.2,706.875300,706.875300,706.875300
XS GIS Cut Line= 6
456463.272382259743194.778791979457489.978124052743667.240948111
457784.247543812743757.602141514458040.663695425743881.190437078
458358.575835675744131.514946654 458669.25305739 744466.53799212
#Sta/Elev= 30
8716.374245.91528882.879208.97429014.566183.83279905.171187.4366 9988.79173.2133
10030.24174.074310061.32178.365610134.67177.627710166.45180.054310230.96177.2248
10263.65182.1244 10278.8179.076110341.57176.019310469.19188.478810620.23189.7445
10760.63194.141610775.61192.514710790.59195.336810835.54196.044810879.04200.3001
 10893.4205.481810922.13210.984111019.91 224.93111053.63223.537811101.92216.6378
11142.07216.540511187.85232.943511248.04 246.65511280.42252.140811302.48251.5529
#Mann= 3 , 0 , 0
8716.374  0.0433       08716.374  0.0433       011302.48  0.0433       0
#XS Ineff= 2 , 0
       09384.752                       0
Bank Sta=8716.374,11302.48
Exp/Cntr=0.3,0.1

Type RM Length L Ch R = 1 ,100929.3,840.464300,840.464300,840.464300
XS GIS Cut Line= 2
456306.125391513743685.526766509458201.958724856744883.443433166
#Sta/Elev= 30
8709.593212.90838820.931196.8213  8968.5189.28779157.765185.53789358.858177.2886
9500.806183.10829625.922179.83199678.242184.83429719.526185.34559756.967177.4987
9775.688178.91559888.012176.473510000.34171.824310033.11174.0457 10068.6172.3895
10080.43 179.06210092.26182.064310115.92183.910410317.01181.8505 10352.5178.9237
10376.15184.919810447.13195.0879 10599.4199.554610671.88206.780910730.44219.9742
10766.51222.034910778.34 234.19310790.17241.599210880.21269.144710952.18278.1353
#Mann= 3 , 0 , 0
8709.593   0.042       08709.593   0.042       010952.18   0.042       0
#XS Ineff= 2 , 0
       09344.115        10170.94       0
Bank Sta=8709.593,10952.18
Exp/Cntr=0.3,0.1

Type RM Length L Ch R = 1 ,100088.8,109.264500,109.264500,109.264500
XS GIS Cut Line= 5
456432.509434432744227.886038184456507.280711263744336.528654709
456971.169600159744590.000876918457062.836266845744640.000876918
457874.123076737745348.685041964
#Sta/Elev= 30
9651.675219.28539757.426187.72369837.939175.76439863.794 176.2949884.649169.5616
9894.916168.17699997.475167.594410054.45169.008310072.35167.527210111.43169.3587
10157.01167.6129 10280.9167.712810293.76171.253810339.33175.289110385.27181.8229
10459.31185.5915   10561183.0672 10682.6182.500410977.15186.570911017.01189.6611
11056.82190.423111153.82 190.90211176.32 189.52911321.02193.022511362.21195.4986
11402.05200.7943 11428.6206.887411455.16216.746711468.44219.955311493.83220.5309
#Mann= 3 , 0 , 0
9651.675  0.0382       09651.675  0.0382       011493.83  0.0382       0
#XS Ineff= 2 , 0
       09834.985        10451.64       0
Bank Sta=9651.675,11493.83
Exp/Cntr=0.3,0.1