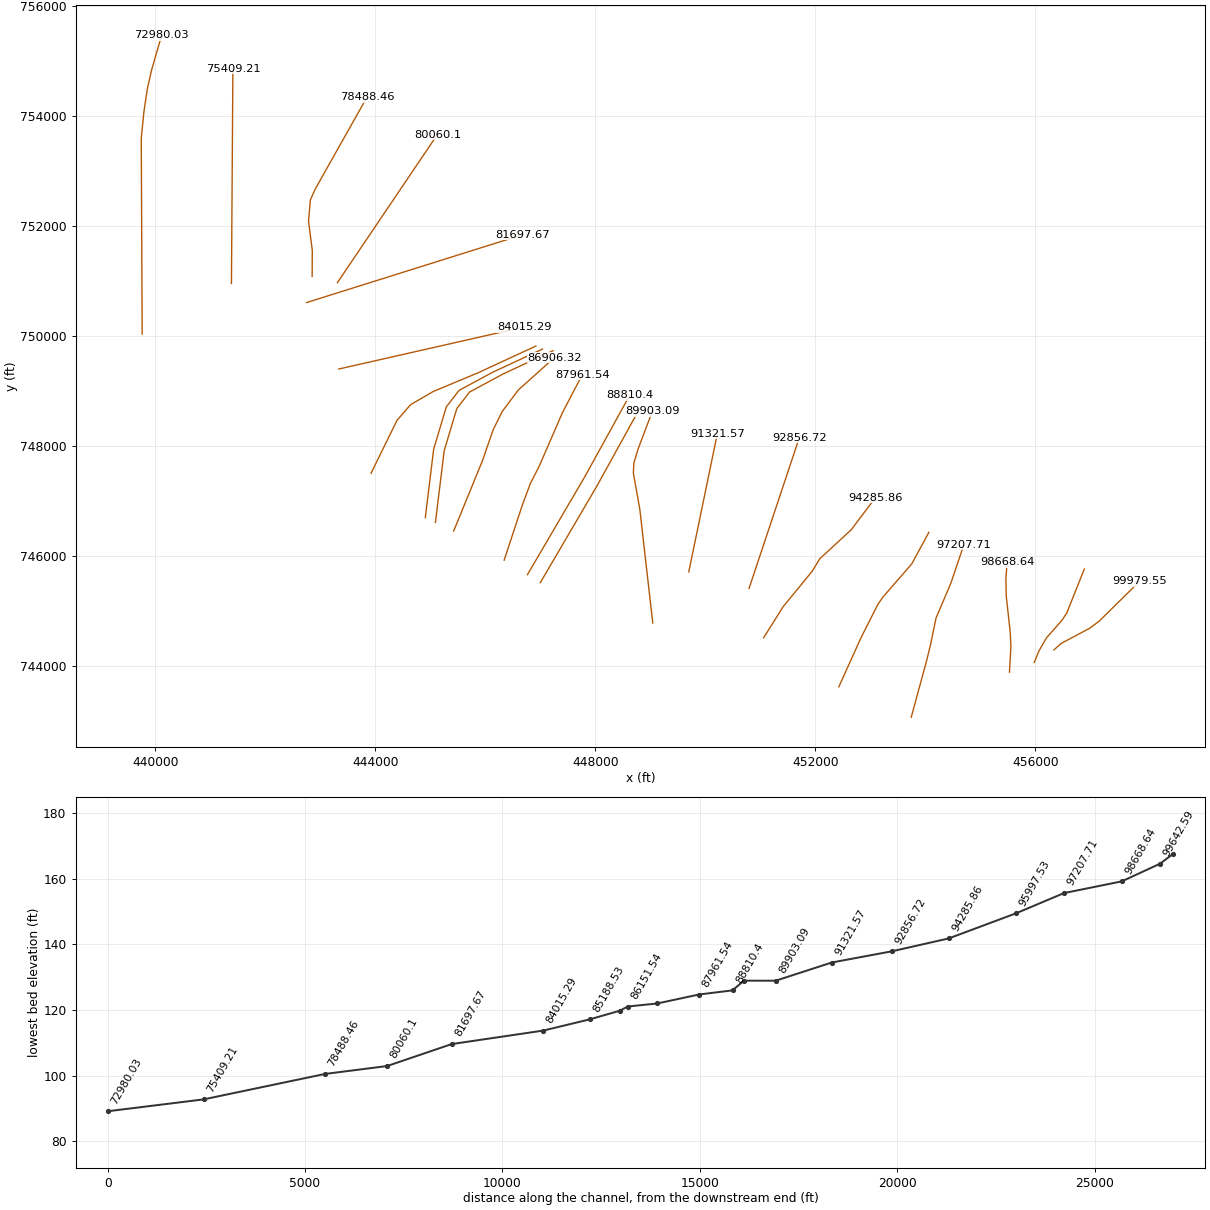
HEC-RAS study 2549_ras.prj: 2549

--- 2549_ras.g01 (geometry) --- (continued)

Type RM Length L Ch R = 3 ,100012.3,,,
BEGIN DESCRIPTION:
END DESCRIPTION:
Bridge Culvert--1,0,-1,-1, 0
Deck Dist Width WeirC Skew NumUp NumDn MinLoCord MaxHiCord MaxSubmerge Is_Ogee
38.064050,33.136400,2.6,0, 26, 28, , , 0.95, 0, 0,0,,
 9759.52 9761.32 9768.53 9776.24 9782.00 9795.48 9811.61 9829.17 9837.29 9837.29
 9841.18 9848.5410368.1310368.1310413.9510414.5710437.0610485.5310545.7810559.28
10599.7610626.7510653.7410683.9610694.2310739.36
  190.88  190.00  187.07  186.76  186.42  186.57  186.55  186.79  186.67  186.67
  186.62  186.83  186.90  186.90  186.90  187.07  186.81  186.04  184.33  184.17
  183.37  183.08  183.12  183.58  183.83  184.30
 -809.12 -810.00 -812.93 -813.24 -813.58 -813.43 -813.45 -813.21 -813.33  183.67
  183.62  183.83  183.90 -813.10 -813.10 -812.93 -813.19 -813.96 -815.67 -815.83
 -816.63 -816.92 -816.88 -816.42 -816.17 -815.70
 9759.52 9761.32 9768.53 9776.24 9782.00 9795.48 9811.61 9829.17 9841.18 9848.54
 9877.55 9877.5510408.3910408.3910413.9510414.5710419.9010482.0310493.2810505.25
10545.7810559.2810599.7610626.7510653.7410683.9610694.2310739.36
  190.88  190.00  187.07  186.76  186.42  186.57  186.55  186.79  186.62  186.83
  186.83  186.83  186.90  186.90  186.90  187.07  187.02  186.11  185.85  185.44
  184.33  184.17  183.37  183.08  183.12  183.58  183.83  184.30
 -809.12 -810.00 -812.93 -813.24 -813.58 -813.43 -813.45 -813.21 -813.38 -813.17
 -813.17  183.83  183.90 -813.10 -813.10 -812.93 -812.98 -813.89 -814.15 -814.56
 -815.67 -815.83 -816.63 -816.92 -816.88 -816.42 -816.17 -815.70
Pier Skew, UpSta & Num, DnSta & Num=  ,9876.85, 2 ,9917.11, 2 , 0 , 0 , 0 ,,
    3.00    3.00
 -813.17  186.83
    3.00    3.00
 -813.16  186.84
Pier Skew, UpSta & Num, DnSta & Num=  ,9917.92, 2 ,9958.18, 2 , 0 , 0 , 0 ,,
    3.00    3.00
 -813.16  186.84
    3.00    3.00
 -813.16  186.84
Pier Skew, UpSta & Num, DnSta & Num=  ,9958.98, 2 ,9999.24, 2 , 0 , 0 , 0 ,,
    3.00    3.00
 -813.16  186.84
    3.00    3.00
 -813.15  186.85
Pier Skew, UpSta & Num, DnSta & Num=  ,10000.05, 2 ,10040.31, 2 , 0 , 0 , 0 ,,
    3.00    3.00
 -813.15  186.85
    3.00    3.00
 -813.15  186.85
Pier Skew, UpSta & Num, DnSta & Num=  ,10041.11, 2 ,10081.37, 2 , 0 , 0 , 0 ,,
    3.00    3.00
 -813.15  186.85
    3.00    3.00
 -813.14  186.86
Pier Skew, UpSta & Num, DnSta & Num=  ,10082.18, 2 ,10122.44, 2 , 0 , 0 , 0 ,,
    3.00    3.00
 -813.14  186.86
    3.00    3.00
 -813.14  186.86
Pier Skew, UpSta & Num, DnSta & Num=  ,10123.24, 2 ,10163.50, 2 , 0 , 0 , 0 ,,
    3.00    3.00
 -813.14  186.86
    3.00    3.00
 -813.13  186.87
Pier Skew, UpSta & Num, DnSta & Num=  ,10164.30, 2 ,10204.57, 2 , 0 , 0 , 0 ,,
    3.00    3.00
 -813.13  186.87
    3.00    3.00
 -813.13  186.87
Pier Skew, UpSta & Num, DnSta & Num=  ,10205.37, 2 ,10245.63, 2 , 0 , 0 , 0 ,,
    3.00    3.00
 -813.12  186.88
    3.00    3.00
 -813.12  186.88
Pier Skew, UpSta & Num, DnSta & Num=  ,10246.43, 2 ,10286.69, 2 , 0 , 0 , 0 ,,
    3.00    3.00
 -813.12  186.88
    3.00    3.00
 -813.11  186.89
Pier Skew, UpSta & Num, DnSta & Num=  ,10287.50, 2 ,10327.76, 2 , 0 , 0 , 0 ,,
    3.00    3.00
 -813.11  186.89
    3.00    3.00
 -813.11  186.89
Pier Skew, UpSta & Num, DnSta & Num=  ,10328.56, 2 ,10368.82, 2 , 0 , 0 , 0 ,,
    3.00    3.00
 -813.11  186.89
    3.00    3.00
 -813.10  186.90
BR Coef=-1 , 0 , 0 ,, 0 ,,,0.8,0,1,0,
WSPro=,,,, 1 ,,,, 0 ,,,, 0 ,,,,-1 ,-1 ,-1 , 0 , 0 , 0 , 0 , 0
BC Design=,, 0 ,, 0 ,,,,,,

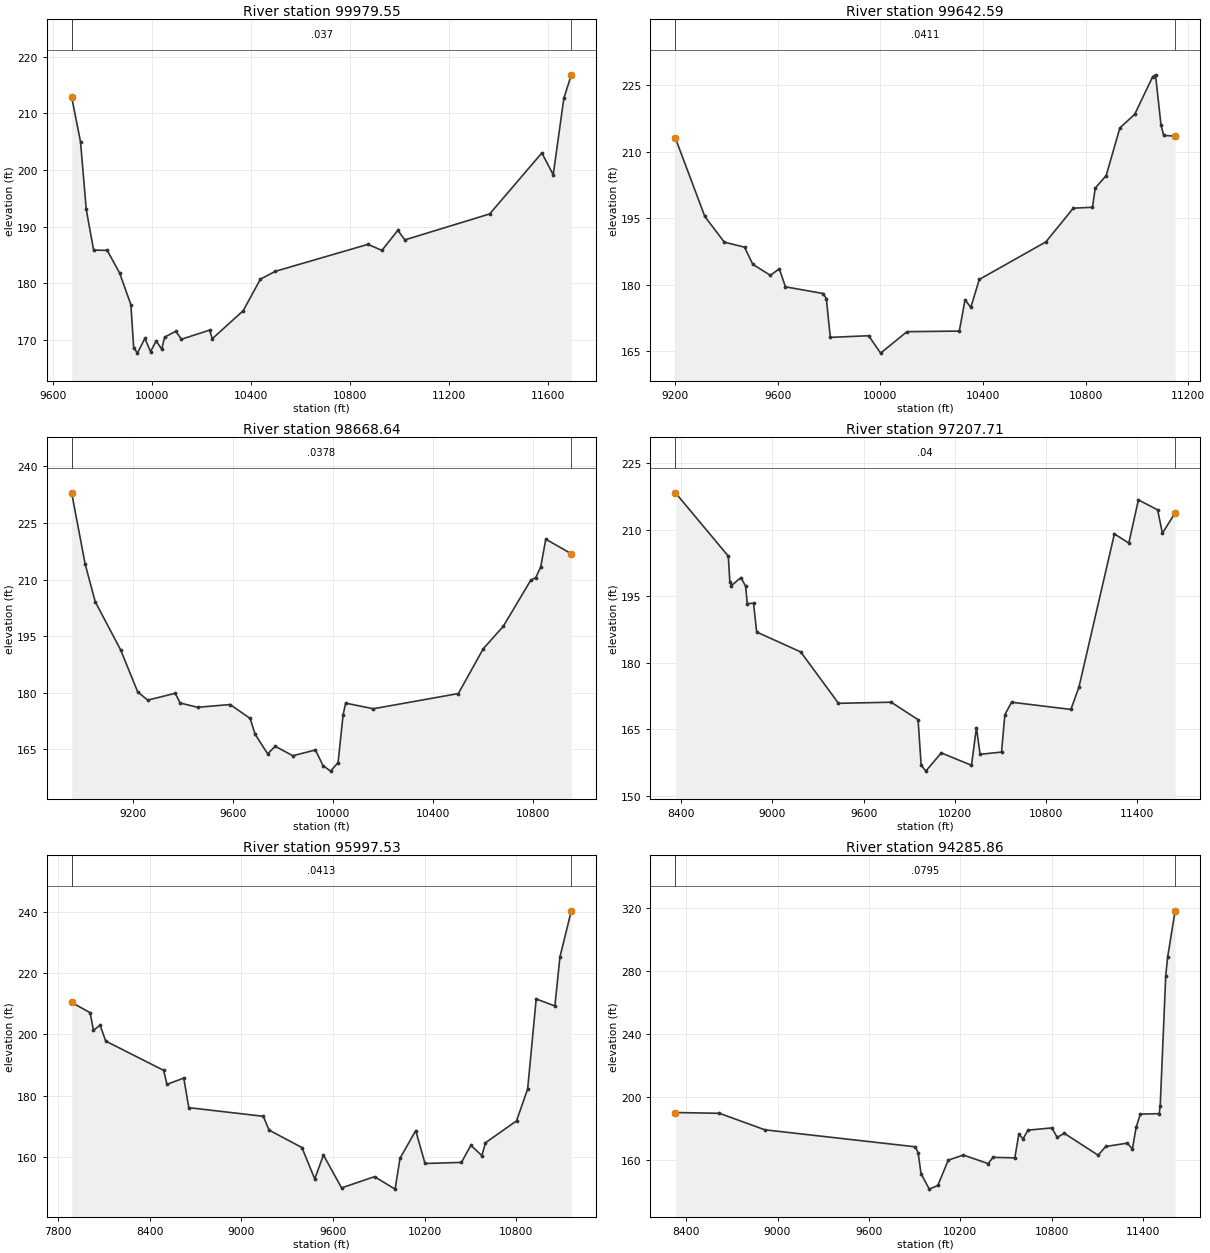
Type RM Length L Ch R = 1 ,99979.55,336.964600,336.964600,336.964600
XS GIS Cut Line= 5
456338.345808655744285.615086213456467.176544607  744401.8064325
456986.273766845744678.716154695457158.699876875744806.620613337
457899.730715632745536.185041994
#Sta/Elev= 30
9675.868212.89389711.761204.94699734.674 193.0449764.537185.84339819.492185.7903
9869.556181.78359914.892 176.1979926.225 168.6319941.127167.64159971.561170.2634
9994.229167.8947 10016.9169.794110039.56168.3363 10050.9170.462210096.23171.5026
 10118.9170.097710232.24171.703310243.57170.188510368.25175.140510437.69180.7181
10498.36182.103210871.72186.857210927.85185.787210992.16189.332411020.67187.6471
11362.88192.230911573.37203.001511619.32199.144111662.08212.643411692.28216.8022
#Mann= 3 , 0 , 0
9675.868   0.037       09675.868   0.037       011692.28   0.037       0
#XS Ineff= 2 , 0
       09888.359        10475.57       0
Bank Sta=9675.868,11692.28
Exp/Cntr=0.3,0.1

Type RM Length L Ch R = 1 ,99642.59,973.950100,973.950100,973.950100
XS GIS Cut Line= 6
455980.703677395744058.194339219456063.740147482744263.427026804
 456200.97020734744502.771481901456485.470373171744825.499656016
456572.273680729744958.900705358456890.227411087745756.584827636
#Sta/Elev= 30
9201.439213.03129315.951195.39169391.757 189.6029470.574188.47279502.865184.5978
 9571.42 182.1169606.139183.59769630.054179.52359777.004 178.0179789.518176.8769
9804.907168.12349954.427168.4929   10001164.568610103.71169.408810307.64169.5416
10330.18176.595610352.55174.884910385.56181.188310645.18189.664610751.97197.2655
10826.71197.461710837.39201.793110880.11204.6218 10933.5215.377310991.32218.4361
11061.64226.962811072.32227.341111093.68216.039811104.36213.675411148.76213.5185
#Mann= 3 , 0 , 0
9201.439  0.0411       09201.439  0.0411       011148.76  0.0411       0
#XS Ineff= 2 , 0
       09641.509         10207.4       0
Bank Sta=9201.439,11148.76
Exp/Cntr=0.3,0.1

Type RM Length L Ch R = 1 ,98668.64,1460.925200,1460.925200,1460.925200
XS GIS Cut Line= 6
455529.199984565743881.027162337455555.286105948 744342.36856971
455544.077651918744596.597637262455470.243871366745271.234815276
455464.595183318745582.187504121455486.513075425745876.816084845
#Sta/Elev= 30
8952.249 233.0039006.506 214.0649046.717204.11939148.368 191.358 9217.13180.1723
9257.176178.0101 9367.22179.81729387.221177.2398 9457.24176.09989587.338176.8418
9667.512173.14169687.598168.92859737.824163.75729767.959165.77579838.484163.2567
9929.182164.78739959.415160.65929989.648159.170110019.89161.454510040.06174.1106
10050.14177.214510160.89 175.71810501.79179.748310601.79191.656810681.82197.5791
10791.95209.814310812.04210.504710832.13213.403910852.22220.710210954.49216.8334
#Mann= 3 , 0 , 0
8952.249  0.0378       08952.249  0.0378       010954.49  0.0378       0
#XS Ineff= 2 , 0
       09516.449        10143.34       0
Bank Sta=8952.249,10954.49
Exp/Cntr=0.3,0.1

Type RM Length L Ch R = 1 ,97207.71,1210.185400,1210.185400,1210.185400
XS GIS Cut Line= 6
453742.725372945743061.030718033454017.077790245 744067.38381761
454088.784798511744356.786522208454194.931526763744867.075498221
454464.337870516745499.277501292454698.945501667746194.409686908
#Sta/Elev= 30
8363.462218.29798710.803204.03818721.169198.16518731.535197.40558793.728199.2074
8824.825197.2474 8835.19193.36358876.652193.40918897.384  186.949187.066 182.459
9435.044170.8879 9781.47171.13649958.051167.19919978.349     15710008.77155.6139
10110.39159.713710309.22156.933610341.72165.433310365.65159.405410506.61159.9039
10528.65168.340510572.72171.133410962.58169.508811015.69174.563711248.46209.0484
11343.13206.981111406.24216.712811532.46214.462911564.02209.211711647.55213.7675
#Mann= 3 , 0 , 0
8363.462    0.04       08363.462    0.04       011647.55    0.04       0
#XS Ineff= 2 , 0
       09497.179        10934.12       0
Bank Sta=8363.462,11647.55
Exp/Cntr=0.3,0.1

Type RM Length L Ch R = 1 ,95997.53,1711.664900,1711.664900,1711.664900
XS GIS Cut Line= 6
452426.344243618743613.850500197452833.014555134744513.115744713
453133.398691189745107.338541124453230.606368893 745249.39114531
453753.001372773745849.201121387454063.720264543746422.672562939
#Sta/Elev= 30
7887.379210.36328008.438 207.0528030.222201.31218073.788202.95058110.878197.7684
8490.162188.22338512.158 183.6478622.134185.71538655.235176.05299143.597173.2392
9180.906168.73839396.616163.04369480.657152.80499537.659  160.58 9656.66149.8735
 9872.47153.542310007.27149.4743 10039.5159.524610142.45168.568610203.39157.8356
10442.19158.196210503.93163.783810575.87160.402110599.79164.610710803.19171.7459
10876.15182.177310932.09 211.52411054.51209.233811087.75 225.22211162.19240.2705
#Mann= 3 , 0 , 0
7887.379  0.0413       07887.379  0.0413       011162.19  0.0413       0
#XS Ineff= 2 , 0
       09299.147        10234.83       0
Bank Sta=7887.379,11162.19
Exp/Cntr=0.3,0.1

Type RM Length L Ch R = 1 ,94285.86,1429.144400,1429.144400,1429.144400
XS GIS Cut Line= 6
451058.930329698 744505.61123768451414.646619444745071.574893621
451942.800567812745716.200341604452079.638369373745941.915952882
452652.624368466746470.677134668453093.659780288747055.974100932
#Sta/Elev= 30
8329.478190.40158618.533189.91568916.969179.4282 9904.78168.65289923.136164.9381
 9942.06151.69479996.536141.793410052.81144.127610120.85160.178610220.01163.4259
   10383158.002610414.91161.9613 10558.2 161.632 10584.7176.807210612.37173.6585
10644.01179.209210801.27 180.65310836.72174.662610883.13177.215311105.31163.3108
11155.55168.846511296.98170.981111330.43167.265911355.07181.108111382.71189.4058
11506.63189.6921   11513 194.50211549.35277.172811561.47288.842711610.92318.4055
#Mann= 3 , 0 , 0
8329.478  0.0795       08329.478  0.0795       011610.92  0.0795       0
#XS Ineff= 2 , 0
       09840.294        10607.68       0
Bank Sta=8329.478,11610.92
Exp/Cntr=0.3,0.1

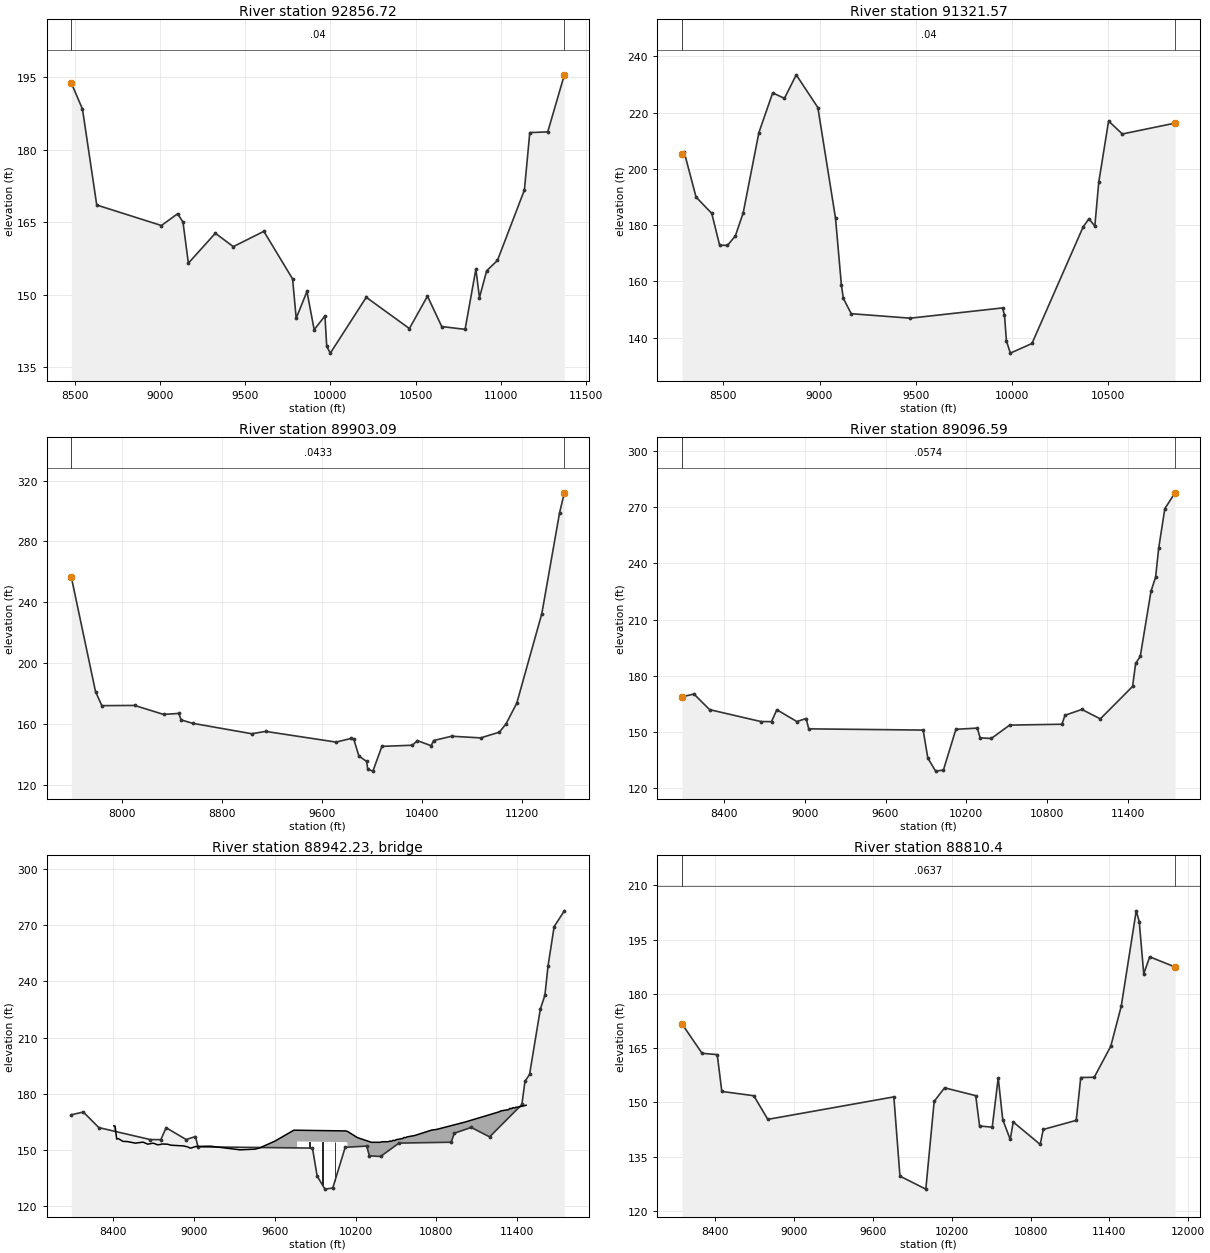
Type RM Length L Ch R = 1 ,92856.72,1535.142700,1535.142700,1535.142700
XS GIS Cut Line= 2
 450794.30306977745403.510322134451708.932104468748147.397426218
#Sta/Elev= 30
8480.844193.80718546.293188.40588629.987168.5531 9009.46164.31129104.328166.7478
9135.951165.01889167.574156.52069325.688 162.7119431.097 159.9469610.293163.1065
9778.948153.25769800.029145.12289863.275150.67359905.439142.74879968.684145.6051
9979.225139.291510000.31 137.90610211.13149.463410464.11142.992310570.15149.7007
10653.84 143.40310790.88142.827710854.12 155.286 10875.2149.388510917.37154.9514
10980.61157.086211138.73171.651711170.35 183.53711275.76183.685911373.15195.4922
#Mann= 3 , 0 , 0
8480.844    0.04       08480.844    0.04       011373.15    0.04       0
#XS Ineff= 2 , 0
       09556.788        10701.95       0
Bank Sta=8480.844,11373.15
Exp/Cntr=0.3,0.1

Type RM Length L Ch R = 1 ,91321.57,1418.488300,1418.488300,1418.488300
XS GIS Cut Line= 2
449698.228447355745703.503260286450216.813370557748213.275966288
#Sta/Elev= 30
8285.072205.29418296.811205.89768358.079189.97598439.769184.16988480.614172.8471
8521.459172.79358562.304176.15058603.148 184.3618684.838212.92988756.317227.0311
8817.585 225.1068878.852233.46418991.176221.83159083.077182.44799113.711  158.56
9123.922153.89239164.767148.48299471.104146.88899951.032150.53829961.244148.0991
9971.455138.79999991.877 134.457 10104.2137.887210369.69179.291810400.33182.2629
10430.96179.659510451.38195.252310502.44 217.02810573.92 212.41810847.86 216.287
#Mann= 3 , 0 , 0
8285.072    0.04       08285.072    0.04       010847.86    0.04       0
#XS Ineff= 2 , 0
       0 9326.28                       0
Bank Sta=8285.072,10847.86
Exp/Cntr=0.3,0.1

Type RM Length L Ch R = 1 ,89903.09,806.495000,806.495000,806.495000
XS GIS Cut Line= 6
449044.078292182 744772.96073052448808.159022897 746843.00243929
448690.854110271747500.803306803448699.534665942 747683.09497346
448778.636622816747943.907645375449038.825761817748630.523615022
#Sta/Elev= 30
7598.595256.58997792.079  181.277842.455172.00188104.411172.13798336.141166.2345
8457.043166.88888477.194162.59688567.871160.39649041.369153.52379152.099155.0654
9714.932148.0283 9836.56150.44429856.886149.91779897.553138.92039958.784135.3103
9968.989 130.08610009.82128.923410081.39145.208410324.91145.963610365.19148.9772
10475.32145.643810495.34149.0631 10640.1151.890910871.37150.786711021.08154.5808
11074.55160.0541 11160.1173.699811360.18232.552511502.31298.9898 11540.3312.0161
#Mann= 3 , 0 , 0
7598.595  0.0433       07598.595  0.0433       0 11540.3  0.0433       0
#XS Ineff= 2 , 0
       09548.657        10307.69       0
Bank Sta=7598.595,11540.3
Exp/Cntr=0.3,0.1

Type RM Length L Ch R = 1 ,89096.59,286.188600,286.188600,286.188600
XS GIS Cut Line= 4
446998.758637995745508.189578876448036.037140101747279.152875185
448713.120473444748507.451486304448814.259760171748691.561325505
#Sta/Elev= 30
8087.282 168.6868176.298170.15658292.188161.81848674.627155.42498752.575155.3937
8792.148161.75318941.175 155.4439009.796157.06079029.582151.53869879.888150.8822
9914.656135.89389972.601128.929210030.55129.520710123.26151.287910282.51151.9468
10303.23146.726110386.13146.381810523.15153.539810911.39154.004210934.23158.7872
11059.83161.920911196.86156.867611436.65174.208511459.48 186.53811493.74190.2907
11573.65225.134611607.88232.668311630.69248.081711676.33269.297711752.28277.7467
#Mann= 3 , 0 , 0
8087.282  0.0574       08087.282  0.0574       011752.28  0.0574       0
#XS Ineff= 2 , 0
       09731.885        10149.12       0
Bank Sta=8087.282,11752.28
Exp/Cntr=0.3,0.1

Type RM Length L Ch R = 3 ,88942.23,,,
BEGIN DESCRIPTION:
END DESCRIPTION:
Bridge Culvert--1,0,-1,-1, 0
Deck Dist Width WeirC Skew NumUp NumDn MinLoCord MaxHiCord MaxSubmerge Is_Ogee
122.899300,40.390000,2.6,0, 60, 60, , , 0.95, 0, 0,0,,
 8403.35 8412.93 8424.48 8436.02 8470.66 8505.30 8563.03 8620.75 8655.39 8690.03
 8701.57 8724.67 8747.76 8759.30 8801.39 8828.58 8921.43 8955.58 8967.13 8978.67
 9013.31 9121.50 9341.58 9452.05 9486.68 9601.66 9741.60 9765.92 9765.9210126.06
10139.5910139.5910214.0610317.9710381.9310398.7910444.9810456.5210468.0710479.61
10491.1610502.7110548.8910560.4310571.9810583.5310641.2510766.9610801.1511015.97
11268.5511279.9511336.9511348.3511359.7511371.1511382.5511393.9511405.3511468.32
  162.75  162.62  155.69  155.97  154.47  154.35  153.52  154.05  152.97  153.44
  153.40  152.71  152.73  153.07  152.96  152.41  152.04  151.44  150.92  150.92
  151.75  151.90  149.94  150.29  150.93  154.64  160.45  160.42  160.42  160.06
  159.83  159.83  156.47  153.97  153.96  154.27  154.29  154.65  154.50  155.04
  154.90  155.38  155.99  156.54  156.45  156.86  157.62  160.53  160.83  164.83
  170.29  170.75  171.44  172.12  171.95  172.51  172.30  172.79  172.70  173.78
 -837.25 -837.38 -844.31 -844.03 -845.53 -845.65 -846.48 -845.95 -847.03 -846.56
 -846.60 -847.29 -847.27 -846.93 -847.04 -847.59 -847.96 -848.56 -849.08 -849.08
 -848.25 -848.10 -850.06 -849.71 -849.07 -845.36 -839.55 -839.58  154.42  154.06
  153.83 -840.17 -843.53 -846.03 -846.04 -845.73 -845.71 -845.35 -845.50 -844.96
 -845.10 -844.62 -844.01 -843.46 -843.55 -843.14 -842.38 -839.47 -839.17 -835.17
 -829.71 -829.25 -828.56 -827.88 -828.05 -827.49 -827.70 -827.21 -827.30 -826.22
 8403.35 8412.93 8424.48 8436.02 8470.66 8505.30 8563.03 8620.75 8655.39 8690.03
 8724.67 8747.76 8759.30 8801.39 8828.58 8921.43 8955.58 8967.13 8978.67 9013.31
 9121.50 9341.58 9452.05 9486.68 9601.66 9734.26 9734.26 9741.6010107.9310107.93
10141.8510156.3310214.0610317.9710381.9310398.7910444.9810456.5210468.0710479.61
10491.1610502.7110548.8910560.4310571.9810583.5310641.2510766.9610801.1511015.97
11268.5511279.9511336.9511348.3511359.7511371.1511382.5511393.9511405.3511468.32
  162.75  162.62  155.69  155.97  154.47  154.35  153.52  154.05  152.97  153.44
  152.71  152.73  153.07  152.96  152.41  152.04  151.44  150.92  150.92  151.75
  151.90  149.94  150.29  150.93  154.64  160.14  160.14  160.45  160.07  160.07
  159.80  158.88  156.47  153.97  153.96  154.27  154.29  154.65  154.50  155.04
  154.90  155.38  155.99  156.54  156.45  156.86  157.62  160.53  160.83  164.83
  170.29  170.75  171.44  172.12  171.95  172.51  172.30  172.79  172.70  173.78
 -837.25 -837.38 -844.31 -844.03 -845.53 -845.65 -846.48 -845.95 -847.03 -846.56
 -847.29 -847.27 -846.93 -847.04 -847.59 -847.96 -848.56 -849.08 -849.08 -848.25
 -848.10 -850.06 -849.71 -849.07 -845.36 -839.86  154.14  154.45  154.07 -839.93
 -840.20 -841.12 -843.53 -846.03 -846.04 -845.73 -845.71 -845.35 -845.50 -844.96
 -845.10 -844.62 -844.01 -843.46 -843.55 -843.14 -842.38 -839.47 -839.17 -835.17
 -829.71 -829.25 -828.56 -827.88 -828.05 -827.49 -827.70 -827.21 -827.30 -826.22
Pier Skew, UpSta & Num, DnSta & Num=  ,9858.34, 2 ,9826.68, 2 , 0 , 0 , 0 ,,
    4.00    4.00
 -839.67  160.33
    4.00    4.00
 -839.64  160.36
Pier Skew, UpSta & Num, DnSta & Num=  ,9952.76, 2 ,9921.09, 2 , 0 , 0 , 0 ,,
    4.00    4.00
 -839.77  160.23
    4.00    4.00
 -839.74  160.26
Pier Skew, UpSta & Num, DnSta & Num=  ,10047.17, 2 ,10015.51, 2 , 0 , 0 , 0 ,,
    4.00    4.00
 -839.86  160.14
    4.00    4.00
 -839.83  160.17
BR Coef=-1 , 0 , 0 ,, 0 ,,,0.8,0,1,0,
WSPro=,,,, 1 ,,,, 0 ,,,, 0 ,,,,-1 ,-1 ,-1 , 0 , 0 , 0 , 0 , 0
BC Design=,, 0 ,, 0 ,,,,,,

Type RM Length L Ch R = 1 , 88810.4,848.866800,848.866800,848.866800
XS GIS Cut Line= 4
446764.869569063745653.518709108447806.002417892747431.062597394
448483.085751235748659.361208513448622.892001182748913.858813241
#Sta/Elev= 30
8146.434171.70098298.809163.56028414.699163.19028449.466153.00678692.836151.8175
8799.636145.27749759.029151.49969805.385129.5729 10002.4125.977810065.95150.2598
 10145.1154.010710382.22151.839910411.51143.447110507.82143.1181 10553.5156.7819
10587.75145.226710644.84139.727110667.68144.550510873.22138.335410896.06142.4873
11147.27145.003511181.52156.852111284.29 156.928 11409.9165.483511489.83176.5841
11604.01202.975711626.84200.012711661.07185.5591 11706.7190.252411899.36187.4417
#Mann= 3 , 0 , 0
8146.434  0.0637       08146.434  0.0637       011899.36  0.0637       0
#XS Ineff= 2 , 0
       09776.317         10134.9       0
Bank Sta=8146.434,11899.36
Exp/Cntr=0.3,0.1

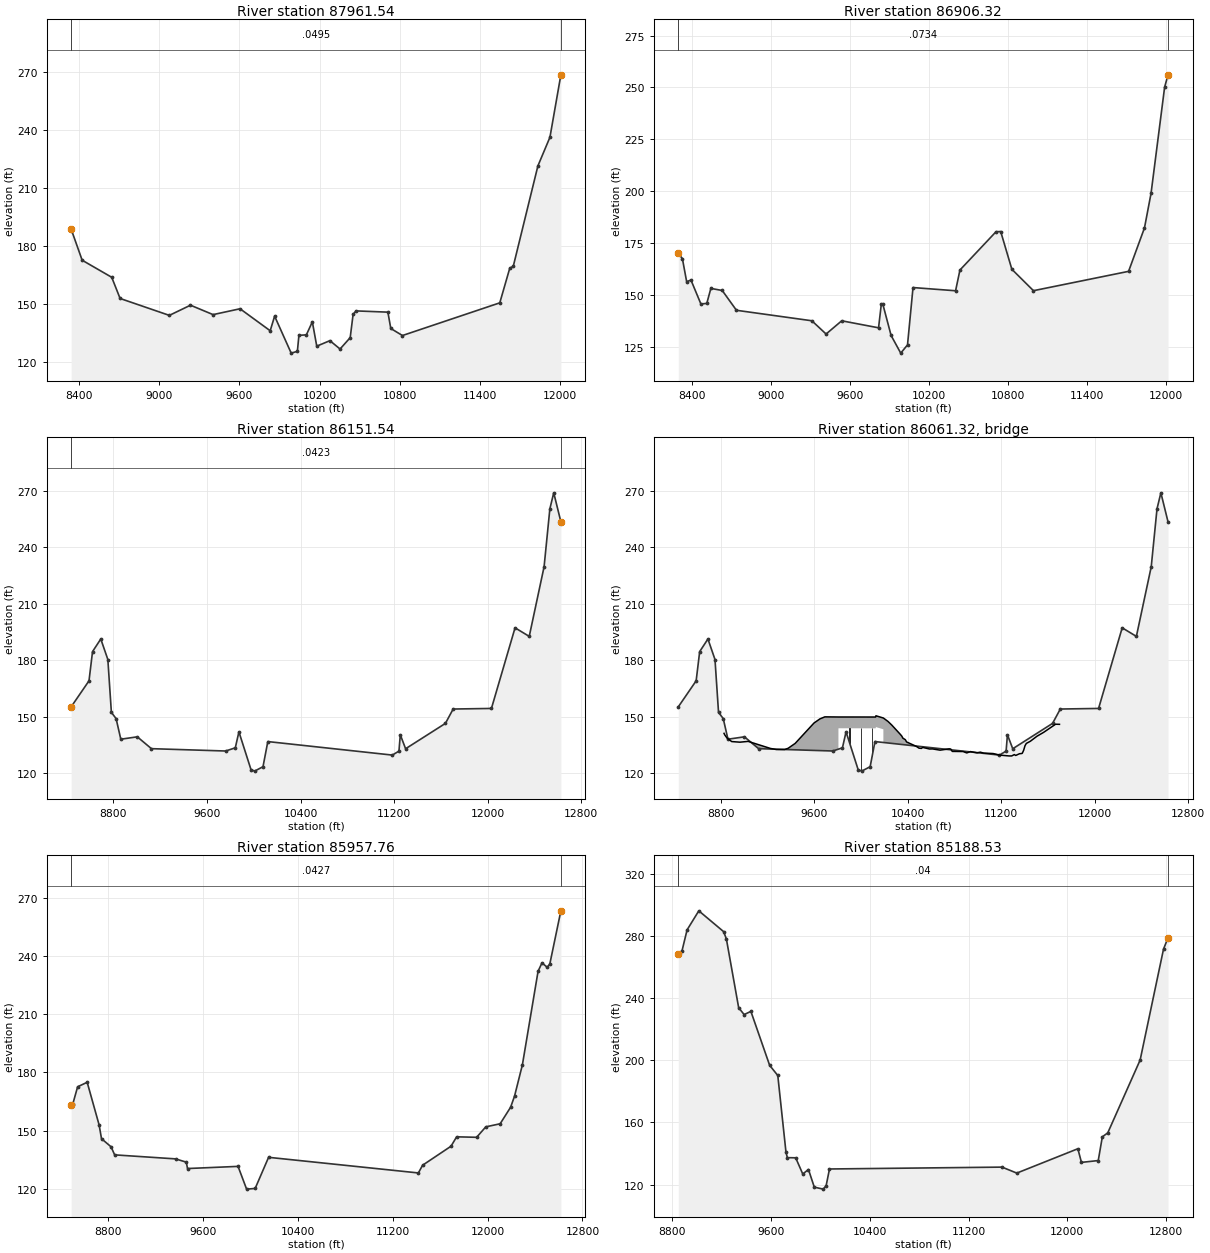
Type RM Length L Ch R = 1 ,87961.54,1055.219100,1055.219100,1055.219100
XS GIS Cut Line= 6
446341.332668573 745916.68726863446673.118593991746921.386953071
446819.157925367747313.513413474446973.899493873 747614.96081017
447405.632950991748608.621028095447760.351509809749285.917393118
#Sta/Elev= 30
8340.867188.78158423.198172.71138644.389163.90098707.052 152.9529075.475144.2207
9233.704 149.4769402.784144.61489604.549147.63279830.104136.27579863.157 143.827
 9987.18124.720710033.43125.653410044.99133.890710100.81134.179510145.43140.8854
10178.43128.312710276.77131.163110352.74126.843510428.63 132.71710450.32144.6907
   10472146.536510710.59145.887610732.38137.448510819.55133.814811547.76150.6947
11622.09168.503111648.99169.648511832.97221.435911923.14236.255712004.84268.4751
#Mann= 3 , 0 , 0
8340.867  0.0495       08340.867  0.0495       012004.84  0.0495       0
#XS Ineff= 2 , 0
       09479.351        10277.75       0
Bank Sta=8340.867,12004.84
Exp/Cntr=0.3,0.1

Type RM Length L Ch R = 1 ,86906.32,754.780900,754.780900,754.780900
XS GIS Cut Line= 6
445422.924973428746446.148869023   445945.083058 747720.63335368
446141.499175638748287.229473367 446304.91391632748618.483688071
446601.477680147 749013.92782931447255.090221435749598.893584564
#Sta/Elev= 30
8295.661 170.0798326.846167.50738359.266156.39038391.686157.22388467.333145.6844
8512.121145.9431 8542.98153.17488629.433152.1678  8737.5 142.6319310.255137.5807
9418.321131.19349537.195137.57049816.909134.1934 9838.18145.73329848.815145.7198
  9912.3130.48839985.415121.991610036.88125.956810078.73153.582910402.06152.0387
10435.27162.038610709.06180.473510744.85180.570110829.54162.397410993.53152.0735
11716.26161.392511837.03182.327111886.88198.946511989.96250.091112015.85256.0766
#Mann= 3 , 0 , 0
8295.661  0.0734       08295.661  0.0734       012015.85  0.0734       0
#XS Ineff= 2 , 0
       09050.279        10222.44       0
Bank Sta=8295.661,12015.85
Exp/Cntr=0.3,0.1

Type RM Length L Ch R = 1 ,86151.54,193.772000,193.772000,193.772000
XS GIS Cut Line= 6
445091.573912978746603.456948221445251.184709549747906.945120543
445481.219431758748675.174287245445713.424292892748974.653453901
446325.403459609749304.514564991447230.351376235749725.521509424
#Sta/Elev= 30
8438.144155.23098590.819169.07268621.043184.60858691.566191.31458752.014180.4061
8782.238152.29168822.537148.98678862.836138.02589003.882139.29229124.778132.9991
9759.666131.75289842.078133.45199872.983141.94259975.998121.9104 10006.9121.0556
10079.01123.405210120.22136.772311185.07129.588511241.87 131.69711253.23140.3866
11298.67132.956611639.16146.439111705.33154.073712032.75154.382312234.74197.2586
12356.06 192.69312483.18229.750312532.53260.542712565.61  269.0312626.66253.6333
#Mann= 3 , 0 , 0
8438.144  0.0423       08438.144  0.0423       012626.66  0.0423       0
#XS Ineff= 2 , 0
       09153.558        10774.48       0
Bank Sta=8438.144,12626.66
Exp/Cntr=0.3,0.1

Type RM Length L Ch R = 3 ,86061.32,,,
BEGIN DESCRIPTION:
END DESCRIPTION:
Bridge Culvert--1,0,-1,-1, 0
Deck Dist Width WeirC Skew NumUp NumDn MinLoCord MaxHiCord MaxSubmerge Is_Ogee
81.302050,31.167900,2.6,0, 60, 60, , , 0.95, 0, 0,0,,
 8829.32 8834.77 8854.87 8895.08 8965.43 9035.78 9226.73 9276.98 9347.33 9377.48
 9437.78 9598.58 9650.05 9691.65 9807.91 9807.9110125.9310128.4010192.0910192.09
10232.3910263.6610337.7310349.4810358.8910380.0510390.6310475.2710496.4410517.60
10528.1810586.6010612.5710677.5010755.4110768.4010781.3810873.8610905.2110936.56
10993.7911020.7011050.6811130.3311187.2211266.8711289.6311312.3911323.7611356.06
11377.0211380.6611392.0311403.4111414.7911448.9311505.8211562.7111665.1211698.33
  141.14  140.40  138.64  136.77  136.45  136.87  133.11  132.56  132.55  133.20
  135.80  146.63  148.86  149.91  149.84  149.84  149.82  150.49  149.30  149.30
  147.44  145.57  140.56  139.70  138.60  137.77  136.58  134.17  133.28  133.13
  133.67  132.82  132.86  132.20  132.92  132.79  131.54  131.48  130.73  131.45
  130.78  131.15  130.64  130.41  129.58  129.13  129.13  129.86  129.38  130.30
  130.44  130.61  132.17  134.56  135.78  136.93  139.61  141.67  146.00  145.94
 -858.86 -859.60 -861.36 -863.23 -863.55 -863.13 -866.89 -867.44 -867.45 -866.80
 -864.20 -853.37 -851.14 -850.09 -850.16  143.84  143.82  144.49  143.30 -850.70
 -852.56 -854.43 -859.44 -860.30 -861.40 -862.23 -863.42 -865.83 -866.72 -866.87
 -866.33 -867.18 -867.14 -867.80 -867.08 -867.21 -868.46 -868.52 -869.27 -868.55
 -869.22 -868.85 -869.36 -869.59 -870.42 -870.87 -870.87 -870.14 -870.62 -869.70
 -869.56 -869.39 -867.83 -865.44 -864.22 -863.07 -860.39 -858.33 -854.00 -854.06
 8829.32 8834.77 8854.87 8895.08 8965.43 9035.78 9226.73 9276.98 9347.33 9377.48
 9437.78 9598.58 9650.05 9691.65 9807.91 9807.9110125.9310128.4010192.0910192.09
10232.3910263.6610337.7310349.4810358.8910380.0510390.6310475.2710496.4410517.60
10528.1810586.6010612.5710677.5010755.4110768.4010781.3810873.8610905.2110936.56
10993.7911020.7011050.6811130.3311187.2211266.8711289.6311312.3911323.7611356.06
11377.0211380.6611392.0311403.4111414.7911448.9311505.8211562.7111665.1211698.33
  141.14  140.40  138.64  136.77  136.45  136.87  133.11  132.56  132.55  133.20
  135.80  146.63  148.86  149.91  149.84  149.84  149.82  150.49  149.30  149.30
  147.44  145.57  140.56  139.70  138.60  137.77  136.58  134.17  133.28  133.13
  133.67  132.82  132.86  132.20  132.92  132.79  131.54  131.48  130.73  131.45
  130.78  131.15  130.64  130.41  129.58  129.13  129.13  129.86  129.38  130.30
  130.44  130.61  132.17  134.56  135.78  136.93  139.61  141.67  146.00  145.94
 -858.86 -859.60 -861.36 -863.23 -863.55 -863.13 -866.89 -867.44 -867.45 -866.80
 -864.20 -853.37 -851.14 -850.09 -850.16  143.84  143.82  144.49  143.30 -850.70
 -852.56 -854.43 -859.44 -860.30 -861.40 -862.23 -863.42 -865.83 -866.72 -866.87
 -866.33 -867.18 -867.14 -867.80 -867.08 -867.21 -868.46 -868.52 -869.27 -868.55
 -869.22 -868.85 -869.36 -869.59 -870.42 -870.87 -870.87 -870.14 -870.62 -869.70
 -869.56 -869.39 -867.83 -865.44 -864.22 -863.07 -860.39 -858.33 -854.00 -854.06
Pier Skew, UpSta & Num, DnSta & Num=  ,9902.95, 2 ,9902.95, 2 , 0 , 0 , 0 ,,
    4.00    4.00
 -850.17  149.83
    4.00    4.00
 -850.17  149.83
Pier Skew, UpSta & Num, DnSta & Num=  ,10000.00, 2 ,10000.00, 2 , 0 , 0 , 0 ,,
    4.00    4.00
 -850.17  149.83
    4.00    4.00
 -850.17  149.83
Pier Skew, UpSta & Num, DnSta & Num=  ,10097.05, 2 ,10097.05, 2 , 0 , 0 , 0 ,,
    4.00    4.00
 -850.18  149.82
    4.00    4.00
 -850.18  149.82
BR Coef=-1 , 0 , 0 ,, 0 ,,,0.8,0,1,0,
WSPro=,,,, 1 ,,,, 0 ,,,, 0 ,,,,-1 ,-1 ,-1 , 0 , 0 , 0 , 0 , 0
BC Design=,, 0 ,, 0 ,,,,,,

Type RM Length L Ch R = 1 ,85957.76,769.237200,769.237200,769.237200
XS GIS Cut Line= 6
444907.577590138746690.808737829 445060.21248734747937.327064991
445290.247209549748705.556231678445522.452070683749005.035398334
  446134.4312374749334.896509439447039.379153997749755.903453887
#Sta/Elev= 30
 8486.46163.18958500.757163.78018541.056172.58158621.653174.8993  8722.4152.8936
8742.549145.80958823.147141.61448853.371 137.465 9367.18135.39219457.852133.7017
9467.927 130.4139894.414131.52359966.525119.791810038.64120.138410151.95136.1951
11415.66128.1371 11451.1132.115111690.86 141.91911738.28146.773211906.88146.5206
11984.09  151.9112105.41153.503312193.64162.035512226.73167.7508 12292.9183.8763
12425.25 232.15612458.34236.513712502.46234.180412524.52235.979712617.58263.3319
#Mann= 3 , 0 , 0
 8486.46  0.0427       0 8486.46  0.0427       012617.58  0.0427       0
#XS Ineff= 2 , 0
       09174.057        11037.87       0
Bank Sta=8486.46,12617.58
Exp/Cntr=0.3,0.1

Type RM Length L Ch R = 1 ,85188.53,1173.238400,1173.238400,1173.238400
XS GIS Cut Line= 6
 443921.47134009 747498.08179602444393.380019605748459.638937116
444640.411642671748744.332243919  445049.6020917 748982.72001873
445868.846909314749324.746465549 446918.05318436749810.004695669
#Sta/Elev= 30
8847.427268.28088877.931270.44388918.707283.77739013.748296.01539215.027282.6236
9237.299277.88039336.797233.71999380.965229.3296 9435.82231.38129587.834196.7087
9653.778190.17589720.429140.71179731.537137.3733 9798.95137.26299856.155126.8641
 9902.45129.74929949.652118.408210022.35117.133510045.49119.286810072.92130.0811
 11471.3131.283411591.04127.438612085.85143.085412114.99134.322412251.17135.4983
12284.23150.734912328.32153.309912590.67200.1109 12780.2271.415312816.63278.6812
#Mann= 3 , 0 , 0
8847.427    0.04       08847.427    0.04       012816.63    0.04       0
#XS Ineff= 2 , 0
       09657.846        11415.88       0
Bank Sta=8847.427,12816.63
Exp/Cntr=0.3,0.1

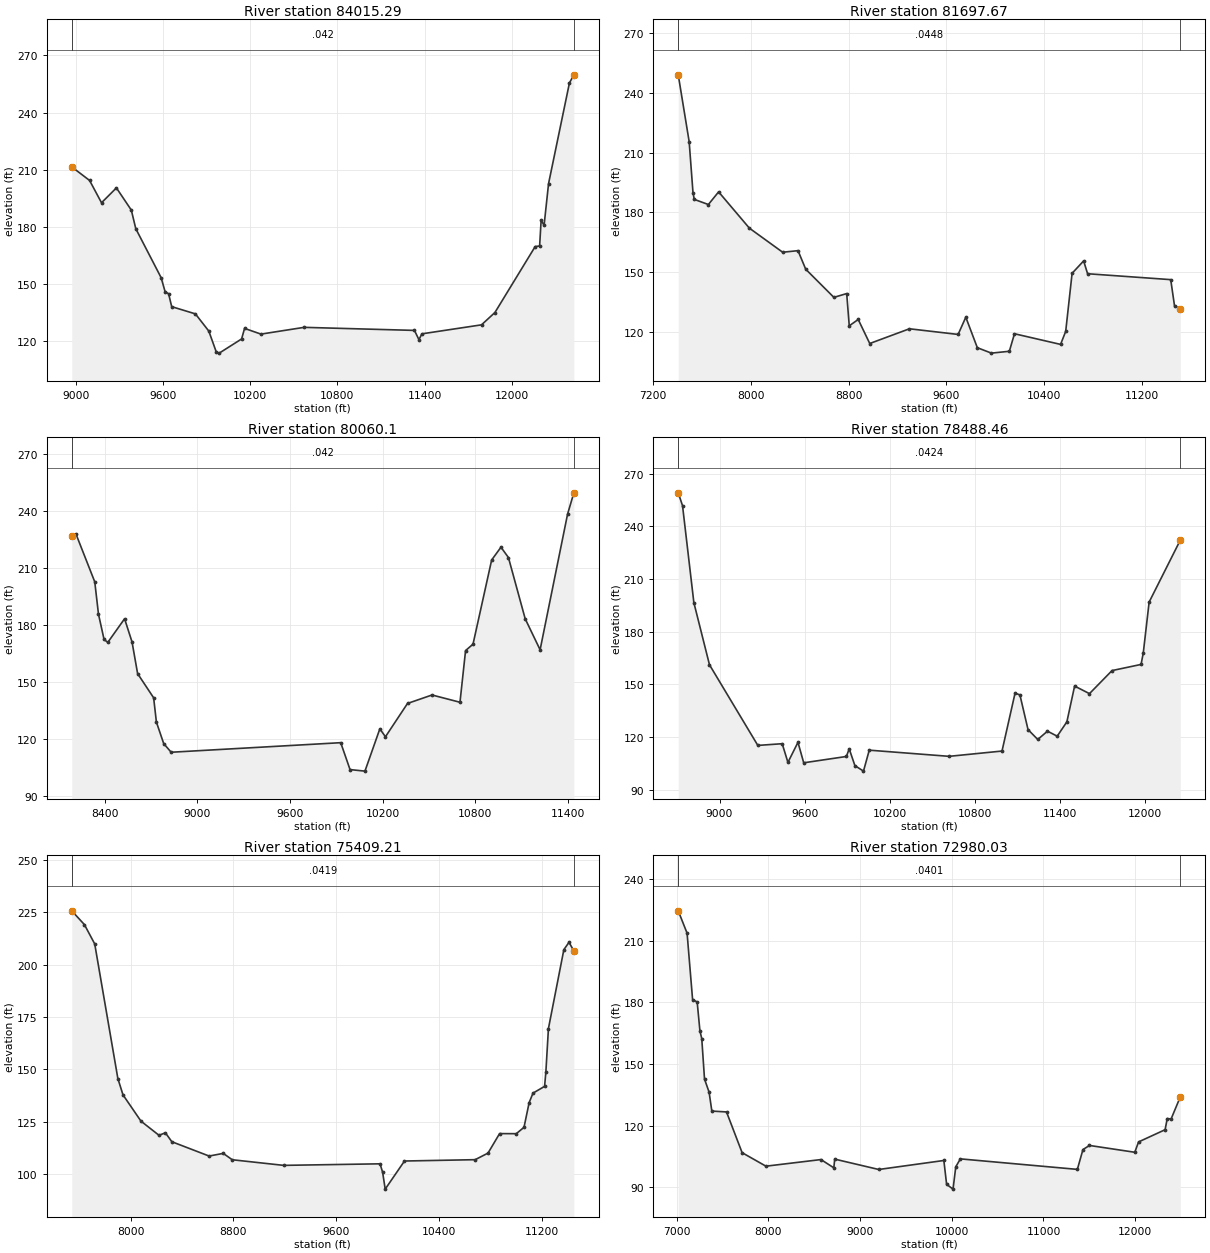
Type RM Length L Ch R = 1 ,84015.29,2317.615300,2317.615300,2317.615300
XS GIS Cut Line= 2
 443335.40074724749392.928161412446704.591826707750156.946037352
#Sta/Elev= 30
8972.269211.49549094.905204.35979176.936192.66319279.475200.46389382.014188.8085
9412.776179.04119587.092153.34729614.689145.91569638.361144.92949659.907138.1207
9822.931134.33499915.216125.29949966.486114.34629986.994113.7305 10140.8121.1665
10161.31126.7101 10274.1123.714310571.47127.262711330.25125.656111361.02120.7944
11381.52123.860211791.68128.579611883.96135.050712160.82169.651312191.58169.9823
12201.83 183.40312222.34 180.865 12253.1202.748412396.66 255.532   12427259.8087
#Mann= 3 , 0 , 0
8972.269   0.042       08972.269   0.042       0   12427   0.042       0
#XS Ineff= 2 , 0
       09814.293        11387.03       0
Bank Sta=8972.269,12427
Exp/Cntr=0.3,0.1

Type RM Length L Ch R = 1 ,81697.67,1637.567700,1637.567700,1637.567700
XS GIS Cut Line= 2
442749.730715603750601.390481785446669.869604468751832.293259576
#Sta/Elev= 30
 7404.97248.89077494.344215.46737525.788189.88027536.269186.55557651.564183.9908
7735.415190.32197986.969172.17758259.484160.11878385.261160.89888448.149151.6274
8678.739137.52978783.553139.42828804.516123.29388877.886 126.4648972.218114.4408
9297.141121.80799695.433 118.9799758.321127.60839852.654112.34189967.949109.6265
10114.69110.553810156.61 119.32410533.94113.994910575.87120.506710628.28149.5742
10722.61155.772910755.09149.355311435.34146.400111466.79133.133111513.82131.9239
#Mann= 3 , 0 , 0
 7404.97  0.0448       0 7404.97  0.0448       011513.82  0.0448       0
#XS Ineff= 2 , 0
       08905.831        10427.77       0
Bank Sta=7404.97,11513.82
Exp/Cntr=0.3,0.1

Type RM Length L Ch R = 1 , 80060.1,1571.644200,1571.644200,1571.644200
XS GIS Cut Line= 2
443308.324465573750961.633537352445127.768910021  753656.0779818
#Sta/Elev= 30
8186.971226.82888215.166227.8262 8335.83202.79568359.962185.72918396.162172.3832
8420.294170.86358528.892183.31918577.157171.11538613.356154.37648717.109141.6137
8734.978128.83118782.285117.46778830.551112.89639928.591117.93899988.922103.7417
10085.45102.931710181.98125.247210218.18121.057610361.08138.637910519.84143.1032
10700.84139.267710737.04166.5312 10785.3169.921310905.97214.3296 10966.3221.0789
11014.56215.628311123.16183.296211219.69166.9511 11397.5238.501611438.19249.7656
#Mann= 3 , 0 , 0
8186.971   0.042       08186.971   0.042       011438.19   0.042       0
#XS Ineff= 2 , 0
       08746.007                       0
Bank Sta=8186.971,11438.19
Exp/Cntr=0.3,0.1

Type RM Length L Ch R = 1 ,78488.46,3079.252100,3079.252100,3079.252100
XS GIS Cut Line= 6
442850.236286342751074.769033358442852.800007522751551.114638671
442784.416448444752081.323125526442818.037134111752468.200786188
 442908.14054513752668.728069976443849.015356869 754338.26583083
#Sta/Elev= 30
8708.976259.08218739.207251.76938819.208196.4764 8929.21161.1043 9269.84115.1772
9441.554116.1494 9481.99105.50949552.754116.9526 9593.19105.27049893.787108.8736
9913.828113.2171 9953.91103.667210014.46100.528210055.12112.470810617.96 108.956
10990.62111.966611082.49144.939811116.79143.971911173.94124.196811242.53118.5708
11311.12123.289911379.61120.4359 11447.8128.619711502.24148.994611606.92144.6736
11766.04157.819311970.62161.312111986.18167.897512027.45196.848412247.11  232.14
#Mann= 3 , 0 , 0
8708.976  0.0424       08708.976  0.0424       012247.11  0.0424       0
#XS Ineff= 2 , 0
       0                               0
Bank Sta=8708.976,12247.11
Exp/Cntr=0.3,0.1

Type RM Length L Ch R = 1 ,75409.21,2429.179800,2429.179800,2429.179800
XS GIS Cut Line= 2
441382.977243364750946.442565128 441409.01891005754852.692565113
#Sta/Elev= 30
7542.669225.79617641.228219.1916 7721.23209.97847901.234 145.6467941.235137.8232
8081.238 125.2578221.241118.50888271.242119.69558321.243115.4247 8611.25108.5849
8721.252109.85728791.254106.81449191.263104.12689941.279104.8683 9961.28100.8124
 9981.2892.7710810131.28106.2075 10681.3106.8481 10781.3109.9988 10871.3 119.312
 11001.3  119.27 11061.3122.322711101.31134.139311131.31 138.66611221.31141.8796
11231.31148.705811251.31169.535511371.31207.234211411.31210.757111449.01206.6458
#Mann= 3 , 0 , 0
7542.669  0.0419       07542.669  0.0419       011449.01  0.0419       0
#XS Ineff= 2 , 0
       08561.524                       0
Bank Sta=7542.669,11449.01
Exp/Cntr=0.3,0.1

Type RM Length L Ch R = 1 ,72980.03,2805.675500,2805.675500,2805.675500
XS GIS Cut Line= 6
439759.713354468750028.473815113439742.896874994753587.561455175
439792.037813306754074.617999658439852.210193455 754479.49511303
439933.675736964754840.587693825440114.286379367755461.110884964
#Sta/Elev= 30
7017.284224.46757113.811213.59367173.811 181.3267223.811180.12727253.811166.1049
7273.811162.33437303.811142.67167353.812136.29537383.812127.10527543.812 126.686
7713.813106.87567973.814100.31278573.816103.53288713.81699.522198723.816103.7466
9203.81898.70697 9913.82103.0839 9943.8291.4931410013.8289.1567110043.82100.0267
10093.83103.863511369.5598.7550811430.48108.3916 11501.7110.393311995.61107.0782
12037.08112.109912326.46118.051712349.67 123.46712391.56123.245812492.23134.0278
#Mann= 3 , 0 , 0
7017.284  0.0401       07017.284  0.0401       012492.23  0.0401       0
#XS Ineff= 2 , 0
       09085.435                       0
Bank Sta=7017.284,12492.23
Exp/Cntr=0.3,0.1