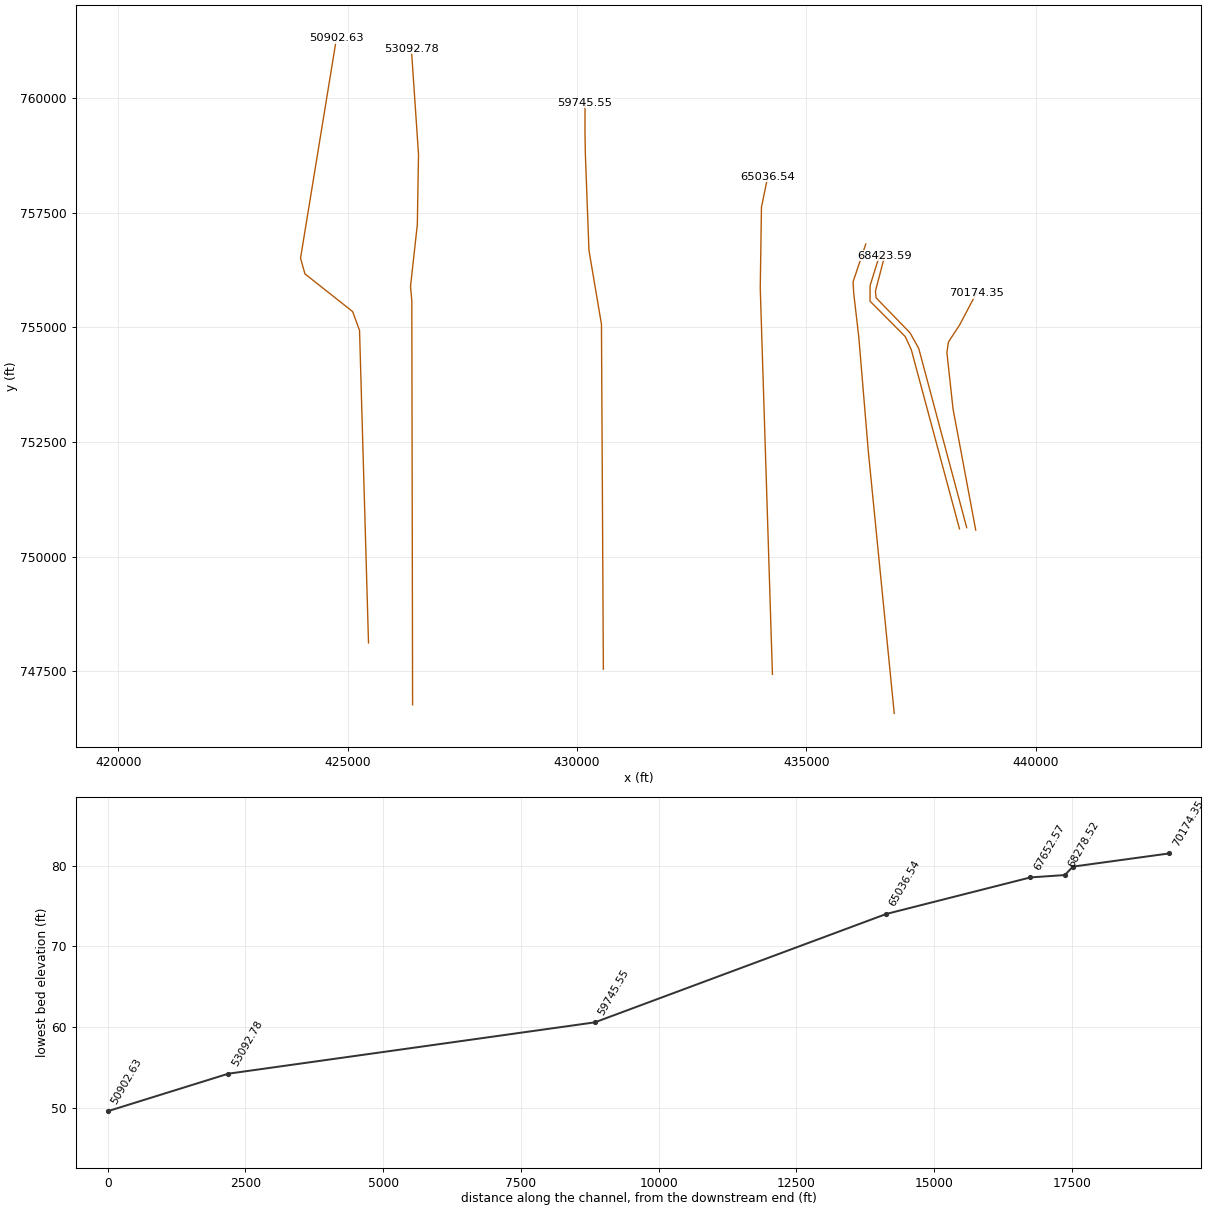
HEC-RAS study 2549_ras.prj: 2549

--- 2549_ras.g01 (geometry) --- (continued)

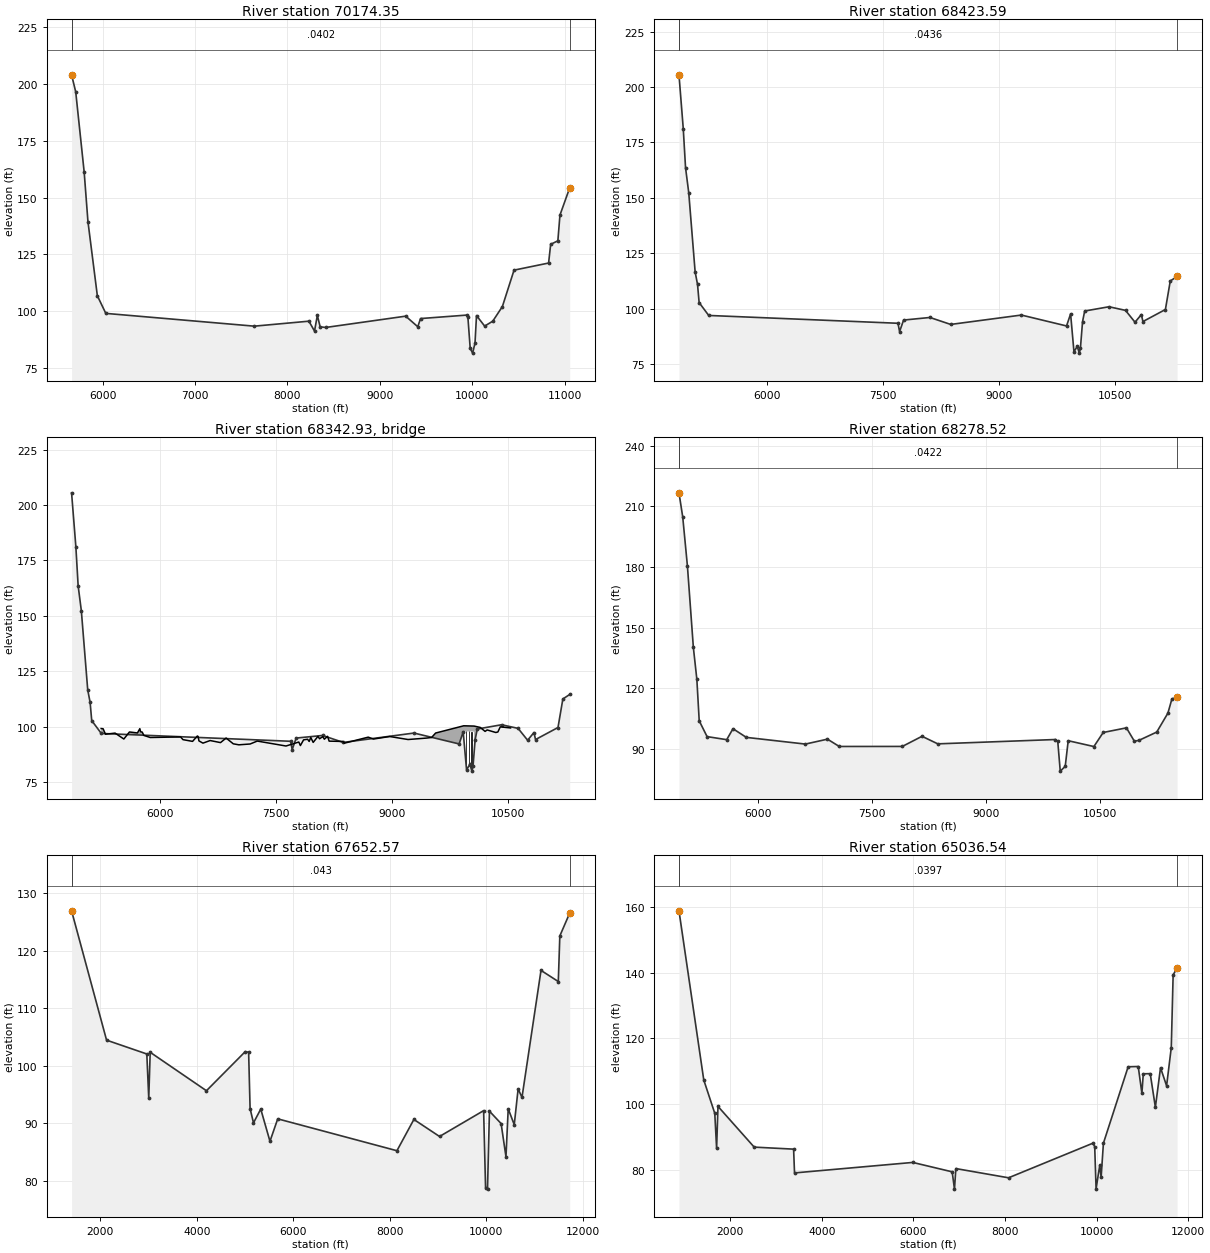
Type RM Length L Ch R = 1 ,70174.35,1750.760900,1750.760900,1750.760900
XS GIS Cut Line= 6
  438695.2795322750581.216796053438201.368433177753218.254840359
438066.819822133754451.617108867 438099.76065141754680.051996842
438347.782023907755060.469735727438710.847886145755749.828948572
#Sta/Elev= 30
5664.976204.00725709.861 196.5075801.415161.17815842.106139.42585943.834106.7681
6035.38898.999447642.679 93.37748232.69895.567968293.73491.225228324.25298.11358
8354.69493.09183 8415.05 92.80439280.15297.780599410.92493.124139441.102 96.7247
9940.61598.250919952.86597.587119978.35883.57917 10004.5 81.507810030.2285.94146
10046.4898.0403910134.6493.4043310222.6495.5799810326.57 102.02110452.64118.0354
 10826.5121.162310848.97129.385510926.82130.955410949.46142.265211054.74154.2501
#Mann= 3 , 0 , 0
5664.976  0.0402       05664.976  0.0402       011054.74  0.0402       0
#XS Ineff= 2 , 0
       07318.333                       0
Bank Sta=5664.976,11054.74
Exp/Cntr=0.3,0.1

Type RM Length L Ch R = 1 ,68423.59,145.072000,145.072000,145.072000
XS GIS Cut Line= 6
438498.885274448750632.751697129437451.618722528754544.403567225
437260.646500289754884.681344986436523.898815215755643.492108867
436508.273815215755791.061553314 436709.29909169756558.998738048
#Sta/Elev= 30
4859.741205.49374915.002181.26184944.716163.54264986.041152.28055068.693116.5307
5099.688 110.895 5120.35102.69435244.32896.879727692.88593.349387713.54889.58956
7765.20594.794548106.14395.966978374.76192.82703 9289.17 97.06049873.19792.14016
9925.85997.573839969.34380.4462410011.3482.9265410038.9779.8739710052.7882.06294
10080.4194.0835910108.0498.8775410422.78100.8088   1063699.1712510759.0693.82343
10841.1197.2815310861.6294.1303311152.1699.5620811215.19112.443211303.42114.4714
#Mann= 3 , 0 , 0
4859.741  0.0436       04859.741  0.0436       011303.42  0.0436       0
#XS Ineff= 2 , 0
       06510.713         10098.5       0
Bank Sta=4859.741,11303.42
Exp/Cntr=0.3,0.1

Type RM Length L Ch R = 3 ,68342.93,,,
BEGIN DESCRIPTION:
END DESCRIPTION:
Bridge Culvert--1,0,-1,-1, 0
Deck Dist Width WeirC Skew NumUp NumDn MinLoCord MaxHiCord MaxSubmerge Is_Ogee
59.248650,26.574700,2.6,0, 60, 60, , , 0.95, 0, 0,0,,
 5242.50 5267.39 5298.39 5422.40 5536.06 5608.40 5711.73 5742.73 5753.07 5773.73
 5794.40 5877.07 6269.74 6300.74 6424.74 6486.74 6497.07 6507.40 6559.07 6652.07
 6786.41 6858.74 6951.74 7024.08 7169.58 7261.74 7633.75 7799.08 7819.75 7861.08
 7912.75 7933.42 7954.08 7985.08 8047.08 8067.75 8109.08 8129.75 8171.08 8191.75
 8367.42 8388.34 8697.11 8765.47 8974.92 9212.50 9451.08 9517.18 9569.02 9932.74
 9932.7410067.2610067.2610146.2010208.9710235.7510347.3210374.3910405.3110538.52
   99.10   99.02   96.53   97.04   94.37   97.55   97.11   99.04   97.65   97.50
   96.01   95.05   95.31   94.09   93.30   95.73   95.51   93.52   92.51   93.68
   92.75   94.80   92.20   91.75   92.12   93.44   91.21   93.01   91.42   93.99
   94.27   93.27   95.07   92.84   95.57   94.48   95.45   94.29   95.60   93.41
   93.27   92.49   95.21   94.36   95.50   94.14   94.79   95.06   97.07  100.34
  100.34  100.21  100.21   99.60   97.81   98.46   97.31   97.54   99.85   99.37
 -900.90 -900.98 -903.47 -902.96 -905.63 -902.45 -902.89 -900.96 -902.35 -902.50
 -903.99 -904.95 -904.69 -905.91 -906.70 -904.27 -904.49 -906.48 -907.49 -906.32
 -907.25 -905.20 -907.80 -908.25 -907.88 -906.56 -908.79 -906.99 -908.58 -906.01
 -905.73 -906.73 -904.93 -907.16 -904.43 -905.52 -904.55 -905.71 -904.40 -906.59
 -906.73 -907.51 -904.79 -905.64 -904.50 -905.86 -905.21 -904.94 -902.93 -899.66
   97.84   97.71 -899.79 -900.40 -902.19 -901.54 -902.69 -902.46 -900.15 -900.63
 5242.50 5267.39 5298.39 5422.40 5536.06 5608.40 5711.73 5742.73 5753.07 5773.73
 5794.40 5877.07 6269.74 6300.74 6424.74 6486.74 6497.07 6507.40 6559.07 6652.07
 6786.41 6858.74 6951.74 7024.08 7169.58 7261.74 7633.75 7799.08 7819.75 7861.08
 7912.75 7933.42 7954.08 7985.08 8047.08 8067.75 8109.08 8129.75 8171.08 8191.75
 8367.42 8388.34 8697.11 8765.47 8974.92 9212.50 9451.08 9517.18 9569.02 9932.74
 9932.7410067.2610067.2610146.2010208.9710235.7510347.3210374.3910405.3110538.52
   99.10   99.02   96.53   97.04   94.37   97.55   97.11   99.04   97.65   97.50
   96.01   95.05   95.31   94.09   93.30   95.73   95.51   93.52   92.51   93.68
   92.75   94.80   92.20   91.75   92.12   93.44   91.21   93.01   91.42   93.99
   94.27   93.27   95.07   92.84   95.57   94.48   95.45   94.29   95.60   93.41
   93.27   92.49   95.21   94.36   95.50   94.14   94.79   95.06   97.07  100.34
  100.34  100.21  100.21   99.60   97.81   98.46   97.31   97.54   99.85   99.37
 -900.90 -900.98 -903.47 -902.96 -905.63 -902.45 -902.89 -900.96 -902.35 -902.50
 -903.99 -904.95 -904.69 -905.91 -906.70 -904.27 -904.49 -906.48 -907.49 -906.32
 -907.25 -905.20 -907.80 -908.25 -907.88 -906.56 -908.79 -906.99 -908.58 -906.01
 -905.73 -906.73 -904.93 -907.16 -904.43 -905.52 -904.55 -905.71 -904.40 -906.59
 -906.73 -907.51 -904.79 -905.64 -904.50 -905.86 -905.21 -904.94 -902.93 -899.66
   97.84   97.71 -899.79 -900.40 -902.19 -901.54 -902.69 -902.46 -900.15 -900.63
Pier Skew, UpSta & Num, DnSta & Num=  ,9965.62, 2 ,9965.62, 2 , 0 , 0 , 0 ,,
    3.00    3.00
 -899.67  100.33
    3.00    3.00
 -899.67  100.33
Pier Skew, UpSta & Num, DnSta & Num=  ,10000.00, 2 ,10000.00, 2 , 0 , 0 , 0 ,,
    3.00    3.00
 -899.71  100.29
    3.00    3.00
 -899.71  100.29
Pier Skew, UpSta & Num, DnSta & Num=  ,10034.38, 2 ,10034.38, 2 , 0 , 0 , 0 ,,
    3.00    3.00
 -899.75  100.25
    3.00    3.00
 -899.75  100.25
BR Coef=-1 , 0 , 0 ,, 0 ,,,0.8,0,1,0,
WSPro=,,,, 1 ,,,, 0 ,,,, 0 ,,,,-1 ,-1 ,-1 , 0 , 0 , 0 , 0 , 0
BC Design=,, 0 ,, 0 ,,,,,,

Type RM Length L Ch R = 1 ,68278.52,625.950900,625.950900,625.950900
XS GIS Cut Line= 6
438341.192180813750607.426862404437290.088051289754514.600326464
437157.709578991754801.058659792436390.218259573755572.311553314
436392.536401689755913.574355617 436612.28366788756620.051547865
#Sta/Elev= 30
4967.958 216.7445017.022204.82945078.901 180.4165156.814140.1143 5202.66124.2812
  5233.6103.76915336.73395.940125594.56494.42038 5677.0799.849845852.39595.55234
6627.45192.237566917.17694.675117072.38691.052947900.17191.070328158.854 96.0937
  8365.8 92.34749910.01894.496159941.06793.526169973.59878.8329710038.9681.17726
10078.19 93.903810415.3391.0166710537.63 97.983510842.66100.282510947.3893.61893
11010.2294.1356711240.6298.1933711387.23107.584811439.59 114.61611507.72115.4725
#Mann= 3 , 0 , 0
4967.958  0.0422       04967.958  0.0422       011507.72  0.0422       0
#XS Ineff= 2 , 0
       06657.237        10085.06       0
Bank Sta=4967.958,11507.72
Exp/Cntr=0.3,0.1

Type RM Length L Ch R = 1 ,67652.57,2616.026100,2616.026100,2616.026100
XS GIS Cut Line= 6
436918.331239939746583.256407857436353.586315155752291.683659792
436145.252981782754791.683659792436034.141870677755750.016993135
436020.897290319755995.041729882436297.719381571756818.010107398
#Sta/Elev= 30
1406.718126.94822131.985104.45282966.037102.04783006.232 94.37493036.379102.3427
4202.04295.653475005.947102.45755076.289102.35375106.43592.559095176.77790.06127
5327.509 92.46365518.43786.858895679.21890.763728149.80785.21901 8501.0290.65656
9032.85787.695959946.57492.190619986.78978.74789   1002778.5391810067.2292.09733
10308.8989.9430210409.7484.1662110456.1192.51504 10581.289.7480510661.5795.96546
10741.6894.5025311135.81116.586211494.22114.648211525.89122.5777 11730.2126.5475
#Mann= 3 , 0 , 0
1406.718   0.043       01406.718   0.043       0 11730.2   0.043       0
#XS Ineff= 2 , 0
       07065.309        10406.38       0
Bank Sta=1406.718,11730.2
Exp/Cntr=0.3,0.1

Type RM Length L Ch R = 1 ,65036.54,5290.990700,5290.990700,5290.990700
XS GIS Cut Line= 4
434262.081239939 747433.95085232433996.457241833755863.563241467
434022.810204029757620.527892441434159.316849113758289.503739923
#Sta/Elev= 30
883.4053158.94621424.723107.31451664.84297.159311704.86286.431071734.87799.26993
2525.26986.840243385.696 86.22423405.70678.967125986.98682.168966847.41379.29686
6897.43874.022056927.45380.292588078.02477.480389918.70688.036319958.71186.99484
9988.71474.1341510068.7281.3085210098.7377.6076410148.7388.0259710688.79111.3636
10908.82111.439710988.83103.231611018.83109.213911170.78109.258511283.0599.00193
11395.32111.0651   11528105.541811630.06117.209211670.88139.429211757.13141.4409
#Mann= 3 , 0 , 0
883.4053  0.0397       0883.4053  0.0397       011757.13  0.0397       0
#XS Ineff= 2 , 0
       05256.263        10511.95       0
Bank Sta=883.4053,11757.13
Exp/Cntr=0.3,0.1

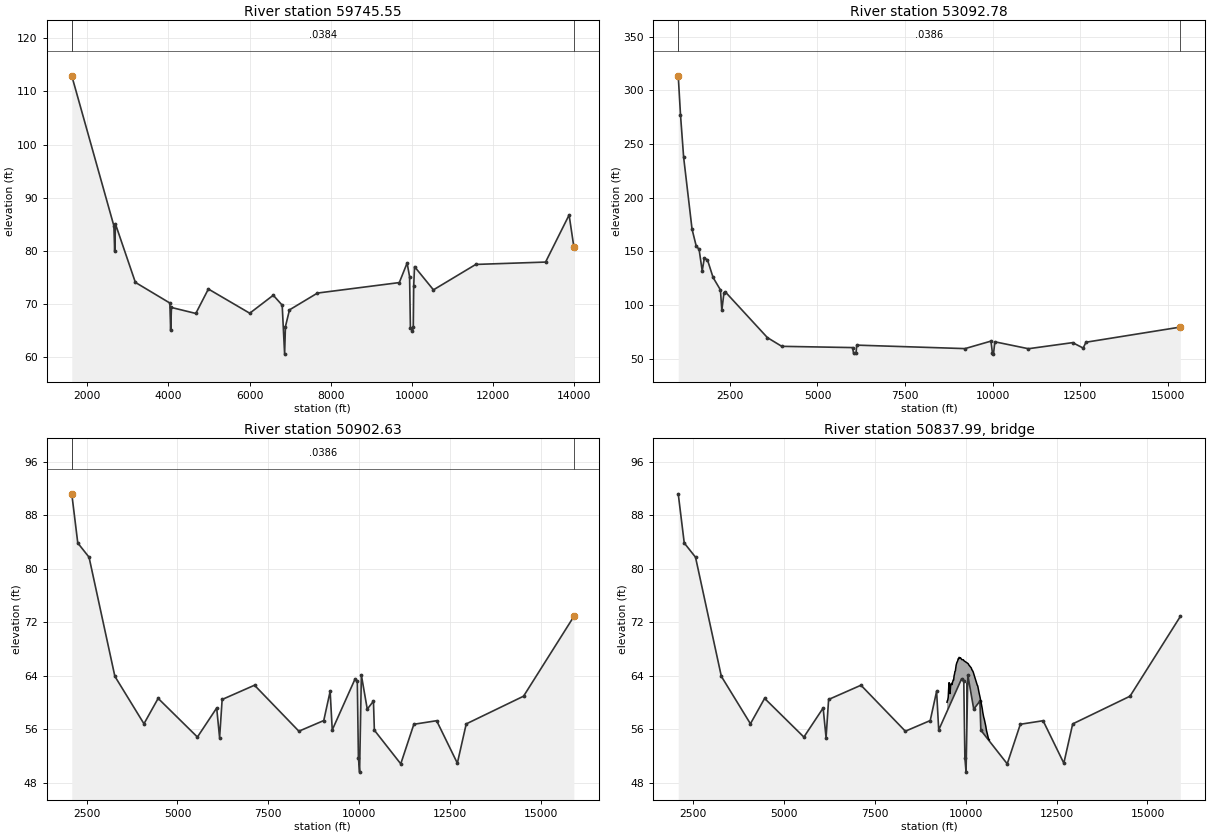
Type RM Length L Ch R = 1 ,59745.55,6652.770700,6652.770700,6652.770700
XS GIS Cut Line= 6
 430575.15994364747546.798074529430533.665413797755067.939253852
430260.841363281756682.049160257430182.027719676758794.387674659
430173.968338817759272.988932744430175.963048995759901.932188258
#Sta/Elev= 30
1617.597112.94432655.81484.743452675.815 79.94832695.81585.065883185.82374.11034
4035.83570.229794055.83665.102064075.83669.391714675.84568.26923 4985.8572.86527
6005.86568.312176585.87471.694876805.87869.825146865.87960.622646885.879 65.7973
 6985.8868.942187675.89172.103319693.67374.074129886.36877.752129947.21975.17435
9967.50265.5921510018.2164.94636 10038.565.6371910048.6473.3716510068.9277.07653
10535.4572.7040911579.3677.4862813300.3877.92975 13880.486.7840113997.3480.79488
#Mann= 3 , 0 , 0
1617.597  0.0384       01617.597  0.0384       013997.34  0.0384       0
#XS Ineff= 2 , 0
       05350.263         11268.6       0
Bank Sta=1617.597,13997.34
Exp/Cntr=0.3,0.1

Type RM Length L Ch R = 1 ,53092.78,2190.153100,2190.153100,2190.153100
XS GIS Cut Line= 6
426415.038781911 746770.57289502 426397.97758463755578.339973062
426369.728124589755896.269928023426518.449864447757241.919852614
426544.150809646758770.544972807426387.851662908761082.394986779
#Sta/Elev= 30
1026.451313.65921090.878277.42441180.879237.65091420.881 170.6911540.882154.8579
1620.882152.08011710.883131.81371770.884143.76881860.884142.11812020.885125.7227
2230.887114.11552270.88795.062412330.888 111.4192370.888112.24983570.898 69.6784
3980.90161.544996000.91760.377746030.91755.007446100.91855.449096120.91862.65918
9210.94259.41876    995266.409559992.47155.4276710022.9854.27532 10063.465.75222
 11020.959.3158612282.94  64.98412582.95 59.929312662.9565.3749415355.6379.48441
#Mann= 3 , 0 , 0
1026.451  0.0386       01026.451  0.0386       015355.63  0.0386       0
#XS Ineff= 2 , 0
       05845.672        11985.28       0
Bank Sta=1026.451,15355.63
Exp/Cntr=0.3,0.1

Type RM Length L Ch R = 1 ,50902.63,119.784100,119.784100,119.784100
XS GIS Cut Line= 6
425453.632165879748119.714741215425258.080950648754934.319775954
425107.039283991755345.778109267424067.832107991756166.796627775
423971.477941334 756510.54662779424754.776370674761304.088617459
#Sta/Elev= 30
2092.01991.18453 2257.36 83.84412567.46381.719993277.69963.938544077.96556.85508
4468.09560.646055548.45554.872066078.63159.211266158.65854.768986228.68160.48106
7118.97762.609528339.80455.745329023.92857.33434 9199.67    61.79257.57855.92898
9885.88763.557139947.03363.194189977.186 51.7972 10009.749.6351110058.47 64.1172
10221.02 59.040410390.9760.2335110416.3455.8923711142.3950.8710811502.4556.78054
12129.1257.3111412699.0150.9717112943.2556.8346614520.6460.9723515903.7472.87381
#Mann= 3 , 0 , 0
2092.019  0.0386       02092.019  0.0386       015903.74  0.0386       0
#XS Ineff= 2 , 0
       05907.358        12749.18       0
Bank Sta=2092.019,15903.74
Exp/Cntr=0.3,0.1

Type RM Length L Ch R = 3 ,50837.99,,,
BEGIN DESCRIPTION:
END DESCRIPTION:
Bridge Culvert--1,0,-1,-1, 0
Deck Dist Width WeirC Skew NumUp NumDn MinLoCord MaxHiCord MaxSubmerge Is_Ogee
40.863200,38.057700,2.6,0, 57, 57, , , 0.95, 0, 0,0,,
 9485.49 9492.73 9505.24 9517.75 9520.43 9537.08 9542.77 9553.72 9555.28 9567.79
 9587.01 9592.81 9605.32 9617.83 9620.30 9655.36 9667.87 9680.38 9692.88 9703.52
 9717.90 9720.17 9736.81 9755.43 9780.45 9792.96 9805.47 9817.98 9843.00 9855.51
 9893.04 9936.54 9950.30 9950.3010049.7010049.7010071.5110080.6810155.7410168.24
10180.7510205.7710318.3610330.8710368.7410397.3110410.7710425.8910454.4710468.75
10494.7710511.6210554.4810568.7710620.7810634.7810652.13
   60.07   60.27   60.39   60.77   60.95   62.69   62.99   62.65   62.42   61.36
   62.63   62.76   62.88   62.80   62.69   63.38   63.37   64.03   64.28   64.66
   64.76   64.94   65.60   65.97   66.26   66.56   66.54   66.77   66.67   66.71
   66.43   66.41   66.27   66.27   65.90   65.90   65.81   65.68   65.17   64.92
   64.86   64.59   62.61   62.51   61.45   60.76   60.31   59.96   59.14   58.59
   57.85   57.53   56.44   55.92   54.75   54.56   54.45
 -939.93 -939.73 -939.61 -939.23 -939.05 -937.31 -937.01 -937.35 -937.58 -938.64
 -937.37 -937.24 -937.12 -937.20 -937.31 -936.62 -936.63 -935.97 -935.72 -935.34
 -935.24 -935.06 -934.40 -934.03 -933.74 -933.44 -933.46 -933.23 -933.33 -933.29
 -933.57 -933.59 -933.73   63.27   62.90 -934.10 -934.19 -934.32 -934.83 -935.08
 -935.14 -935.41 -937.39 -937.49 -938.55 -939.24 -939.69 -940.04 -940.86 -941.41
 -942.15 -942.47 -943.56 -944.08 -945.25 -945.44 -945.55
 9485.49 9492.73 9505.24 9517.75 9520.43 9537.08 9542.77 9553.72 9555.28 9567.79
 9587.01 9592.81 9605.32 9617.83 9620.30 9655.36 9667.87 9680.38 9692.88 9703.52
 9717.90 9720.17 9736.81 9755.43 9780.45 9792.96 9805.47 9817.98 9843.00 9855.51
 9893.04 9936.54 9950.30 9950.3010049.7010049.7010071.5110080.6810155.7410168.24
10180.7510205.7710318.3610330.8710368.7410397.3110410.7710425.8910454.4710468.75
10494.7710511.6210554.4810568.7710620.7810634.7810652.13
   60.07   60.27   60.39   60.77   60.95   62.69   62.99   62.65   62.42   61.36
   62.63   62.76   62.88   62.80   62.69   63.38   63.37   64.03   64.28   64.66
   64.76   64.94   65.60   65.97   66.26   66.56   66.54   66.77   66.67   66.71
   66.43   66.41   66.27   66.27   65.90   65.90   65.81   65.68   65.17   64.92
   64.86   64.59   62.61   62.51   61.45   60.76   60.31   59.96   59.14   58.59
   57.85   57.53   56.44   55.92   54.75   54.56   54.45
 -939.93 -939.73 -939.61 -939.23 -939.05 -937.31 -937.01 -937.35 -937.58 -938.64
 -937.37 -937.24 -937.12 -937.20 -937.31 -936.62 -936.63 -935.97 -935.72 -935.34
 -935.24 -935.06 -934.40 -934.03 -933.74 -933.44 -933.46 -933.23 -933.33 -933.29
 -933.57 -933.59 -933.73   63.27   62.90 -934.10 -934.19 -934.32 -934.83 -935.08
 -935.14 -935.41 -937.39 -937.49 -938.55 -939.24 -939.69 -940.04 -940.86 -941.41
 -942.15 -942.47 -943.56 -944.08 -945.25 -945.44 -945.55
Pier Skew, UpSta & Num, DnSta & Num=  ,10000.00, 2 ,10000.00, 2 , 0 , 0 , 0 ,,
    3.00    3.00
 -933.92   66.08
    3.00    3.00
 -933.92   66.08
BR Coef=-1 , 0 , 0 ,, 0 ,,,0.8,0,1,0,
WSPro=,,,, 1 ,,,, 0 ,,,, 0 ,,,,-1 ,-1 ,-1 , 0 , 0 , 0 , 0 , 0
BC Design=,, 0 ,, 0 ,,,,,,