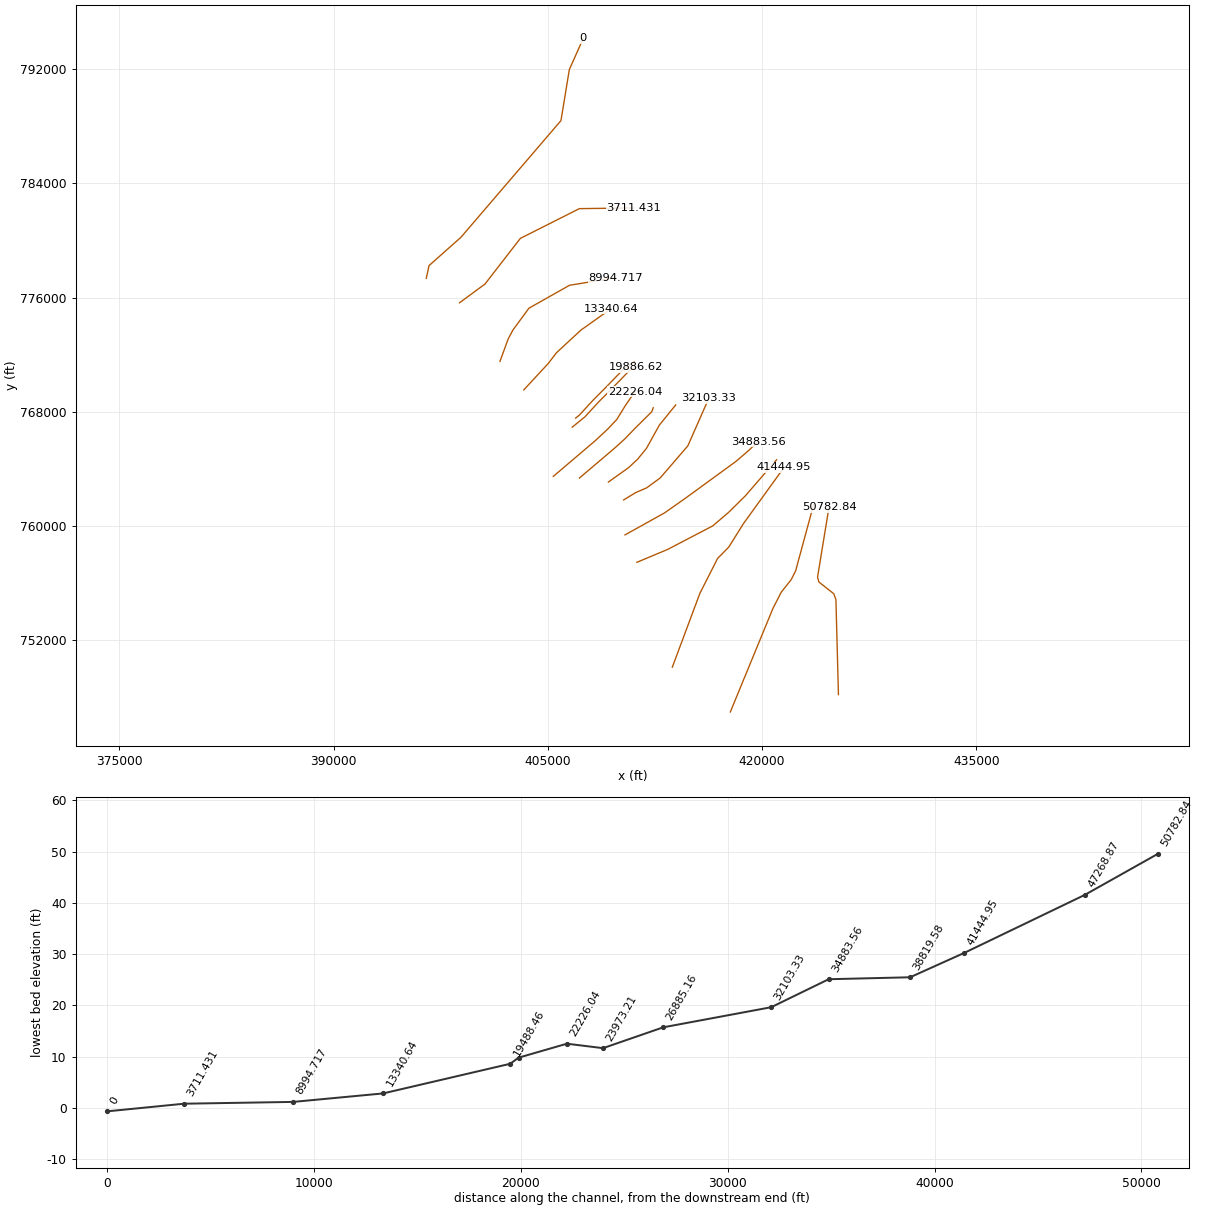
HEC-RAS study 2549_ras.prj: 2549

--- 2549_ras.g01 (geometry) --- (continued)

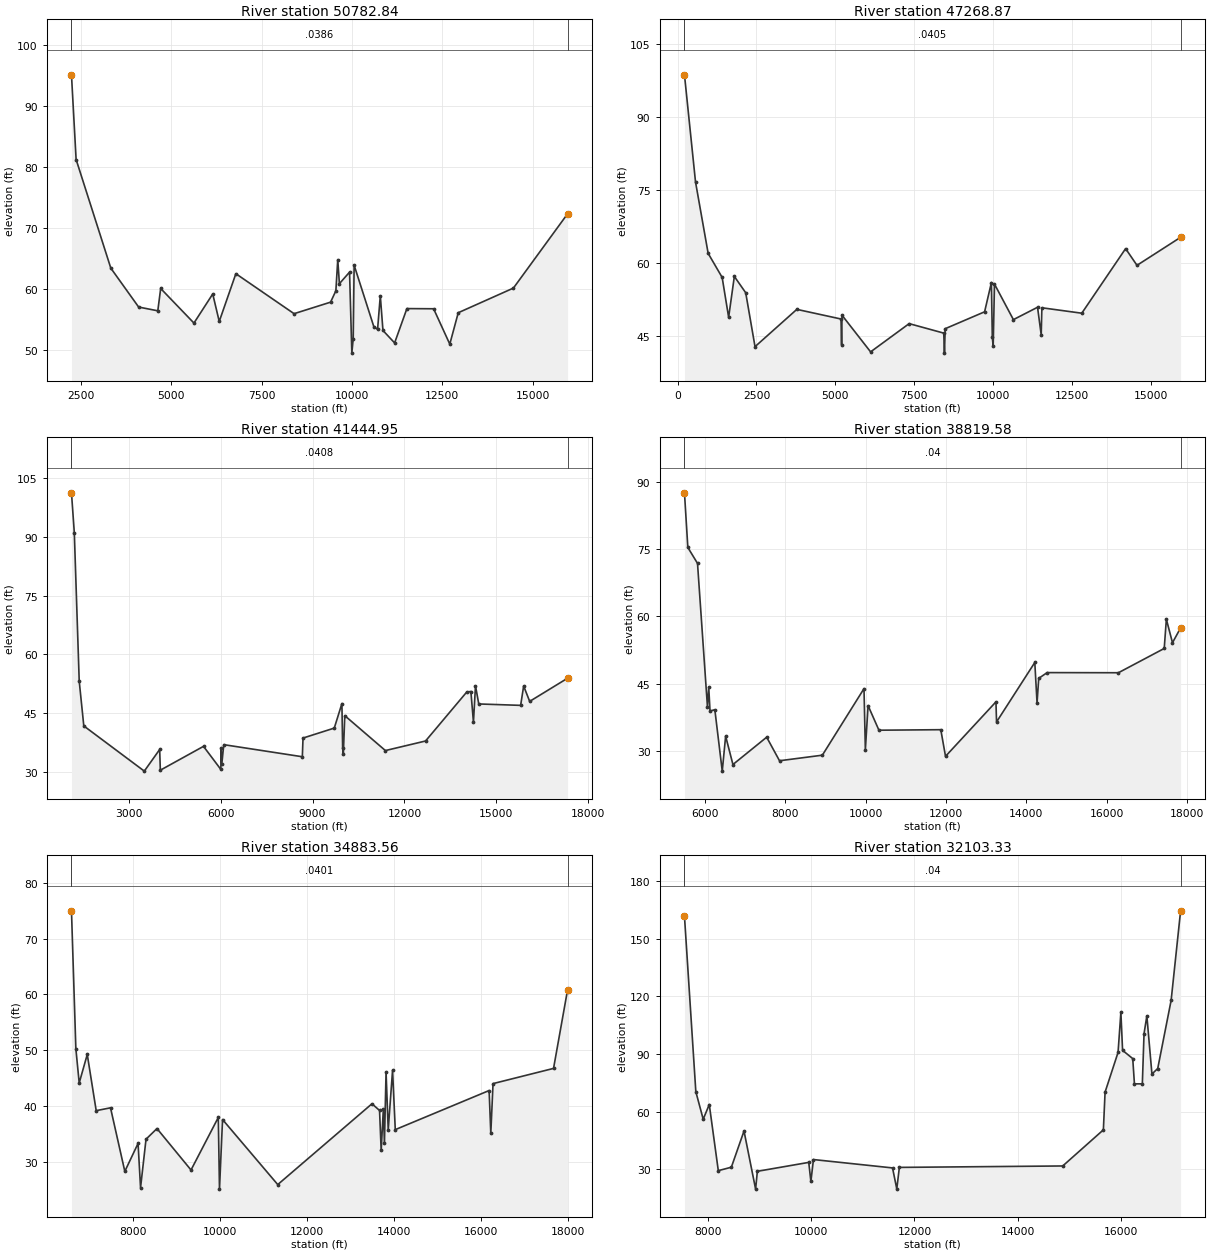
Type RM Length L Ch R = 1 ,50782.84,3513.977800,3513.977800,3513.977800
XS GIS Cut Line= 6
425349.465499192748206.520296752  425173.0115062754856.194775954
425021.969839513755267.653109267423982.762663543756088.671627775
423886.408496886 756432.42162779424685.393532932761309.044534445
#Sta/Elev= 30
2239.41795.10588 2367.9381.231713328.17863.435194098.377 57.06034628.51556.44322
4708.53560.100835628.773 54.43516148.90859.201586328.95454.696186789.07362.52275
8400.034 55.97289410.23857.860789556.90259.721779609.07764.824099654.45660.88862
9935.33862.780239998.75849.5102110036.81 51.877910062.1863.9188210607.5953.83925
10711.0653.4018610786.4558.9114710860.0153.2203311182.5851.1816711522.6356.80731
12261.9156.7773712709.6950.9837312943.7556.1297514470.2560.1658515970.3472.34413
#Mann= 3 , 0 , 0
2239.417  0.0386       02239.417  0.0386       015970.34  0.0386       0
#XS Ineff= 2 , 0
       05997.812        12843.29       0
Bank Sta=2239.417,15970.34
Exp/Cntr=0.3,0.1

Type RM Length L Ch R = 1 ,47268.87,5823.915000,5823.915000,5823.915000
XS GIS Cut Line= 6
417780.021054745746991.242518961420760.437023818754233.222169474
421340.043073297755369.842507482422031.160042197756239.847476363
422348.219637364756855.321068481423607.976637304761497.738039494
#Sta/Elev= 30
217.8176  98.594568.245576.62773968.725361.99612  1412.557.071251618.15248.89786
1798.82657.269522159.28453.928532454.454 42.87613779.70150.520915180.79148.54472
5198.74743.272075213.11449.309876118.57841.808427341.29247.59854 8437.8245.65325
8460.10141.551418483.02746.55851 9732.4750.020199948.59856.027029976.99844.75511
10004.5542.9781210046.0455.7052810645.4748.4162511411.0850.9536411527.3845.29632
11548.4550.8484212813.8349.7327814202.8162.97142 14563.759.5466915946.5565.29205
#Mann= 3 , 0 , 0
217.8176  0.0405       0217.8176  0.0405       015946.55  0.0405       0
#XS Ineff= 2 , 0
       07717.528        13189.14       0
Bank Sta=217.8176,15946.55
Exp/Cntr=0.3,0.1

Type RM Length L Ch R = 1 ,41444.95,2625.373400,2625.373400,2625.373400
XS GIS Cut Line= 6
413718.778654665750128.153913543415649.142376274755298.474049926
416888.266516745 757739.29902494 417673.77748549758537.235214308
418698.986119092760178.275996402421548.443885982764121.427562147
#Sta/Elev= 30
1133.208101.2021 1225.9191.018421386.02453.184951535.46341.774833510.19730.24987
4011.886 35.77254033.23530.488275442.234 36.56596007.96930.682686018.643 36.1184
6039.99232.115526104.03736.996478667.98533.915078690.24438.682139710.30641.22291
9959.43547.476159982.83436.26764 10006.334.70433 10053.244.3926811378.5535.49246
12689.4837.9321814035.0650.4342214168.7850.5408314252.3542.7386714319.2152.01161
14425.5147.3748815792.4847.0153915890.9351.94322 16087.648.0284617325.5453.94272
#Mann= 3 , 0 , 0
1133.208  0.0408       01133.208  0.0408       017325.54  0.0408       0
#XS Ineff= 2 , 0
       07553.241         12754.7       0
Bank Sta=1133.208,17325.54
Exp/Cntr=0.3,0.1

Type RM Length L Ch R = 1 ,38819.58,3936.019300,3936.019300,3936.019300
XS GIS Cut Line= 6
411237.684968442 757469.76296553413385.737226337758368.039364263
416546.662520498760017.409691975 417642.59854129760950.344011754
418818.421779573762108.890068457421015.409232646 764645.19204767
#Sta/Elev= 30
5493.77187.529585577.57475.346035818.38371.800696065.33739.866276097.85544.15312
 6129.4238.896826249.60339.168496433.86925.483426518.216 33.28196699.65426.95656
7539.46433.048727858.937 27.79648925.08129.037289961.32943.88203 9995.1230.23623
 10062.740.0924810333.0334.6057111872.4434.7217211989.9328.7847513245.1540.93183
13259.67 36.449914211.7349.7091514267.6340.6982914309.5646.1686414518.8447.44924
16292.5547.4195617432.5552.8323217485.5359.3502717637.7254.1134717840.0957.41366
#Mann= 3 , 0 , 0
5493.771    0.04       05493.771    0.04       017840.09    0.04       0
#XS Ineff= 2 , 0
       07535.648        13309.42       0
Bank Sta=5493.771,17840.09
Exp/Cntr=0.3,0.1

Type RM Length L Ch R = 1 ,34883.56,2780.232300,2780.232300,2780.232300
XS GIS Cut Line= 6
410406.965548694759388.541661814413166.394055039760923.811933681
414624.727388263761948.117489234418147.437580168764513.307402253
419097.583747715 765323.39120774 419713.19765687765924.879546061
#Sta/Elev= 30
6592.27474.981196693.01750.279676770.10344.125936955.21649.238347160.89839.16725
7489.98839.676677819.07928.282488123.46233.298358180.67925.361348306.55934.05219
8558.317 35.95919341.12328.532029968.30337.946739995.68525.1031210066.0637.57481
11335.3525.9185813501.8440.4000513676.3439.2024213713.7432.0528713763.5939.45975
13788.5233.3168713825.9146.0884213875.7735.7496513975.4946.3928214037.8135.76701
16195.8742.7733416234.3835.0960316285.8544.0147217677.0246.7387918000.6560.85902
#Mann= 3 , 0 , 0
6592.274  0.0401       06592.274  0.0401       018000.65  0.0401       0
#XS Ineff= 2 , 0
       08531.189        13650.72       0
Bank Sta=6592.274,18000.65
Exp/Cntr=0.3,0.1

Type RM Length L Ch R = 1 ,32103.33,5218.162500,5218.162500,5218.162500
XS GIS Cut Line= 6
410311.685776561761836.937809885411149.654737204762347.113809288
  411926.5016976762685.120402262412868.028892875763373.074086457
414805.528892875765623.074086457416273.726571262768952.879029289
#Sta/Elev= 30
7547.791161.62667767.79170.32093 7910.3456.013458028.02663.665168202.65229.25866
8455.54631.046338700.37849.876158924.98519.643938958.555 28.9132  9953.733.55831
9994.99423.6135310044.5335.0333311575.5730.6772611657.7819.7431111707.5330.95149
14870.2231.6967615657.11 50.486615689.8970.1144515941.2690.78032 15995.9 111.638
16028.6991.8437116225.4187.55597 16258.274.41949 16411.274.4137416443.99100.4912
16498.63109.789316596.9979.5348116709.0582.3928616968.58117.844217152.05164.4461
#Mann= 3 , 0 , 0
7547.791    0.04       07547.791    0.04       017152.05    0.04       0
#XS Ineff= 2 , 0
       08586.836        13507.41       0
Bank Sta=7547.791,17152.05
Exp/Cntr=0.3,0.1

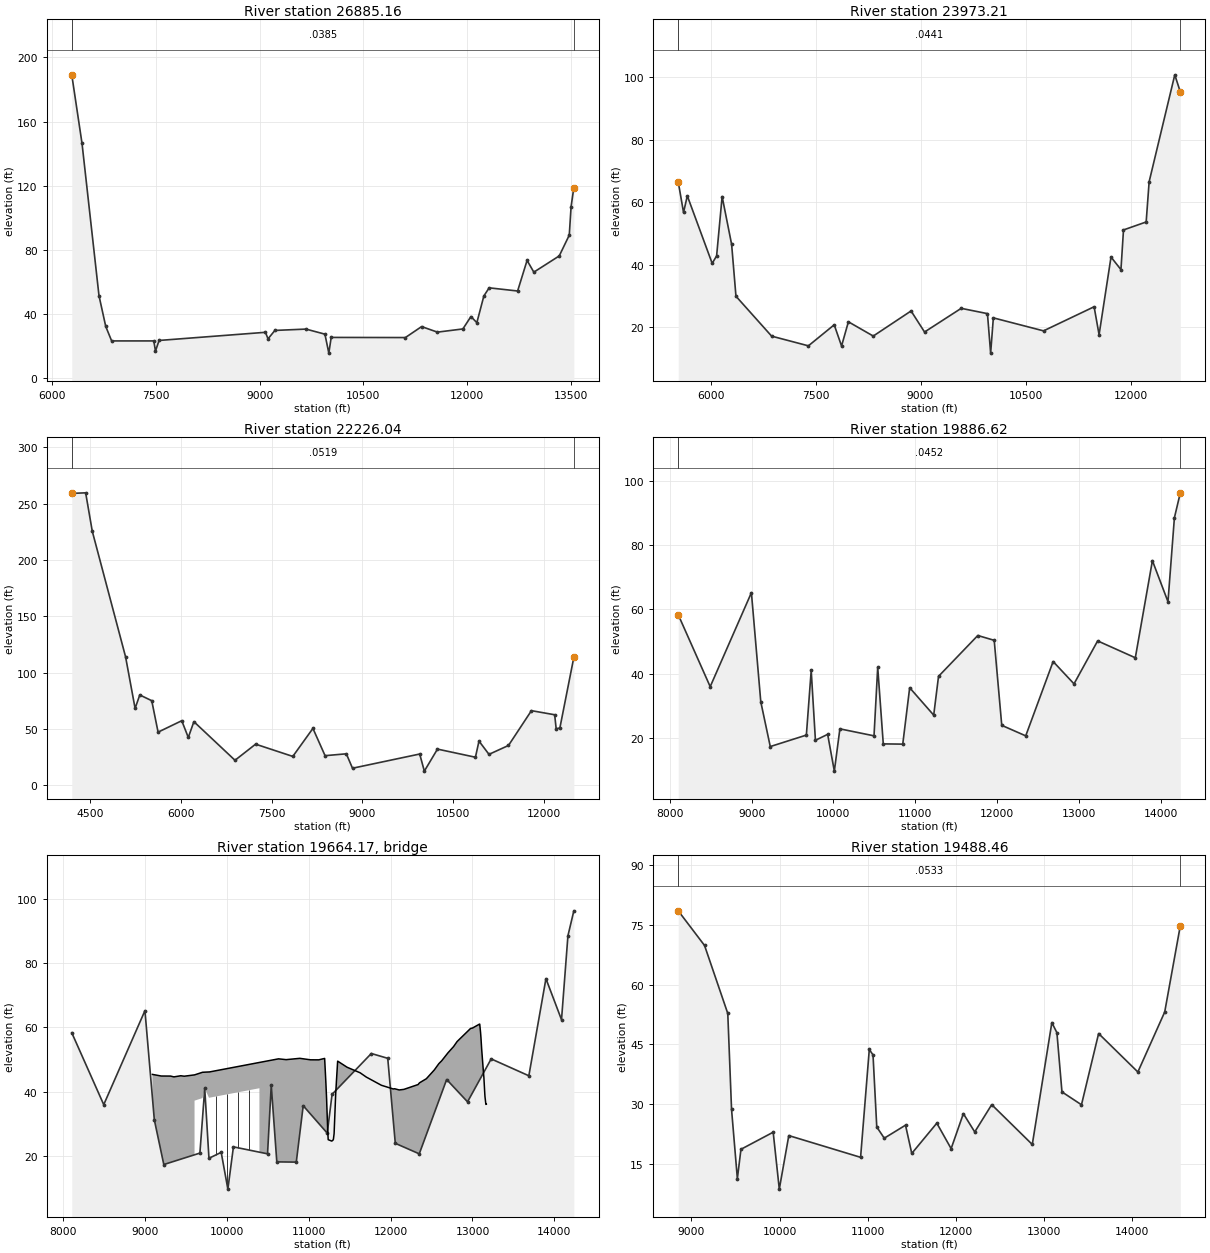
Type RM Length L Ch R = 1 ,26885.16,2911.957500,2911.957500,2911.957500
XS GIS Cut Line= 6
409242.491775781763089.252713516410651.946587533764092.528877184
411280.399399161 764678.11651364411911.563815892765450.646115974
412812.970965236  767078.9043625413954.282126814768485.150271118
#Sta/Elev= 30
6279.861189.1687 6428.33146.41416674.00551.506186771.63832.361166857.06623.33554
7467.27323.333627491.68117.019227543.74623.62449 9083.47 28.70659120.95124.63922
9220.20829.873679670.22530.70496 9944.5727.5484910001.0915.72698 10035.225.51365
11109.5825.4307411344.3732.2714711572.9428.8092611941.8430.8011112058.2738.53145
12143.9534.7053712245.6151.3539312321.85 56.421112734.1654.4459312871.11 73.5119
12968.88 66.190913336.6976.3072713481.9189.2737513508.31107.065813548.12118.8925
#Mann= 3 , 0 , 0
6279.861  0.0385       06279.861  0.0385       013548.12  0.0385       0
#XS Ineff= 2 , 0
       07744.395        11473.77       0
Bank Sta=6279.861,13548.12
Exp/Cntr=0.3,0.1

Type RM Length L Ch R = 1 ,23973.21,1747.166000,1747.166000,1747.166000
XS GIS Cut Line= 6
407217.218871057763371.079804078409739.898614198765514.763550028
410407.424202412766122.108711138411073.956461608766815.006963059
 412278.26802808768010.968960732412382.434694737768292.218960717
#Sta/Elev= 30
5539.02866.489465614.85356.698835668.62562.028356023.81340.403596087.27742.79626
6166.01461.804096301.78746.469826363.55829.884026873.17617.100517398.23713.99988
7767.00520.732977871.98813.945887969.62621.695018324.81417.130418864.88325.16632
9057.40318.426429581.23126.007499955.94724.3121610001.68 11.664710040.1922.95637
10757.01 18.794111479.6326.5121311550.6217.55631   1172142.4321511862.99 38.4034
11899.2851.1114512223.2753.6642812265.5366.5373512631.93100.778812710.92 95.3227
#Mann= 3 , 0 , 0
5539.028  0.0441       05539.028  0.0441       012710.92  0.0441       0
#XS Ineff= 2 , 0
       08671.479        11722.76       0
Bank Sta=5539.028,12710.92
Exp/Cntr=0.3,0.1

Type RM Length L Ch R = 1 ,22226.04,2339.416000,2339.416000,2339.416000
XS GIS Cut Line= 6
405386.391596168763486.191358969408294.586114109765957.471883342
409188.010950744766789.318500534409833.511531711767473.678666294
410449.805412769768472.193955719411109.503797263769422.989728183
#Sta/Elev= 30
 4191.28259.00554421.085259.49824530.649225.4069 5081.81113.93975239.56268.19145
5316.77780.117595514.86575.036015619.84847.12546 6011.71 57.27246119.81142.38878
6212.46856.435946892.767 22.15647233.96236.462967849.42225.581328182.472 50.4485
8383.52726.247488735.56727.897258837.53315.099689949.86427.7064710026.4212.53105
 10243.832.0761110872.1424.8612110931.1139.1837811096.4227.4145111419.2835.30897
11799.0766.1961412183.5662.5497512208.2950.1270212269.7350.8334212500.93113.5741
#Mann= 3 , 0 , 0
 4191.28  0.0519       0 4191.28  0.0519       012500.93  0.0519       0
#XS Ineff= 2 , 0
       0 8871.59         11332.6       0
Bank Sta=4191.28,12500.93
Exp/Cntr=0.3,0.1

Type RM Length L Ch R = 1 ,19886.62,398.162600,398.162600,398.162600
XS GIS Cut Line= 6
406711.680479109766931.509276718407593.856873989767647.421827719
408553.058262795 768689.08849439409347.329096138769487.699605495
410744.898540586770924.331549942411149.548687845771128.286789834
#Sta/Elev= 30
8103.10558.351798493.73836.025688997.33865.20966 9111.9131.328619227.81717.43289
9669.026 20.99699728.07641.044699779.68719.376549929.21921.2279310010.78 9.80714
10078.7522.9309110495.73 20.760810540.9442.0130210608.9118.2630210846.9418.18784
10931.5635.6940311225.2427.1867111284.1639.2311311764.1151.9074711964.6950.41194
12056.8524.0232112349.8320.7580912684.6643.8300412939.8936.8994313228.7550.23084
13689.14 44.993913897.9775.1390814088.3462.3947514166.73 88.453514239.0196.19621
#Mann= 3 , 0 , 0
8103.105  0.0452       08103.105  0.0452       014239.01  0.0452       0
#XS Ineff= 2 , 0
       09676.514        11463.71       0
Bank Sta=8103.105,14239.01
Exp/Cntr=0.3,0.1

Type RM Length L Ch R = 3 ,19664.17,,,
BEGIN DESCRIPTION:
END DESCRIPTION:
Bridge Culvert--1,0,-1,-1, 0
Deck Dist Width WeirC Skew NumUp NumDn MinLoCord MaxHiCord MaxSubmerge Is_Ogee
173.818900,50.524800,2.6,0, 60, 60, , , 0.95, 0, 0,0,,
 9088.70 9196.53 9310.74 9351.07 9435.14 9477.17 9603.51 9603.51 9701.36 9786.79
10396.4910396.4910630.1410723.1510890.0011020.0811121.2511193.5111207.9611217.68
11222.4211231.5311236.8711280.2311294.6811300.7911309.1311328.4911338.0411352.49
11468.1211627.1011702.4611887.2512031.7812048.7212104.0412161.8512335.2912353.44
12436.4612533.4912588.9012624.3412699.7012768.9612812.2312976.7113000.1213085.77
13088.9113099.1913103.9113112.6113133.9113139.4513148.9013152.8713163.9013169.21
   45.42   44.92   44.90   44.65   45.00   44.86   45.27   45.27   46.08   46.19
   49.13   49.13   50.25   50.00   50.41   49.95   49.94   50.38   43.21   37.71
   34.18   27.83   25.16   24.72   24.99   25.32   27.04   39.34   43.58   49.54
   47.64   45.92   44.59   42.04   40.90   40.97   40.59   40.77   42.27   42.82
   44.08   46.80   48.75   49.66   52.09   54.05   55.62   59.68   59.81   61.03
   61.02   58.39   56.81   53.26   46.17   44.53   40.18   38.55   36.10   36.21
 -954.58 -955.08 -955.10 -955.35 -955.00 -955.14 -954.73   37.27   38.08   38.19
   41.13 -950.87 -949.75 -950.00 -949.59 -950.05 -950.06 -949.62 -956.79 -962.29
 -965.82 -972.17 -974.84 -975.28 -975.01 -974.68 -972.96 -960.66 -956.42 -950.46
 -952.36 -954.08 -955.41 -957.96 -959.10 -959.03 -959.41 -959.23 -957.73 -957.18
 -955.92 -953.20 -951.25 -950.34 -947.91 -945.95 -944.38 -940.32 -940.19 -938.97
 -938.98 -941.61 -943.19 -946.74 -953.83 -955.47 -959.82 -961.45 -963.90 -963.79
 9088.70 9196.53 9310.74 9351.07 9435.14 9477.17 9603.51 9603.51 9701.36 9786.79
10396.4910396.4910630.1410723.1510890.0011020.0811121.2511193.5111207.9611217.68
11222.4211231.5311236.8711280.2311294.6811300.7911309.1311328.4911338.0411352.49
11468.1211627.1011702.4611887.2512031.7812048.7212104.0412161.8512335.2912353.44
12436.4612533.4912588.9012624.3412699.7012768.9612812.2312976.7113000.1213085.77
13088.9113099.1913103.9113112.6113133.9113139.4513148.9013152.8713163.9013169.21
   45.42   44.92   44.90   44.65   45.00   44.86   45.27   45.27   46.08   46.19
   49.13   49.13   50.25   50.00   50.41   49.95   49.94   50.38   43.21   37.71
   34.18   27.83   25.16   24.72   24.99   25.32   27.04   39.34   43.58   49.54
   47.64   45.92   44.59   42.04   40.90   40.97   40.59   40.77   42.27   42.82
   44.08   46.80   48.75   49.66   52.09   54.05   55.62   59.68   59.81   61.03
   61.02   58.39   56.81   53.26   46.17   44.53   40.18   38.55   36.10   36.21
 -954.58 -955.08 -955.10 -955.35 -955.00 -955.14 -954.73   37.27   38.08   38.19
   41.13 -950.87 -949.75 -950.00 -949.59 -950.05 -950.06 -949.62 -956.79 -962.29
 -965.82 -972.17 -974.84 -975.28 -975.01 -974.68 -972.96 -960.66 -956.42 -950.46
 -952.36 -954.08 -955.41 -957.96 -959.10 -959.03 -959.41 -959.23 -957.73 -957.18
 -955.92 -953.20 -951.25 -950.34 -947.91 -945.95 -944.38 -940.32 -940.19 -938.97
 -938.98 -941.61 -943.19 -946.74 -953.83 -955.47 -959.82 -961.45 -963.90 -963.79
Pier Skew, UpSta & Num, DnSta & Num=  ,9734.34, 2 ,9734.34, 2 , 0 , 0 , 0 ,,
    4.00    4.00
 -953.92   46.08
    4.00    4.00
 -953.92   46.08
Pier Skew, UpSta & Num, DnSta & Num=  ,9867.17, 2 ,9867.17, 2 , 0 , 0 , 0 ,,
    4.00    4.00
 -953.41   46.59
    4.00    4.00
 -953.41   46.59
Pier Skew, UpSta & Num, DnSta & Num=  ,10000.00, 2 ,10000.00, 2 , 0 , 0 , 0 ,,
    4.00    4.00
 -952.77   47.23
    4.00    4.00
 -952.77   47.23
Pier Skew, UpSta & Num, DnSta & Num=  ,10132.83, 2 ,10132.83, 2 , 0 , 0 , 0 ,,
    4.00    4.00
 -952.14   47.86
    4.00    4.00
 -952.14   47.86
Pier Skew, UpSta & Num, DnSta & Num=  ,10265.66, 2 ,10265.66, 2 , 0 , 0 , 0 ,,
    4.00    4.00
 -951.50   48.50
    4.00    4.00
 -951.50   48.50
BR Coef=-1 , 0 , 0 ,, 0 ,,,0.8,0,1,0,
WSPro=,,,, 1 ,,,, 0 ,,,, 0 ,,,,-1 ,-1 ,-1 , 0 , 0 , 0 , 0 , 0
BC Design=,, 0 ,, 0 ,,,,,,

Type RM Length L Ch R = 1 ,19488.46,6147.825700,6147.825700,6147.825700
XS GIS Cut Line= 6
406952.169225663767566.840776101407211.912429541767777.630161047
408171.113818347768819.296827719408965.384651691769617.907938823
410362.954096138771054.539883271411052.326465636771489.397900939
#Sta/Elev= 30
8850.327 78.53999148.92669.83257 9412.3652.754999455.124 28.67399521.11111.26183
9561.892 18.62629927.52622.920349996.8968.62015410104.6822.0726110919.1916.61009
11017.9243.7056711060.17  42.33811102.7124.2294811187.7921.4152511428.8724.68801
11499.7717.5868911784.0225.1926911946.3718.7910712085.1927.5868712214.2622.98374
12406.7629.8433912867.1519.8360413089.0750.4604513146.4347.92096 13203.833.04743
 13425.229.8108513619.6947.7096414064.9638.0503514369.6253.1265814546.55 74.8131
#Mann= 3 , 0 , 0
8850.327  0.0533       08850.327  0.0533       014546.55  0.0533       0
#XS Ineff= 2 , 0
       09448.983         11572.4       0
Bank Sta=8850.327,14546.55
Exp/Cntr=0.3,0.1

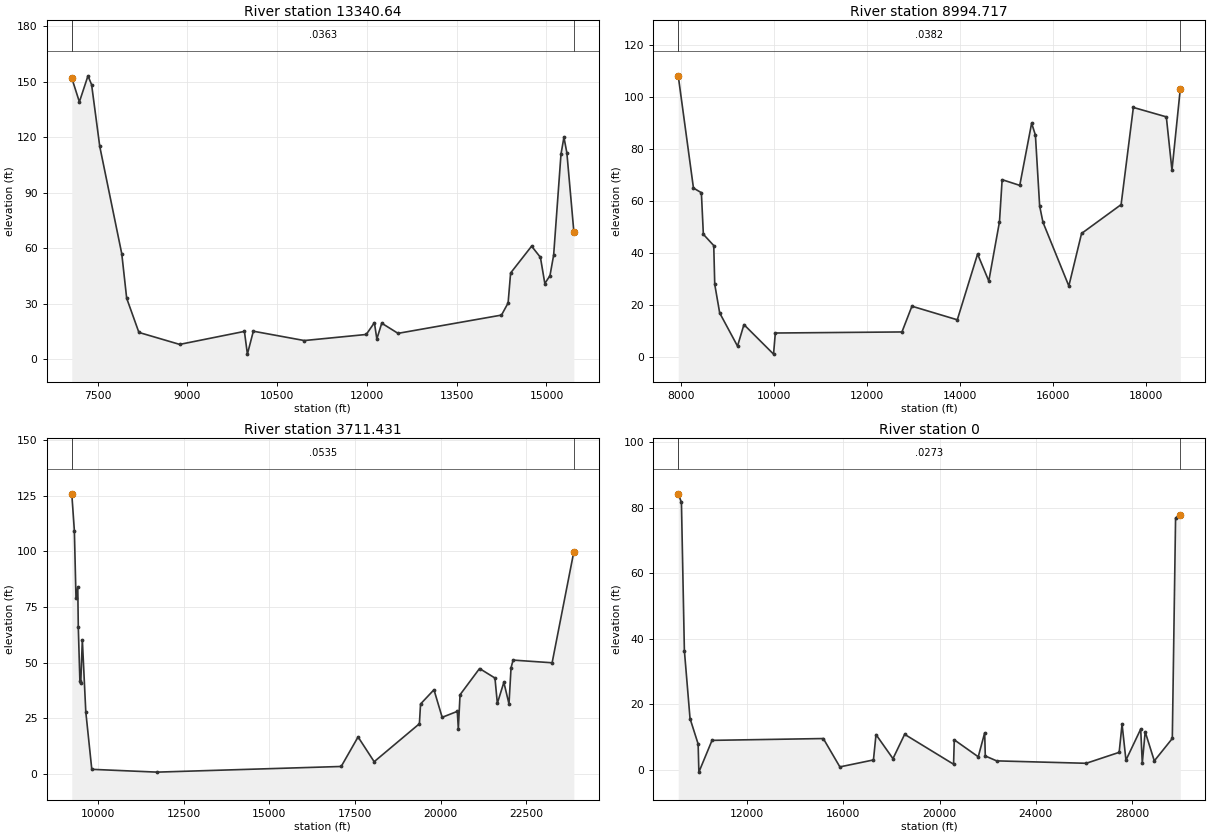
Type RM Length L Ch R = 1 ,13340.64,4345.919300,4345.919300,4345.919300
XS GIS Cut Line= 5
403321.070415586769541.591387913405057.181526691771418.761526793
  405599.7162489772134.907360137407324.976665586773729.959443465
409430.011387855775227.355276793
#Sta/Elev= 30
7068.734151.91587195.968139.01037339.623153.08837400.285148.27147536.496114.9455
7904.26756.988367985.99433.014938190.31214.552168871.369 8.089549953.24715.11124
10002.932.83899510102.29 15.212410953.4910.1714911988.5313.4494312124.7119.82113
12165.5711.0036112247.2919.5398412519.6614.0580114248.2123.9145314358.6630.45437
14400.5846.6397614751.3661.1284314898.6255.0886514972.2540.9635215058.1645.21349
15119.52 56.299515242.24110.788315291.32119.922115340.41111.519215457.0168.99648
#Mann= 3 , 0 , 0
7068.734  0.0363       07068.734  0.0363       015457.01  0.0363       0
#XS Ineff= 2 , 0
       08317.999        12389.35       0
Bank Sta=7068.734,15457.01
Exp/Cntr=0.3,0.1

Type RM Length L Ch R = 1 ,8994.717,5283.286100,5283.286100,5283.286100
XS GIS Cut Line= 6
401651.777866095771537.430187583402219.941943467773091.070554584
402558.483610123773731.695554599403679.143332243775259.907360137
 406522.02527681776865.810137913409742.055643857777388.124632031
#Sta/Elev= 30
7947.531108.09298275.02364.978348445.38663.200978487.97747.218498711.57842.88514
8732.87427.991548839.35117.001739222.6684.2650839361.08812.527279997.8791.185354
10036.049.29565912760.449.70457212974.7219.5939913950.9614.3725714387.3939.63107
14628.5829.2675614858.2952.0157314915.6268.2015715294.7266.0088115550.35 89.9154
 15631.485.3114815722.5858.1081415793.77 51.855716350.6827.3610216624.2147.53824
17475.1958.6213217738.5995.9481518447.7492.32897 18569.371.8253918748.67103.1646
#Mann= 3 , 0 , 0
7947.531  0.0382       07947.531  0.0382       018748.67  0.0382       0
#XS Ineff= 2 , 0
       08665.517        12870.73       0
Bank Sta=7947.531,18748.67
Exp/Cntr=0.3,0.1

Type RM Length L Ch R = 1 ,3711.431,3711.430900,3711.430900,3711.430900
XS GIS Cut Line= 5
  398823.9349989775641.938610122400603.448887795776952.702499017
403077.407221138 780147.14694348407209.351665586782230.480276793
410999.643910944782279.623071924
#Sta/Elev= 30
9226.887125.8971 9302.73109.3644 9350.0879.16716 9402.0983.841029417.52665.91623
9464.18941.628469489.02940.670599535.55760.313239636.72627.877019811.9492.090293
11718.210.83258117098.64 3.37469 17591.4 16.645318061.775.51238919383.2822.57176
19416.8731.4436419808.8537.85438 20048.325.4604120490.5828.1360520520.5820.30501
20570.5935.6006921140.6347.3902321590.6743.1200621660.6831.7327521850.6941.19068
22000.7131.4753122060.71 47.734222120.7251.1802923260.8149.9732923895.5199.90674
#Mann= 3 , 0 , 0
9226.887  0.0535       09226.887  0.0535       023895.51  0.0535       0
#XS Ineff= 2 , 0
       0                 17585.7       0
Bank Sta=9226.887,23895.51
Exp/Cntr=0.3,0.1

Type RM Length L Ch R = 1 ,       0,0.000000,0.000000,0.000000
XS GIS Cut Line= 6
396491.976086885777354.829235137396686.680947989778243.631318465
398912.983031511780218.544512913405921.907380521788395.000000015
406508.826987863791969.209187433407485.111199379794158.957965374
#Sta/Elev= 30
9135.93784.271689268.85681.66876 9391.3936.430239626.24615.708299963.213 7.92884
9993.847-0.6561710540.549.03713615167.269.59331715855.720.93831817251.443.065555
17357.6410.8021418062.543.46093818548.0510.87896   205821.75636520611.58 9.20148
21607.874.02613721875.4211.3454621900.434.27192122373.672.77892226096.342.040673
 27466.45.38263627586.4113.9762627748.35 3.0015928361.4812.4727528427.172.071626
28547.6111.6567528927.332.77535229675.359.60866329811.4176.8864930008.1477.91904
#Mann= 3 , 0 , 0
9135.937  0.0273       09135.937  0.0273       030008.14  0.0273       0
#XS Ineff= 2 , 0
       0                18510.34       0
Bank Sta=9135.937,30008.14
Exp/Cntr=0.3,0.1